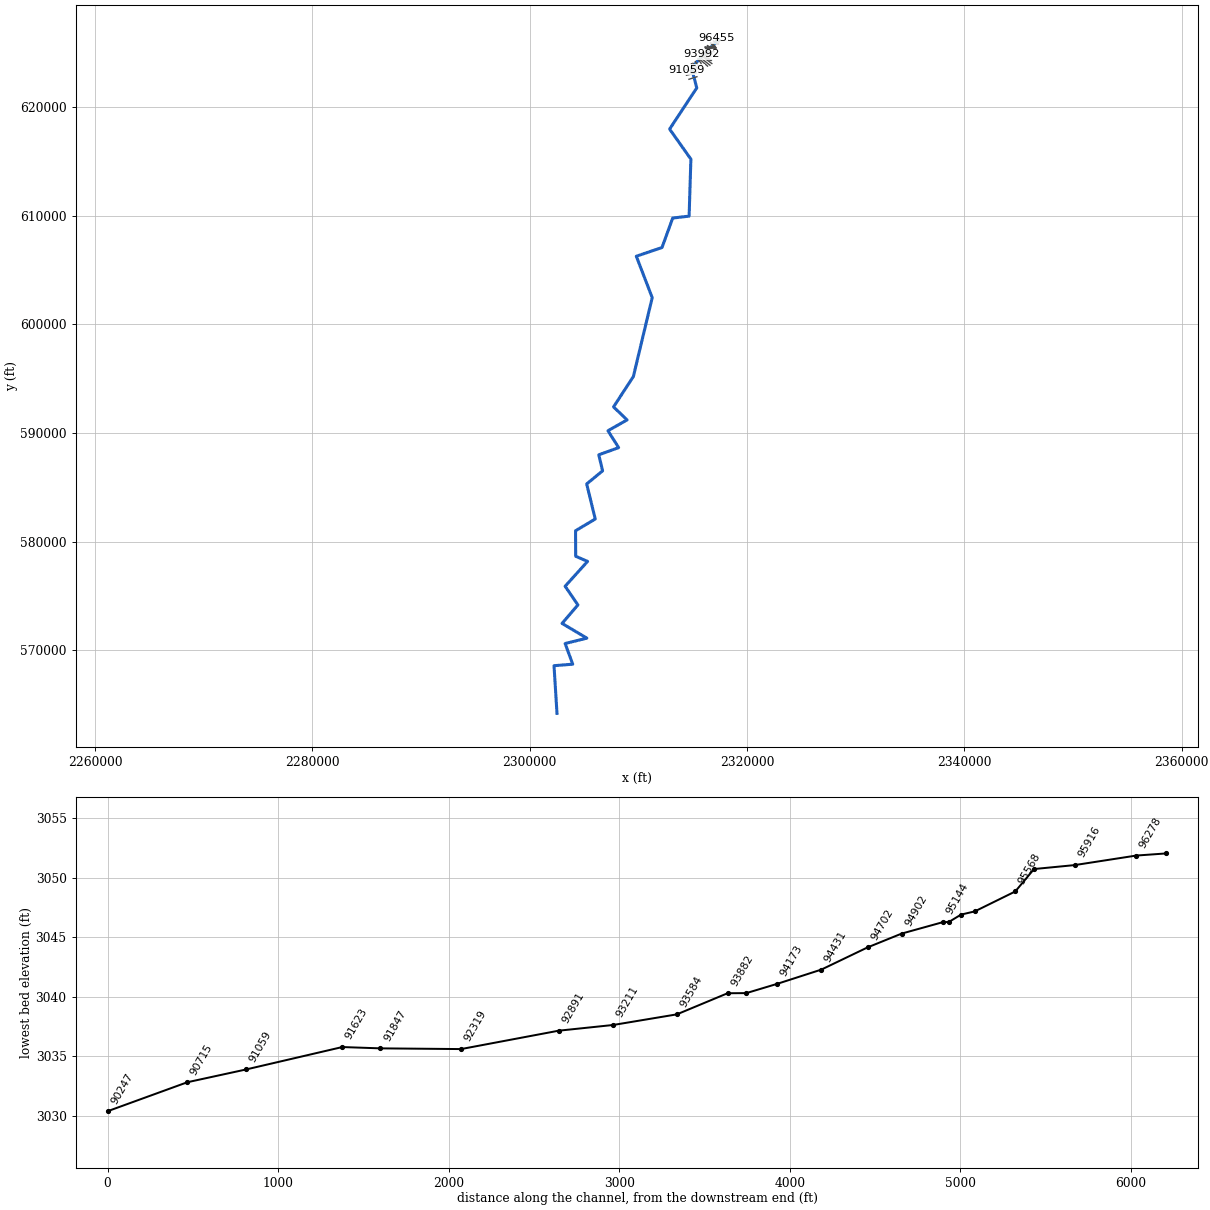
--- WFGRNBRRRV.prj (project) ---

Proj Title=WFGRNBRRRV
Current Plan=p01
Default Exp/Contr=0,0
English Units
Geom File=g01
Flow File=f01
Plan File=p01
Background Map Layer=Inundation Boundary (01pct Value_0)
BEGIN DESCRIPTION:
----------MODEL BY WOOD PLC 2021----------
Stream Name: West Fork Greenbrier River
Flood Zone: Alternating Approximate / Detailed
Pocahontas County, WV
HEC-RAS Version: RAS 6.1
Vertical Datum: NAVD88
Projection: NAD 1983 StatePlane West Virginia S FIPS 4702 (US Feet)
Terrain: 1-meter LIDAR (FEMA Region III 3DEP collected 2016-2018)
Land Use: 2019 NLCD
Hydrologic Method:
WV SIR2010-5033 regression equations
Model Notes:
Zone AE: 189 - 5498
Zone A: 5626 - 95568
END DESCRIPTION:
DSS File=dss
DSS Export Rating Curves= 0
DSS Export Rating Curve Sorted= 0
DSS Export Volume Flow Curves= 0
DXF OffsetX= 0
DXF OffsetY= 0
DXF ScaleX= 0
DXF ScaleY= 0

--- WFGRNBRRRV.p01 (plan) ---

Plan Title=Floodplain
Program Version=6.10
Short Identifier=Floodplain
Geom File=g01
Flow File=f01
Subcritical Flow
K Sum by GR= 0
Std Step Tol= 0.01
Critical Tol= 0.01
Num of Std Step Trials= 20
Max Error Tol= 0.3
Flow Tol Ratio= 0.001
Split Flow NTrial= 30
Split Flow Tol= 0.02
Split Flow Ratio= 0.02
Log Output Level= 0
Friction Slope Method= 1
Unsteady Friction Slope Method= 2
Unsteady Bridges Friction Slope Method= 1
Parabolic Critical Depth
Global Vel Dist= 0 , 0 , 0
Global Log Level= 0
CheckData=True
Encroach Param=-1 ,5,5, 2
Encroach River=WFGRNBRRRV
Encroach Reach=Main
Encroach Node=5498
       1     310     450
Encroach Node=5097
       1     340     515
Encroach Node=4845
       1     599     680
Encroach Node=4513
       1     580     663
Encroach Node=4249
       1     475     570
Encroach Node=3962
       1     345     465
Encroach Node=3628
       1     350     525
Encroach Node=3388
       1     210     380
Encroach Node=3290
       1     270     405
Encroach Node=3174
       1     276     399
Encroach Node=2859
       1     252     400
Encroach Node=2772
       1     460     571
Encroach Node=2732
       1   470.7     615
Encroach Node=2617
       1     520     655
Encroach Node=2358
       1     680   800.9
Encroach Node=2047
       1     873     975
Encroach Node=1692
       1  1007.6    1200
Encroach Node=1390
       1  1009.5    1325
Encroach Node=1136
       1    1090    1478
Encroach Node=775
       1  1525.1    1873
Encroach Node=539
       1  1480.9  1664.1
Encroach Node=467
       1 1601.17  1697.4
Encroach Node=189
       1    1742    2040
Computation Interval=0.1SEC
Output Interval=1SEC
Instantaneous Interval=Max Profile
Mapping Interval=1HOUR
Computation Time Step Use Courant=        0
Computation Time Step Use Time Series=    0
Computation Time Step Count To Double=0
Computation Time Step Max Doubling=0
Computation Time Step Max Halving=0
Computation Time Step Residence Courant=0
Run HTab= 0
Run UNet= 0
Run Sediment= 0
Run PostProcess= 0
Run WQNet= 0
Run RASMapper=-1
UNET Theta= 0
UNET Theta Warmup= 0
UNET ZTol= 0
UNET ZSATol= 0
UNET MxIter= 0
UNET Max Iter WO Improvement= 0
UNET MaxInSteps= 0
UNET DtIC= 0
UNET DtMin= 0
UNET MaxCRTS= 0
UNET WFStab= 0
UNET SFStab= 0
UNET WFX= 1
UNET SFX= 1
UNET Gravity=32.174
UNET 1D Methodology=Finite Difference
UNET DSS MLevel= 1
UNET Pardiso=0
UNET DZMax Abort= 0
UNET Use Existing IB Tables= 0
UNET Froude Reduction=False
UNET Froude Limit= 0
UNET Froude Power= 0
UNET D1 Cores= 0
UNET WindReference=Eulerian
UNET WindDragFormulation=Hsu (1988)
UNET D2 Coriolis=0
UNET D2 Cores= 0
UNET D2 Theta= 1
UNET D2 Theta Warmup= 1
UNET D2 Z Tol= 0.01
UNET D2 Volume Tol= 0.01
UNET D2 Max Iterations= 20
UNET D2 Equation= 0
UNET D2 RampUpFraction=0.1
UNET D2 TimeSlices= 1
UNET D2 Turbulence Formulation=Non-Conservative (original)
UNET D2 Eddy Viscosity=0.3
UNET D2 Transverse Eddy Viscosity=0.1
UNET D2 Smagorinsky Mixing=0
UNET D2 BCVolumeCheck=0
UNET D2 Cores=0
UNET D2 SolverType=PARDISO (Direct)
UNET D2 Minimum Iterations= 2147483647
UNET D2 Maximum Iterations= 2147483647
UNET D2 Restart Number= 10
UNET D2 Relaxation Coeff=1.3
UNET D2 SOR Precondition Iterations= 10
UNET D2 ILUT Maximum Fill= 8
UNET D2 ILUT Tolerance=1E-08
UNET D1D2 MaxIter= 0
UNET D1D2 ZTol=0.01
UNET D1D2 QTol=0.1
UNET D1D2 MinQTol=1
DSS File=dss
Write IC File= 0
Write IC File at Fixed DateTime=0
Write IC File at Sim End=0
Echo Input=False
Echo Parameters=False
Echo Output=False
Write Detailed= 0
HDF Write Warmup=0
HDF Write Time Slices=0
HDF Flush=0
HDF Compression= 1
HDF Chunk Size= 1
HDF Spatial Parts= 1
HDF Use Max Rows=0
HDF Fixed Rows= 1
Calibration Method= 0
Calibration Iterations= 20
Calibration Max Change=0.05
Calibration Tolerance=0.2
Calibration Maximum=1.5
Calibration Minimum=0.5
Calibration Optimization Method= 1
WQ AD Non Conservative
WQ ULTIMATE=-1
WQ Max Comp Step=1HOUR
WQ Output Interval=15MIN
WQ Output Selected Increments= 0
WQ Output face flow=0
WQ Output face velocity=0
WQ Output face area=0
WQ Output face dispersion=0
WQ Output cell volume=0
WQ Output cell surface area=0
WQ Output cell continuity=0
WQ Output cumulative cell continuity=0
WQ Output face conc=0
WQ Output face dconc_dx=0
WQ Output face courant=0
WQ Output face peclet=0
WQ Output face adv mass=0
WQ Output face disp mass=0
WQ Output cell mass=0
WQ Output cell source sink temp=0
WQ Output nsm pathways=0
WQ Output nsm derived pathways=0
WQ Create Restart=0
WQ Fixed Restart=0
WQ System Summary=0
WQ Write To DSS=0
Sorting and Armoring Iterations= 10
XS Update Threshold= 0.02
Bed Roughness Predictor= 0
Hydraulics Update Threshold= 0.02
Energy Slope Method= 1
Volume Change Method= 1
Sediment Retention Method= 0
Sediment TS Multiplier= 1
Warm Up Method= 0
XS Weighting Method= 0
Number of US Weighted Cross Sections= 1
Number of DS Weighted Cross Sections= 1
Upstream XS Weight=0
Main XS Weight=1
Downstream XS Weight=0
Number of DS XS's Weighted with US Boundary= 1
Upstream Boundary Weight= 1
Weight of XSs Associated with US Boundary= 0
Number of US XS's Weighted with DS Boundary= 1
Downstream Boundary Weight= 0.5
Weight of XSs Associated with DS Boundary= 0.5
Percentile Method= 0
Sediment Output Level= 3
Mass or Volume Output= 0
Output Increment Type= 1
Profile and TS Output Increment= 1
Transport Output Increment 1
XS Output Flag= 0
XS Output Increment= 10
Read HDF5 Sediment Hotstart= 0
Sediment Hotstart Type= 0
Write Gradation File= 0
Read Gradation Hotstart= 0
Write HDF5 File= 1
Write Binary Output= 1
Write DSS Sediment File= 0
DSS Sediment Output Type= 1
SV Curve= 0
Specific Gage Flag= 0
Subcell Erosion Methods= 0
Subcell Deposition Methods= 0
Advection Scheme= 1
Matrix Solver= 0
Implicit Weighting Factor= 1
Maximum Outer Loop Convergence Iterations= 5
Convergence Maximum Absolute= 0.001
Convergence RMSE= 0.0001
Grain Fractions Max Abs Error= 0.001
Max Subgrid Regions= 1
Max Subgrid Length Scale= 3.402823E+38
Initial Layer Thickness= 3.402823E+38
Min Layer Thickness= 3.402823E+38
Max Layer Thickness= 3.402823E+38
Number of Layers= 5

--- WFGRNBRRRV.f01 (steady flow) ---

Flow Title=Flow
Program Version=6.10
Number of Profiles= 7
Profile Names=01pct,FW,10pct,04pct,02pct,0_2pct,01plus
River Rch & RM=WFGRNBRRRV,Main            ,96455
    1070    1070     579     761     910    1480    1580
River Rch & RM=WFGRNBRRRV,Main            ,91059
    1190    1190     645     846    1010    1640    1760
River Rch & RM=WFGRNBRRRV,Main            ,86461
    1590    1590     876    1140    1360    2180    2360
River Rch & RM=WFGRNBRRRV,Main            ,82557
    2080    2080    1150    1500    1780    2830    3070
River Rch & RM=WFGRNBRRRV,Main            ,73561
    2720    2720    1530    1970    2340    3690    4020
River Rch & RM=WFGRNBRRRV,Main            ,68768
    3030    3030    1710    2200    2600    4100    4470
River Rch & RM=WFGRNBRRRV,Main            ,61024
    3420    3420    1930    2490    2940    4610    5050
River Rch & RM=WFGRNBRRRV,Main            ,53856
    4130    4130    2350    3020    3560    5560    6110
River Rch & RM=WFGRNBRRRV,Main            ,43666
    7060    7060    4110    5210    6110    9400   10400
River Rch & RM=WFGRNBRRRV,Main            ,13711
    8210    8210    4810    6080    7110   10900   12100
Boundary for River Rch & Prof#=WFGRNBRRRV,Main            , 1
Up Type= 0
Dn Type= 3
Dn Slope=0.01
Boundary for River Rch & Prof#=WFGRNBRRRV,Main            , 2
Up Type= 0
Dn Type= 3
Dn Slope=0.01
Boundary for River Rch & Prof#=WFGRNBRRRV,Main            , 3
Up Type= 0
Dn Type= 3
Dn Slope=0.01
Boundary for River Rch & Prof#=WFGRNBRRRV,Main            , 4
Up Type= 0
Dn Type= 3
Dn Slope=0.01
Boundary for River Rch & Prof#=WFGRNBRRRV,Main            , 5
Up Type= 0
Dn Type= 3
Dn Slope=0.01
Boundary for River Rch & Prof#=WFGRNBRRRV,Main            , 6
Up Type= 0
Dn Type= 3
Dn Slope=0.01
DSS Import GetInterval= 0
DSS Import GetPeak= 0
DSS Import FillOption= 0

--- WFGRNBRRRV.g01 (geometry) ---

Geom Title=Geometry
Program Version=6.10

River Reach=WFGRNBRRRV      ,Main
Reach XY= 30
2317358.30201538626228.0127051092314872.67692347623634.868933558
2315365.40100364621770.3549460622312867.38401805617977.459972814
2314824.89913189615212.0580233042314661.77314581609968.338851973
2313153.13213421 609790.977001982312165.67511964607077.578885481
2309803.02006805606275.9420373142311266.24614422602464.352875724
2309530.38609889595204.2958735672307705.50785889592408.081977814
2308952.10805596591215.4770795552307194.12896039590216.160836726
2308176.01905698588664.1898593162306349.68314272588002.593085393
2306697.63585889586526.7659845652305234.24311639  585318.3720759
2306024.29402973582094.6078541432304210.54896955 581012.38003172
2304222.08109872578664.103888392 2305317.9749043578193.201943055
2303251.11191206575904.5569140612304426.60595214574188.844138145
2302969.63412856 572485.186128142305250.28507905571129.578931227
 2303252.4888778570633.2488871372303949.30211672568732.927884638
2302228.12084781568593.8310499792302501.37194172564205.967122316

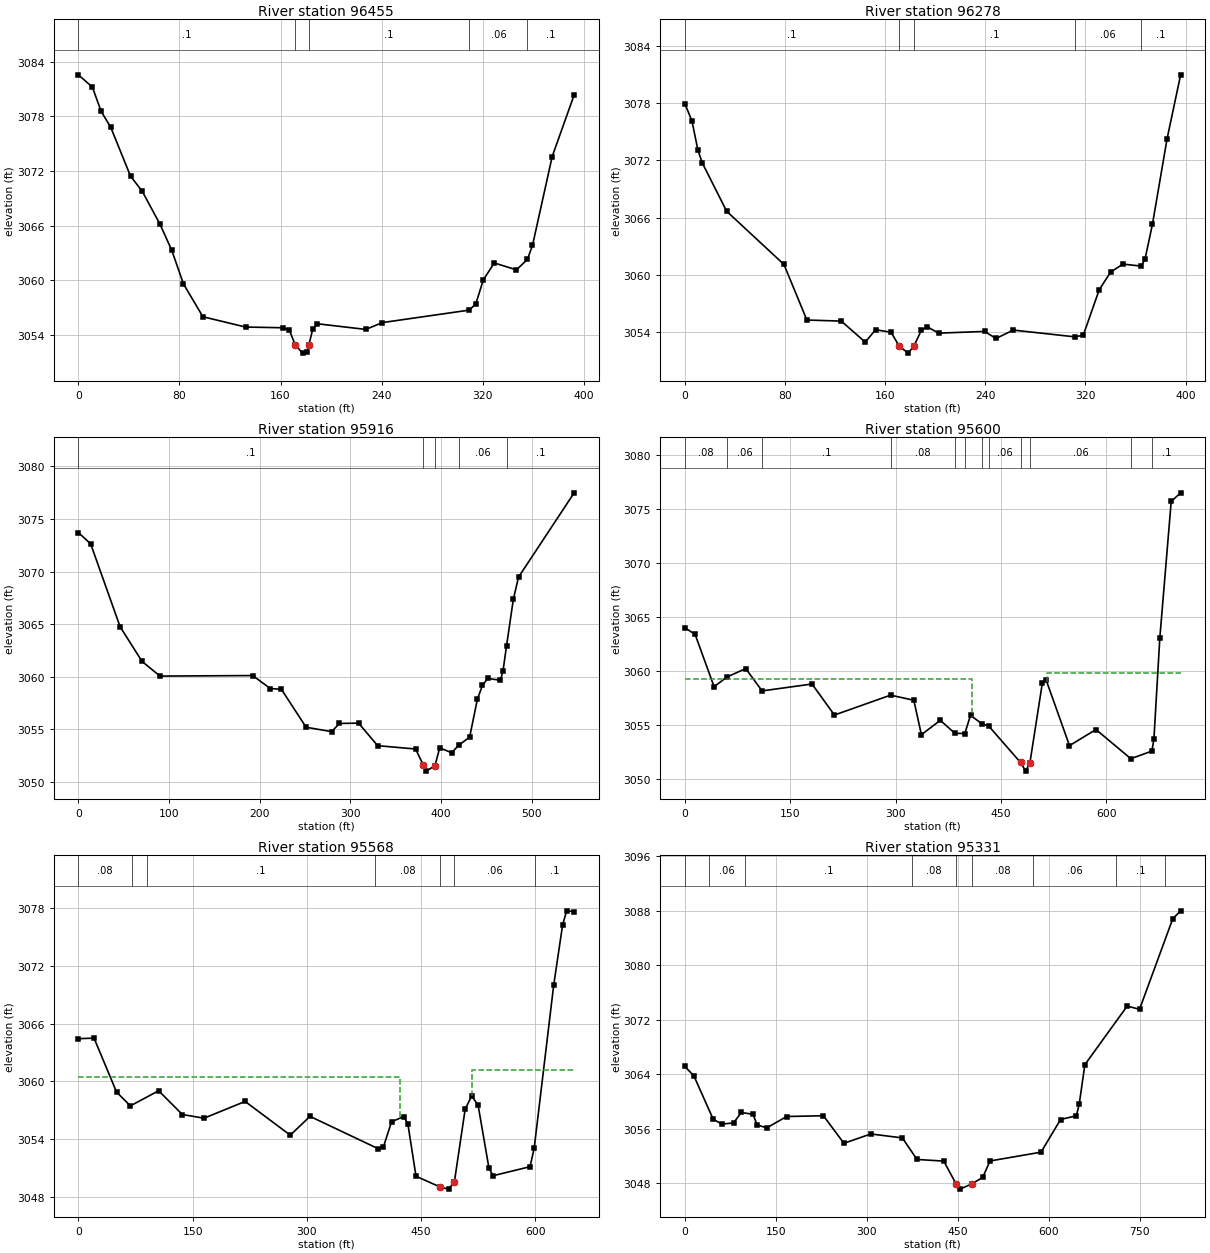
Type RM Length L Ch R = 1 ,96455   ,150.7,176.8,160.6
XS GIS Cut Line= 2
2317503.66927447626129.4712425142317166.43239379626330.055263963
#Sta/Elev= 30
       0 3082.54    11.1  3081.2      18 3078.55    25.7 3076.77    41.3 3071.43
    50.6 3069.76    64.6 3066.16    73.9 3063.31    83.2 3059.61    98.6 3056.01
   132.4 3054.88   162.3  3054.8     167 3054.54   171.6 3052.95   177.4 3052.02
   180.9 3052.19  182.51 3052.96   185.6  3054.7   189.1 3055.24   227.5 3054.62
   240.6 3055.37   309.5 3056.74   314.6 3057.45   320.5 3060.06   329.2 3061.91
   346.7 3061.15   355.4  3062.3   359.4 3063.83     375 3073.58392.3808 3080.34
#Mann= 5 ,-1,0
       0      .1       0   171.6    .045       0  182.51      .1       0
   309.5     .06       0   355.4      .1       0
Bank Sta=171.6,182.51
XS Rating Curve= 0 ,0
Exp/Cntr(USF)=0,0
Exp/Cntr=0.3,0.1

Type RM Length L Ch R = 1 ,96278   ,284.2,361.4,278.3
XS GIS Cut Line= 2
2317425.35360076 626006.403755252317079.32618527626198.996381422
#Sta/Elev= 30
       0 3077.93     5.7 3076.13    10.5 3073.05    13.9 3071.75    33.4 3066.68
    79.2 3061.11    97.5  3055.3     125 3055.19   144.1 3052.99   152.4 3054.29
   164.7 3054.02   171.4 3052.55   178.4 3051.84  183.03 3052.59     189 3054.24
   193.6 3054.59   202.8 3053.93   239.4 3054.11   248.6 3053.37   262.3 3054.25
   311.7 3053.54   318.3 3053.72     331 3058.47   340.1 3060.31   349.9 3061.15
   364.6 3060.94   367.6 3061.69   373.5 3065.31   385.2 3074.26396.0138 3080.94
#Mann= 5 ,-1,0
       0      .1       0   171.4    .045       0  183.03      .1       0
   311.7     .06       0   364.6      .1       0
Bank Sta=171.4,183.03
XS Rating Curve= 0 ,0
Exp/Cntr(USF)=0,0
Exp/Cntr=0.3,0.1

Type RM Length L Ch R = 1 ,95916   ,225.7,238.1,216.7
XS GIS Cut Line= 3
2317362.22157807625857.7638031012317165.63325426625855.366384518
2316899.51979154626083.121149908
#Sta/Elev= 30
       0 3073.71    13.6 3072.63    46.1 3064.75    70.3 3061.46    90.1 3060.07
   192.3 3060.12   211.7 3058.89     224 3058.81   251.2 3055.21   279.4 3054.79
     288 3055.57   309.1  3055.6   330.1 3053.46     372 3053.14   380.5 3051.62
   383.9 3051.04   393.3 3051.56   398.6 3053.25   411.7 3052.79   419.7 3053.51
   431.6 3054.27   440.1 3057.86   445.7 3059.18   451.6 3059.85   465.6 3059.67
   468.4 3060.57   472.3 3062.95   479.8 3067.37   485.5 3069.47546.8723 3077.48
#Mann= 5 ,-1,0
       0      .1       0   380.5    .045       0   393.3      .1       0
   419.7     .06       0   472.3      .1       0
Bank Sta=380.5,393.3
XS Rating Curve= 0 ,0
Exp/Cntr(USF)=0,0
Exp/Cntr=0.3,0.1

Type RM Length L Ch R = 1 ,95600   ,105.1,110.1,110.7
XS GIS Cut Line= 4
2317125.94264086625460.072279414 2317042.3906901625622.800368467
2316820.37333686625869.6455935092316635.37505342625916.585456472
#Sta/Elev= 30
       0 3063.98    14.7 3063.36    41.7 3058.52      603059.417    86.7  3060.2
     1103058.133   181.1 3058.77     213  3055.9  292.92 3057.74     326 3057.27
   336.8 3054.08   363.7 3055.41   384.4 3054.21   398.6 3054.19   406.7 3055.87
  422.923055.091  432.923054.861   477.9 3051.51   485.3 3050.71   491.3 3051.49
   508.9 3058.84   514.3 3059.15   547.6 3053.07   585.3 3054.56  634.923051.859
  664.923052.563   667.8  3053.7   676.2 3063.05   692.4 3075.66   705.8 3076.46
#Mann= 12 ,-1,0
       0     .08       0      60     .06       0     110      .1       0
  292.92     .08       0   384.4    .045       0   398.6     .08       0
  422.92      .1       0  432.92     .06       0   477.9    .045       0
   491.3     .06       0  634.92     .08       0  664.92      .1       0
#XS Ineff= 2 , 0
           409.3 3059.28  515.61         3059.83
Permanent Ineff=
       F       F
Bank Sta=477.9,491.3
XS Rating Curve= 0 ,0
Exp/Cntr=0.3,0.1

Type RM Length L Ch R = 1 ,95568   ,211.8,237.4,255.4
XS GIS Cut Line= 2
2317127.60618297625447.8367568192316640.85437402 625879.87615314
#Sta/Elev= 30
       0 3064.44    20.6  3064.5    50.2  3058.9    68.3 3057.47   105.4 3059.04
   136.6 3056.57     165 3056.19   218.9 3057.93   278.2 3054.43   304.1 3056.38
   393.7 3053.02   400.4 3053.19   411.1 3055.82   427.1 3056.36   432.5 3055.62
   443.2 3050.17   475.2 3049.04   485.9 3048.83   493.6 3049.58   507.7 3057.11
   516.2  3058.5   524.7 3057.55   538.9 3051.04   544.3 3050.22   592.9 3051.16
   598.3 3053.06   623.9 3069.97   635.7 3076.28     641 3077.71   650.8 3077.63
#Mann= 7 ,-1,0
       0     .08       0      70     .06       0      90      .1       0
     390     .08       0   475.2    .045       0   493.6     .06       0
     600      .1       0
#XS Ineff= 2 , 0
          422.76 3060.43  516.23         3061.22
Permanent Ineff=
       F       F
Bank Sta=475.2,493.6
XS Rating Curve= 0 ,0
Exp/Cntr(USF)=0,0
Exp/Cntr=0.3,0.1

Type RM Length L Ch R = 1 ,95331   ,77.8,80.5,83.7
XS GIS Cut Line= 4
2317099.90444566625447.3730436822316916.27541463625592.660012275
2316520.31499966625562.8982817372316361.19333696625659.056391847
#Sta/Elev= 30
       0 3065.15      15 3063.77    46.7 3057.43    60.9 3056.69    80.3 3056.87
    93.2  3058.4   112.5 3058.13     119 3056.59   134.9 3056.14     168 3057.81
   228.5 3057.92   262.3 3053.88   306.5 3055.25   358.6 3054.67   382.7 3051.51
   426.8 3051.27   446.9 3047.97   453.9 3047.16   473.4 3047.96     491 3048.87
     503 3051.29   587.2 3052.58   619.3 3057.37   645.4 3057.92   650.1 3059.64
   659.4 3065.41   729.1    3074   749.5 3073.53   804.3 3086.82   817.2 3087.97
#Mann= 9 ,-1,0
       0     .08       0      40     .06       0     100      .1       0
  374.15     .08       0   446.9    .045       0   473.4     .08       0
  574.15     .06       0  711.23      .1       0  791.23     .12       0
Bank Sta=446.9,473.4
XS Rating Curve= 0 ,0
Exp/Cntr(USF)=0,0
Exp/Cntr=0.3,0.1

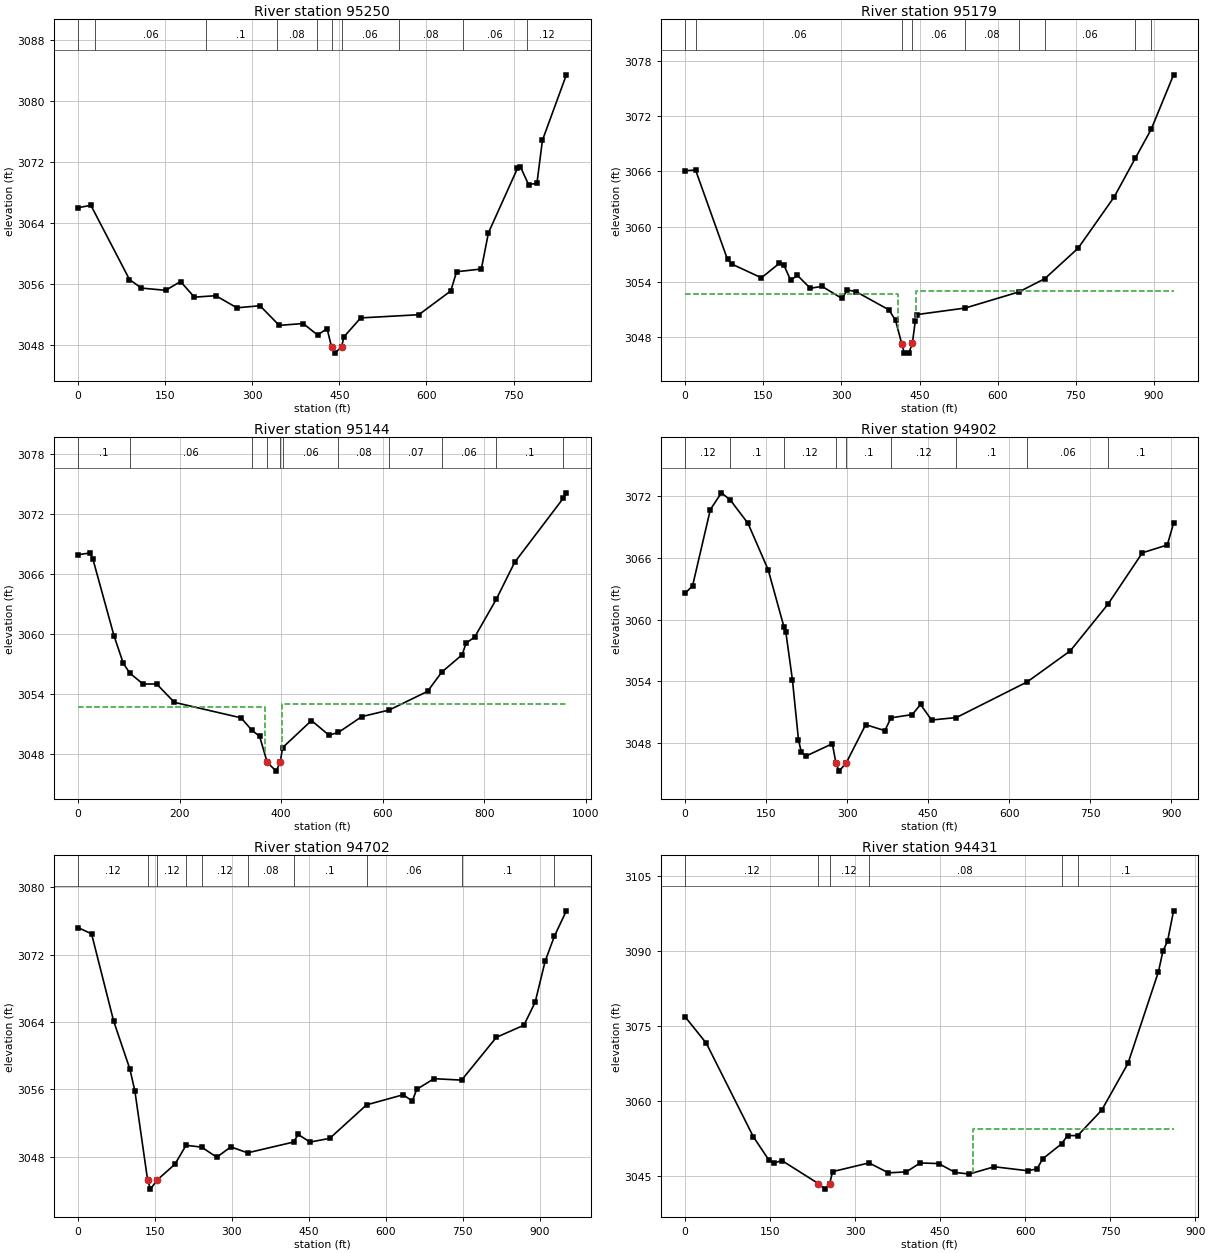
Type RM Length L Ch R = 1 ,95250   ,70.2,71.6,73.8
BEGIN DESCRIPTION:
xs 4
END DESCRIPTION:
XS GIS Cut Line= 4
2317096.13662869625416.1867948332316828.80808587625534.256901243
2316536.97442663625460.7415519692316329.79480595625596.633561234
#Sta/Elev= 30
       0 3066.01    22.3 3066.32    88.7 3056.57   109.3 3055.44     151 3055.15
   176.6  3056.3   200.5 3054.25   237.3 3054.44   273.7 3052.85   313.5 3053.12
   346.5 3050.54   387.8 3050.78   412.5 3049.28     429  3050.1   436.6 3047.71
   441.9 3046.89   453.8 3047.68   457.9 3049.02   486.8 3051.52   586.9 3051.94
     642 3055.07   651.9 3057.59   694.6 3057.95   706.8 3062.71   756.8 3071.18
   761.7 3071.42   775.9 3069.05   790.3 3069.22   799.8 3074.88     841 3083.48
#Mann= 10 ,-1,0
       0     .08       0      30     .06       0     220      .1       0
  342.24     .08       0  412.24     .06       0   436.6    .045       0
   453.8     .06       0  552.24     .08       0  663.19     .06       0
  773.19     .12       0
Bank Sta=436.6,453.8
XS Rating Curve= 0 ,0
Exp/Cntr(USF)=0,0
Exp/Cntr=0.5,0.3

Type RM Length L Ch R = 1 ,95179   ,33.5,34.3,34.7
BEGIN DESCRIPTION:
xs 3
END DESCRIPTION:
XS GIS Cut Line= 6
 2317087.4793181625413.6476974542316895.77735006625491.748499246
2316611.77443446625401.2225698962316499.94828644625385.247405893
2316420.07246642625413.6476974542316217.72038905625530.798900142
#Sta/Elev= 30
       0 3066.06      20 3066.13    81.3 3056.43      90 3055.92   146.4 3054.44
   180.7 3056.01   189.4 3055.84   202.3 3054.19   215.5  3054.7   240.2 3053.31
   262.8 3053.51     301  3052.2   311.5 3053.13   328.3 3052.93   391.3 3050.96
   403.9 3049.81  415.65  3047.3   420.7 3046.28   429.1 3046.27  436.08 3047.32
   441.7 3049.75   445.9 3050.46   537.4 3051.16   640.6 3052.91   690.4 3054.35
   754.4 3057.66   823.8 3063.24   864.3 3067.44   894.4 3070.53   937.5 3076.46
#Mann= 9 ,-1,0
       0     .08       0      20     .06       0  415.65    .045       0
  436.08     .06       0   537.4     .08       0   640.6     .07       0
   690.4     .06       0   864.3      .1       0   894.4     .06       0
#XS Ineff= 2 , 0
             408 3052.63     443         3052.98
Permanent Ineff=
       F       F
Bank Sta=415.65,436.08
XS Rating Curve= 0 ,0
Exp/Cntr(USF)=0,0
Exp/Cntr=0.5,0.3

Type RM Length L Ch R = 1 ,95144   ,257.8,242.1,227.8
BEGIN DESCRIPTION:
xs 2
END DESCRIPTION:
XS GIS Cut Line= 6
2317053.75397187 625369.272241892316869.15207673625450.923080127
2316558.52388778625346.1970049972316466.22294021625349.747041442
2316391.67217486625379.9223512252316168.01987882625509.498681471
#Sta/Elev= 30
       0 3067.91    23.6 3068.08    29.4 3067.47    70.9 3059.81    89.2 3057.05
   102.3 3056.05   128.3 3054.97   154.8 3054.98   189.8 3053.14   321.1 3051.59
   342.2 3050.36   357.6 3049.74   372.6 3047.13   390.3 3046.26   398.33047.199
   402.9 3048.61   459.7 3051.32   494.1 3049.86   512.7 3050.13   558.6 3051.71
   612.6 3052.37   688.2 3054.24   716.3 3056.17   756.3  3057.9   764.1 3059.07
     781 3059.67   823.6 3063.46   859.6 3067.14   955.3 3073.55   961.5  3074.1
#Mann= 11 ,-1,0
       0      .1       0   102.3     .06       0   342.2      .1       0
   372.6    .045       0   398.3      .1       0   402.9     .06       0
   512.7     .08       0   612.6     .07       0   716.3     .06       0
   823.6      .1       0   955.3     .06       0
#XS Ineff= 2 , 0
             368 3052.63     402         3052.98
Permanent Ineff=
       F       F
Bank Sta=372.6,398.3
XS Rating Curve= 0 ,0
Exp/Cntr(USF)=0,0
Exp/Cntr=0.5,0.3

Type RM Length L Ch R = 1 ,94902   ,208.8,200.2,192.1
BEGIN DESCRIPTION:
xs 1
END DESCRIPTION:
XS GIS Cut Line= 3
2316953.56140585625086.481592027 2316543.6576402 625182.27431987
2316167.16994241625485.246668394
#Sta/Elev= 30
       0 3062.57    13.7 3063.28    46.6 3070.68    67.1 3072.31    83.6 3071.61
   116.4 3069.34   153.7 3064.84   183.2 3059.24   186.3 3058.82   198.6 3054.15
   209.8 3048.33     215 3047.15   223.2 3046.75   272.5 3047.96  279.01 3046.11
   284.9  3045.3   298.4 3046.12   334.2 3049.81   369.7 3049.23     381 3050.47
   420.4 3050.79   435.7 3051.77   456.2 3050.26   502.1  3050.5   633.2 3053.96
   712.9 3056.97   782.9 3061.51   846.4 3066.49   892.6 3067.25   904.2 3069.36
#Mann= 9 ,-1,0
       0     .12       0    83.6      .1       0   183.2     .12       0
  279.01    .045       0   298.4      .1       0     381     .12       0
   502.1      .1       0   633.2     .06       0   782.9      .1       0
Bank Sta=279.01,298.4
XS Rating Curve= 0 ,0
Exp/Cntr(USF)=0,0
Exp/Cntr=0.3,0.1

Type RM Length L Ch R = 1 ,94702   ,269.7,270.9,274.9
XS GIS Cut Line= 3
2316754.30839773624885.5797762452316221.62542914625235.435867911
2316126.30695059625535.236445698
#Sta/Elev= 30
       0 3075.21    26.5 3074.47    69.6 3064.09   101.3 3058.38     111 3055.77
  135.77 3045.21   141.3 3044.14   154.3 3045.22   189.2 3047.11   210.6 3049.35
     241 3049.13   270.5 3047.93     298 3049.16   330.5 3048.45   420.1 3049.73
   429.2 3050.63   452.4 3049.73   490.7 3050.17   562.5 3054.15   633.8 3055.35
   651.7  3054.6   660.1 3055.99     694 3057.26   747.7 3057.09   815.4 3062.17
   869.1 3063.61     891 3066.33   910.5 3071.21   928.7 3074.21   951.9  3077.2
#Mann= 10 ,-1,0
       0     .12       0  135.77    .045       0   154.3     .12       0
   210.6      .1       0     241     .12       0   330.5     .08       0
   420.1      .1       0   562.5     .06       0   747.7      .1       0
   928.7     .06       0
Bank Sta=135.77,154.3
XS Rating Curve= 0 ,0
Exp/Cntr(USF)=0,0
Exp/Cntr=0.3,0.1

Type RM Length L Ch R = 1 ,94431   ,269.5,258,237.1
XS GIS Cut Line= 4
2316666.79999936624657.4899346512316389.61541838624801.983148131
2316072.47644482625043.0482869122315921.49327143 625042.85315867
#Sta/Elev= 30
       0 3076.76    37.3 3071.49   120.2 3052.79   147.3 3048.17   155.9 3047.46
   170.7    3048   235.23043.378   246.5 3042.28     255 3043.36   260.1 3045.78
   324.5 3047.53   358.7 3045.54   390.1 3045.73   414.9 3047.52   447.2  3047.4
   476.5 3045.62   501.4  3045.3   545.5 3046.76   604.2 3045.96   620.9 3046.33
   630.9 3048.34   664.2 3051.34   674.8    3053   692.7 3052.99   735.2 3058.11
   781.5 3067.47   835.2 3085.79   843.2 3089.97   851.2 3091.88   861.9 3097.99
#Mann= 6 ,-1,0
       0     .12       0   235.2    .045       0     255     .12       0
   324.5     .08       0   664.2     .06       0   692.7      .1       0
#XS Ineff= 2 , 0
                             508         3054.32
Permanent Ineff=
       F       F
Bank Sta=235.2,255
XS Rating Curve= 0 ,0
Exp/Cntr(USF)=0,0
Exp/Cntr=0.3,0.1

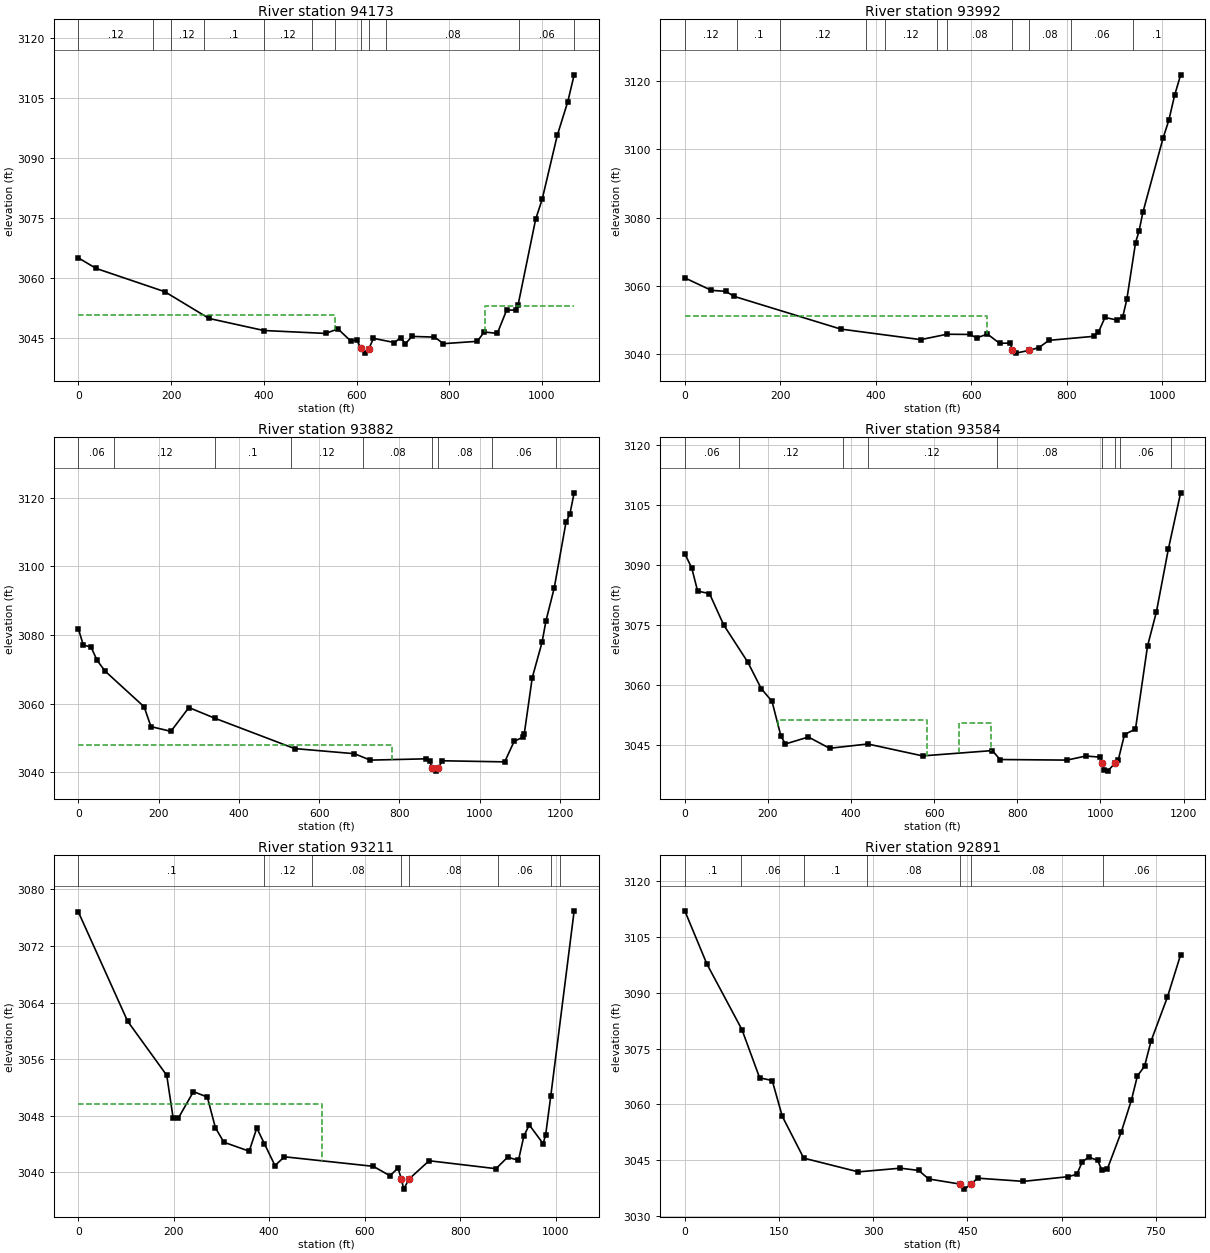
Type RM Length L Ch R = 1 ,94173   ,170.1,181.7,196.3
XS GIS Cut Line= 4
2316720.05054603624330.8865817032316294.04617262624561.638950633
2316196.42017038624753.3409186682315892.89205433 624964.56808715
#Sta/Elev= 30
       0 3064.97    38.4 3062.32   186.4 3056.49     282 3049.78     400 3046.76
   533.3 3046.03   559.9 3047.15   587.2 3044.17   600.7 3044.36   609.7 3042.28
   618.6 3041.09  626.65 3042.22   636.6 3044.79   681.8 3043.74   694.9 3044.93
   705.4 3043.44   719.8 3045.28   768.1 3045.11   787.6 3043.46   860.4 3044.05
   875.4 3046.39   903.7 3046.03   923.8 3051.89   943.9 3051.87   948.4 3053.12
   986.4 3074.67  1000.4 3079.64    1033 3095.68  1055.7 3104.14  1069.4 3110.85
#Mann= 12 ,-1,0
       0     .12       0     160      .1       0     200     .12       0
     270      .1       0     400     .12       0  504.49      .1       0
  554.49     .12       0   609.7    .045       0  626.65     .12       0
  664.49     .08       0  949.61     .06       0 1069.41      .1       0
#XS Ineff= 2 , 0
          554.37 3050.65  877.08         3052.88
Permanent Ineff=
       F       F
Bank Sta=609.7,626.65
XS Rating Curve= 0 ,0
Exp/Cntr(USF)=0,0
Exp/Cntr=0.3,0.1

Type RM Length L Ch R = 1 ,93992   ,103.2,109.7,115.7
XS GIS Cut Line= 3
2316663.95548447624284.495963582 2316311.9729031 624424.84344856
2315817.41509889624861.480068492
#Sta/Elev= 30
       0 3062.34    55.7 3058.69    85.9  3058.4   103.1 3056.94   326.7 3047.35
   494.3 3044.26   549.1 3045.84   597.2 3045.78   611.4 3044.77   634.1 3045.88
   659.6 3043.17   681.6 3043.27  686.03 3041.17   693.5 3040.31   720.2 3041.08
   741.8 3041.92   762.8 3044.05   856.9 3045.23   866.5 3046.42   880.2 3050.76
   905.2    3050   917.5 3050.97     926 3056.03   944.3 3072.67   951.5 3075.99
   959.6  3081.5  1001.9 3103.25    1014 3108.49  1026.1 3115.78  1038.7 3121.79
#Mann= 11 ,-1,0
       0     .12       0     110      .1       0     200     .12       0
  378.93      .1       0  418.93     .12       0  528.93      .1       0
  548.93     .08       0  686.03    .045       0   720.2     .08       0
  808.93     .06       0  938.93      .1       0
#XS Ineff= 2 , 0
          632.79 3051.31
Permanent Ineff=
       F       F
Bank Sta=686.03,720.2
XS Rating Curve= 0 ,0
Exp/Cntr(USF)=0,0
Exp/Cntr=0.3,0.1

Type RM Length L Ch R = 1 ,93882   ,307.4,297.3,287.9
XS GIS Cut Line= 2
2316753.77589226624009.6082834232315759.76568764624742.690809333
#Sta/Elev= 30
       0 3081.84    12.3 3077.11    31.8 3076.45    46.7 3072.61    66.7 3069.46
   163.9 3059.06   180.9 3053.28   230.6  3051.9   275.4 3058.84     340 3055.73
   538.6 3046.88   687.9 3045.38   727.1 3043.51   866.8 3043.89   876.2 3043.17
  880.61 3041.17   891.6  3040.3     897 3041.21   906.6 3043.32  1062.1    3043
  1085.5 3048.97  1107.9 3050.25  1110.7 3051.09  1130.7 3067.54  1155.1 3077.86
    1165  3084.2  1185.4 3093.69  1214.7 3112.81  1224.6 3115.38  1235.1 3121.46
#Mann= 9 ,-1,0
       0     .06       0      90     .12       0     340      .1       0
     530     .12       0     710     .08       0  880.61    .045       0
     897     .08       0    1030     .06       0    1190      .1       0
#XS Ineff= 2 , 0
          781.63 3047.79
Permanent Ineff=
       F       F
Bank Sta=880.61,897
XS Rating Curve= 0 ,0
Exp/Cntr(USF)=0,0
Exp/Cntr=0.3,0.1

Type RM Length L Ch R = 1 ,93584   ,349.2,373.1,393.2
XS GIS Cut Line= 4
2316581.59912468623855.1816980612315821.89132543624455.137857281
2315786.39096098624549.2138230762315699.41506807624637.964734203
#Sta/Elev= 30
       0 3092.92    16.7 3089.33    30.9 3083.56    59.4 3082.94    93.6 3075.09
   151.7 3065.76   183.9 3059.17   209.8 3055.99   231.2 3047.32     242 3045.32
   297.4 3047.06   348.4 3044.24   440.1 3045.32     572 3042.34     740 3043.67
   758.3 3041.43   919.7 3041.29     965 3042.31  1000.1 3042.02  1004.4  3040.5
  1008.7 3038.69  1017.3 3038.53  1034.4 3040.45  1042.9 3041.34  1057.9 3047.69
  1084.3 3049.05  1113.3 3069.83  1134.6 3078.35  1163.2 3093.98  1192.9 3108.14
#Mann= 9 ,-1,0
       0     .06       0     130     .12       0     380      .1       0
     440     .12       0     750     .08       0  1004.4    .045       0
  1034.4     .08       0 1048.04     .06       0 1168.59      .1       0
#XS Ineff= 2 ,-1
  225.25  582.06 3051.28   659.8  737.543050.685
Permanent Ineff=
       F       F
Bank Sta=1004.4,1034.4
XS Rating Curve= 0 ,0
Exp/Cntr(USF)=0,0
Exp/Cntr=0.3,0.1

Type RM Length L Ch R = 1 ,93211   ,315.8,320.1,307.5
XS GIS Cut Line= 2
2316357.94682863623773.5308598242315575.16379249624456.912875503
#Sta/Elev= 30
       0 3076.82   103.2 3061.38   185.3 3053.72   198.8 3047.63   209.4 3047.66
   241.3 3051.42   270.3 3050.65   287.3 3046.31     305 3044.27   358.1    3043
     374 3046.28     390 3044.05   412.1 3040.97   431.9 3042.21   618.3 3040.86
     653 3039.53     670 3040.61   676.7 3039.13     682 3037.64   692.8 3039.05
   735.1 3041.65   875.3 3040.53   899.6 3042.15   922.4 3041.72   933.7 3045.14
     945 3046.72   974.1 3044.06   979.4 3045.33     990 3050.75  1039.1 3076.97
#Mann= 8 ,-1,0
       0      .1       0     390     .12       0     490     .08       0
   676.7    .045       0   692.8     .08       0     880     .06       0
     990      .1       0    1010     .12       0
#XS Ineff= 2 , 0
           510.3 3049.69
Permanent Ineff=
       F       F
Bank Sta=676.7,692.8
XS Rating Curve= 0 ,0
Exp/Cntr(USF)=0,0
Exp/Cntr=0.3,0.1

Type RM Length L Ch R = 1 ,92891   ,565.9,572.2,565.2
XS GIS Cut Line= 3
2315777.27860496623742.1782851322315758.91797284624057.893601838
2315455.46718105624421.367391678
#Sta/Elev= 30
       0 3112.05    35.1 3097.77      91 3080.09   119.2 3067.11   139.2 3066.38
   155.3 3056.74   189.4  3045.5   276.5  3041.8   343.2  3042.8   372.6 3042.19
   388.3  3039.9   438.23038.521   445.4 3037.16     456 3038.53   466.4 3040.11
   539.4 3039.25   610.2  3040.5   624.4 3041.14   633.2 3044.56   643.6 3045.77
   657.6 3044.88   664.4 3042.22   672.7 3042.46     695 3052.45   711.3  3061.1
   720.9 3067.64   732.2 3070.21   742.6 3077.02   768.7 3088.85   789.7 3100.23
#Mann= 7 ,-1,0
       0      .1       0      90     .06       0     190      .1       0
     290     .08       0   438.2    .045       0     456     .08       0
  666.25     .06       0
Bank Sta=438.2,456
XS Rating Curve= 0 ,0
Exp/Cntr(USF)=0,0
Exp/Cntr=0.3,0.1

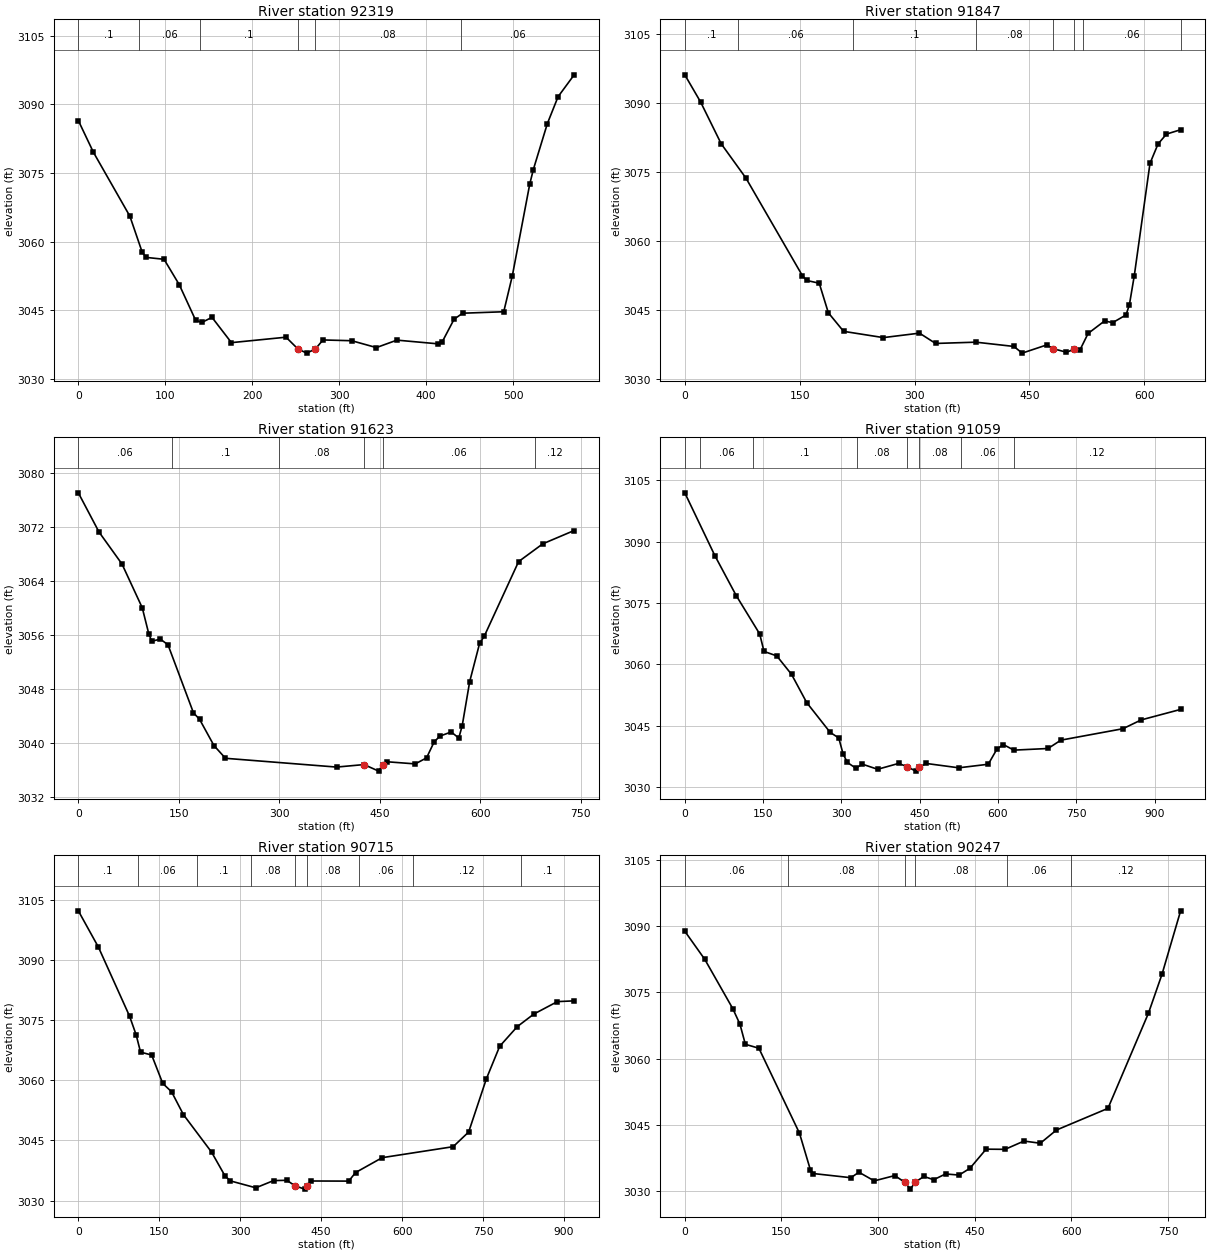
Type RM Length L Ch R = 1 ,92319   ,352,472.5,378.3
XS GIS Cut Line= 2
2315537.88840982623714.9552584812315234.36029377624197.760215012
#Sta/Elev= 30
       0 3086.43    17.4 3079.48    59.3 3065.53    73.5 3057.64    78.2 3056.53
    98.6 3056.12   116.1 3050.57   134.9 3042.81   142.1 3042.32   153.7 3043.44
   176.1 3037.91   238.9  3039.1   252.3 3036.58   262.5 3035.62   272.6 3036.51
   281.4  3038.5   314.5 3038.33   342.8 3036.83   366.4 3038.46   413.7 3037.65
   418.4 3038.03   432.2 3043.03     442 3044.34   489.3 3044.66   499.2 3052.53
   519.2 3072.53   523.3  3075.7   539.5 3085.78   551.8 3091.64   570.3 3096.42
#Mann= 6 ,-1,0
       0      .1       0      70     .06       0     140      .1       0
   252.3    .045       0   272.6     .08       0     440     .06       0
Bank Sta=252.3,272.6
XS Rating Curve= 0 ,0
Exp/Cntr(USF)=0,0
Exp/Cntr=0.3,0.1

Type RM Length L Ch R = 1 ,91847   ,221.8,223.6,224.7
XS GIS Cut Line= 2
2315445.58746225623549.8785637842315012.48301595624030.908502093
#Sta/Elev= 30
       0 3096.11    20.6 3090.22    47.5 3081.14    79.8 3073.69   153.4 3052.53
   159.1 3051.46   175.5 3050.86   187.4 3044.44   207.3 3040.41   259.2 3039.05
   306.4 3040.02   327.4 3037.78     380 3038.06   429.7 3037.13   440.4 3035.68
   472.7 3037.47   480.4 3036.67   498.3 3035.87   507.5 3036.47     516 3036.41
   526.5 3039.95   548.1 3042.68   558.5 3042.29     576 3043.97   580.4 3046.16
   586.8  3052.5   607.3 3076.88   617.8 3081.09   628.8 3083.24   647.3 3084.19
#Mann= 8 ,-1,0
       0      .1       0      70     .06       0     220      .1       0
     380     .08       0   480.4    .045       0   507.5     .08       0
     520     .06       0  647.28     .12       0
Bank Sta=480.4,507.5
XS Rating Curve= 0 ,0
Exp/Cntr(USF)=0,0
Exp/Cntr=0.3,0.1

Type RM Length L Ch R = 1 ,91623   ,537.4,564.4,575
XS GIS Cut Line= 3
2315301.81098622623423.8522699842314881.13166748623853.406679839
2314872.25657637623991.858101197
#Sta/Elev= 30
       0    3077    30.9 3071.19    65.2 3066.45    95.4 3059.98   105.2  3056.1
   109.6 3055.02   122.4 3055.34   133.8  3054.5   171.8 3044.43     181 3043.45
   202.4 3039.58   219.6 3037.69   385.4 3036.39   426.4 3036.76   448.3 3035.79
     454 3036.76   460.3 3037.18   502.8 3036.86   519.7 3037.75     531 3040.11
   539.5 3040.97   556.5 3041.59   567.8 3040.69   572.9 3042.51   584.1 3049.06
   598.9 3054.72   605.7 3055.74   657.1 3066.82   693.2 3069.45     740 3071.42
#Mann= 6 ,-1,0
       0     .06       0     140      .1       0     300     .08       0
   426.4    .045       0     454     .06       0  681.24     .12       0
Bank Sta=426.4,454
XS Rating Curve= 0 ,0
Exp/Cntr(USF)=0,0
Exp/Cntr=0.3,0.1

Type RM Length L Ch R = 1 ,91059   ,331.4,344.1,353.9
XS GIS Cut Line= 2
2315328.43625956623246.3504477292314400.10172917623446.927506877
#Sta/Elev= 30
       0 3101.91    57.6 3086.56    98.5  3076.8   143.5 3067.42   151.7 3063.16
   176.2 3062.06   204.5 3057.55   233.5 3050.66   278.5 3043.37   294.9 3042.02
   303.1 3038.17   311.3 3036.04   327.7 3034.62   339.9 3035.62   369.4 3034.36
   409.5 3035.79   426.6 3034.97   442.2 3033.91   448.73034.895   462.7 3035.78
   524.8 3034.72   581.3 3035.59   597.7 3039.24     610 3040.41   630.5 3039.04
   695.8 3039.44   720.5 3041.48   839.2 3044.27   874.2 3046.42   949.8 3048.99
#Mann= 8 ,-1,0
       0      .1       0      30     .06       0     130      .1       0
     330     .08       0   426.6    .045       0   448.7     .08       0
     530     .06       0     630     .12       0
Bank Sta=426.6,448.7
XS Rating Curve= 0 ,0
Exp/Cntr(USF)=0,0
Exp/Cntr=0.3,0.1

Type RM Length L Ch R = 1 ,90715   ,463.3,467.6,465.6
XS GIS Cut Line= 2
2315312.46109556623146.949427267 2314417.8519114622937.497277007
#Sta/Elev= 30
       0 3102.27    37.3 3093.19    94.9    3076   107.1 3071.34   115.3 3067.02
   135.9 3066.29   156.4 3059.22   172.8 3057.12   194.8 3051.41   246.8 3042.09
   271.4 3036.23   281.3 3034.91   328.9 3033.17   361.8 3034.97   386.5 3035.04
   401.2 3033.69   419.3 3032.84   424.5 3033.72   431.1 3034.87     501 3034.84
   513.8 3036.98   563.1 3040.69   694.6 3043.43   723.3 3047.09   756.2 3060.39
   780.8 3068.48   813.3 3073.37   843.9  3076.5   887.7 3079.62   918.8 3079.81
#Mann= 9 ,-1,0
       0      .1       0     110     .06       0     220      .1       0
     320     .08       0   401.2    .045       0   424.5     .08       0
     520     .06       0     620     .12       0     820      .1       0
Bank Sta=401.2,424.5
XS Rating Curve= 0 ,0
Exp/Cntr(USF)=0,0
Exp/Cntr=0.3,0.1

Type RM Length L Ch R = 1 ,90247   ,375.5,378.3,370.8
XS GIS Cut Line= 2
2315381.68680624622797.2708374262314648.60428033 622562.96843205
#Sta/Elev= 30
       0 3088.88      31  3082.5    74.5 3071.32    85.6  3067.8      94 3063.24
     115 3062.35     178 3043.09   194.8 3034.85     199 3033.95   257.7    3033
   270.3 3034.24     294 3032.28   325.9 3033.48   341.7 3031.94   350.1 3030.41
   357.7 3031.99   371.1 3033.29   386.3 3032.54   404.7 3033.85   425.7  3033.6
   442.5 3035.12   467.7 3039.47   497.1 3039.43   526.5 3041.31   551.8 3040.81
   576.9 3043.81   656.8 3048.72   719.7 3070.31   740.7 3079.12   769.6  3093.5
#Mann= 6 ,-1,0
       0     .06       0     160     .08       0   341.7    .045       0
   357.7     .08       0     500     .06       0     600     .12       0
Bank Sta=341.7,357.7
XS Rating Curve= 0 ,0
Exp/Cntr(USF)=0,0
Exp/Cntr=0.3,0.1