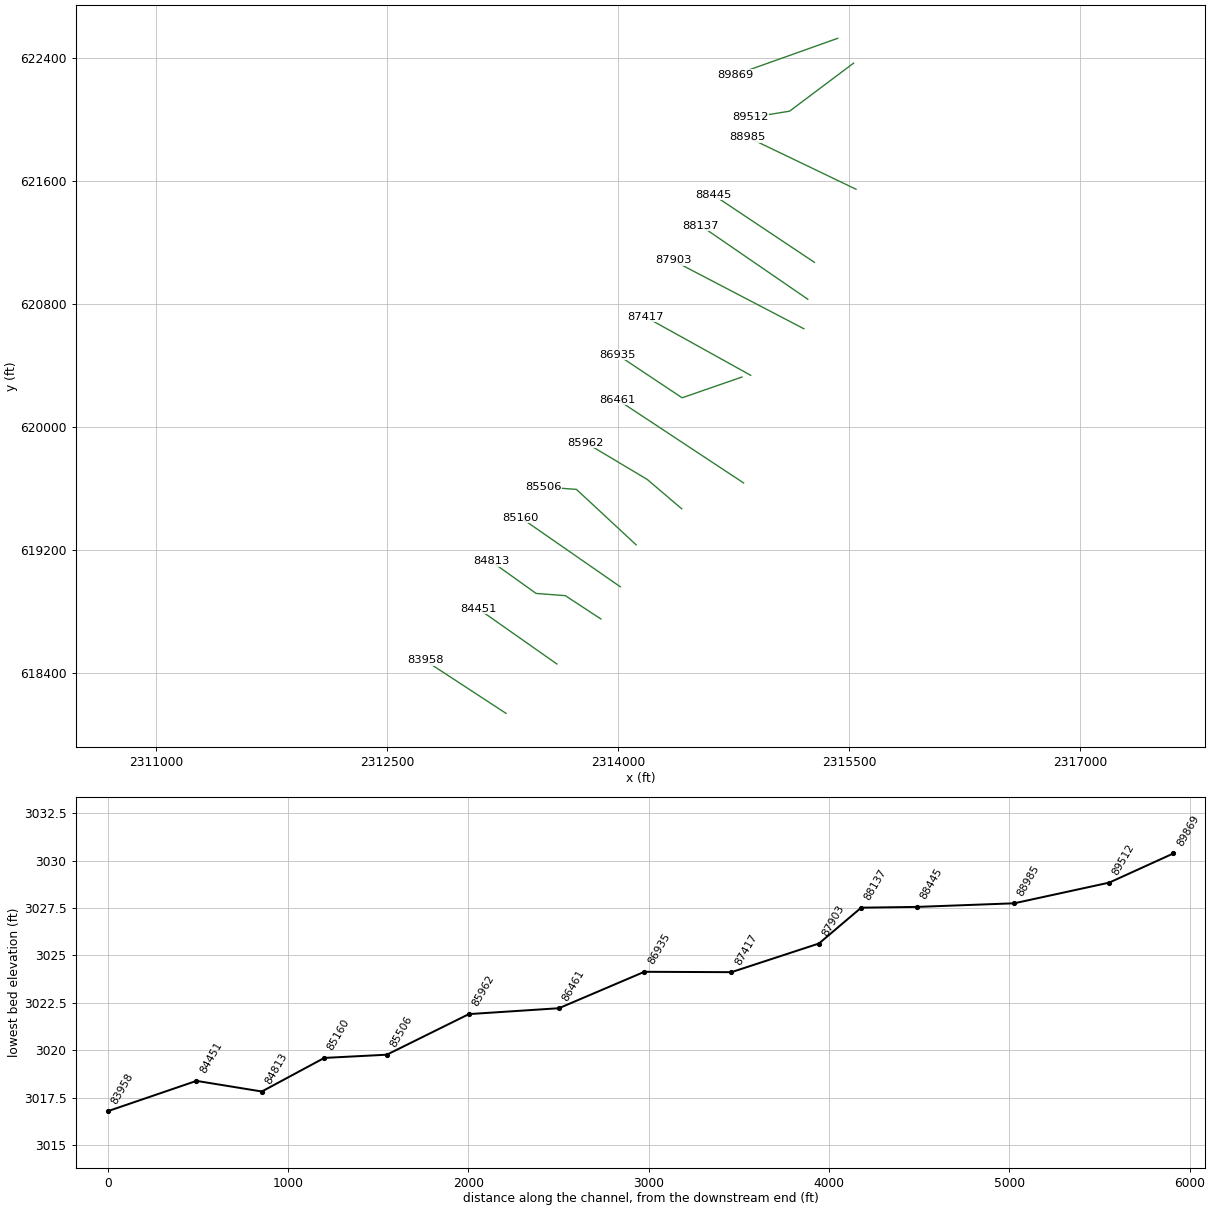
HEC-RAS study WFGRNBRRRV.prj: WFGRNBRRRV

--- WFGRNBRRRV.g01 (geometry) --- (continued)

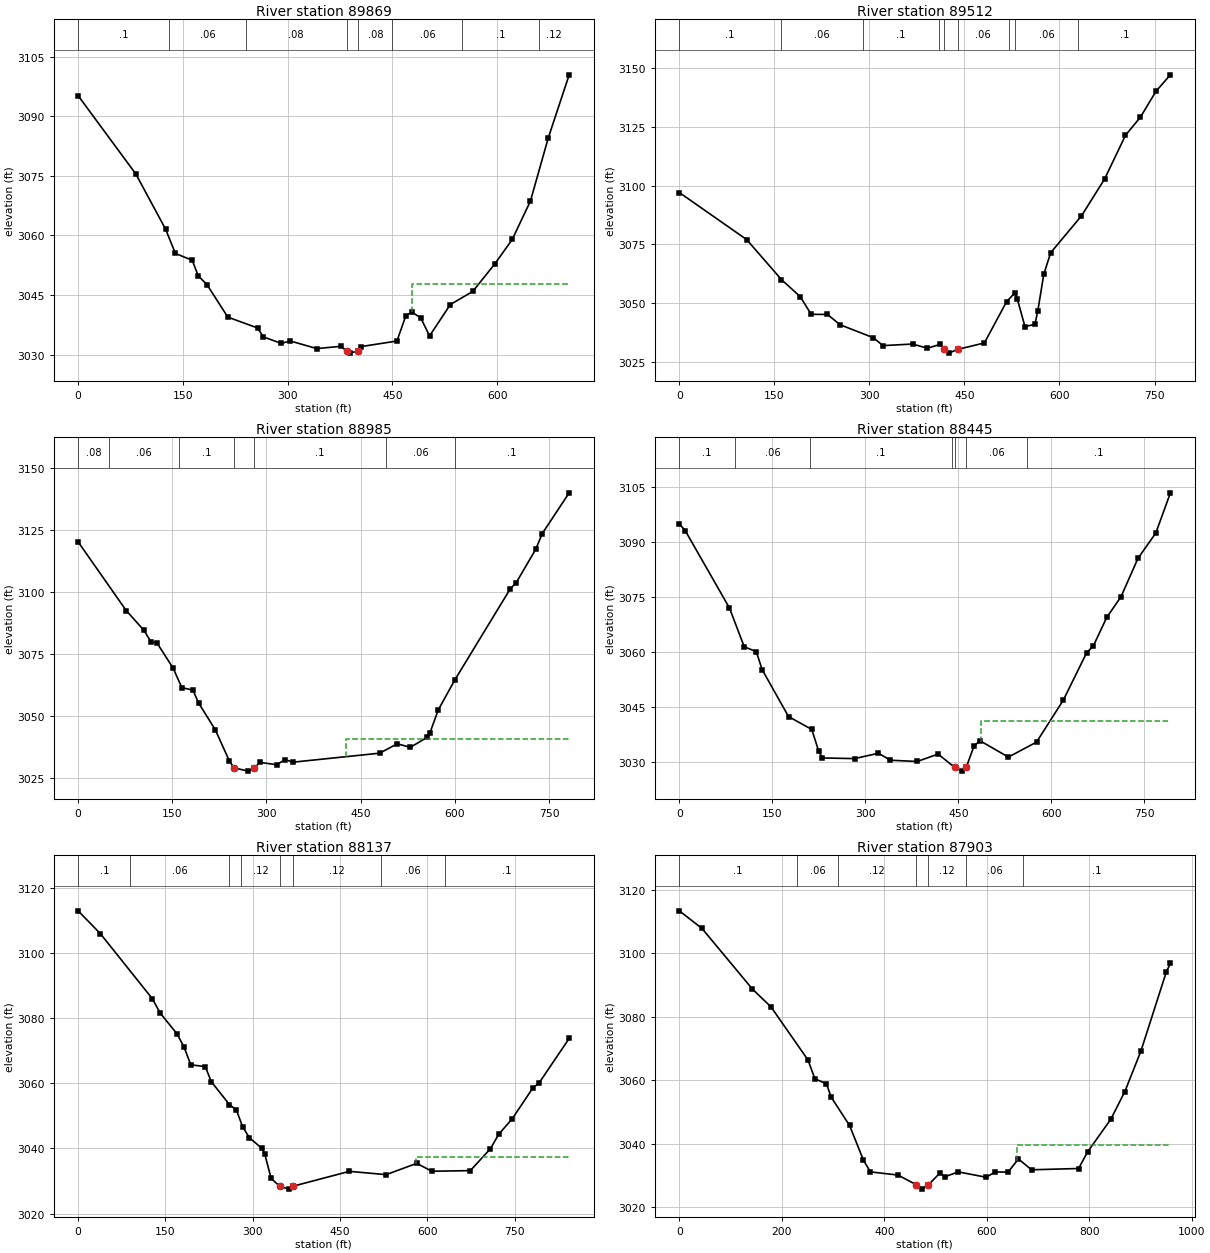
Type RM Length L Ch R = 1 ,89869   ,347.9,356.1,362.5
XS GIS Cut Line= 2
 2315426.0622618622529.2430858222314763.98046479622293.165662224
#Sta/Elev= 30
       0 3095.19    82.7 3075.45   125.2 3061.59   139.3 3055.46   163.4 3053.75
   171.9 3049.85   184.6 3047.59   214.3 3039.44   256.8 3036.72   265.3 3034.47
   290.8 3032.82   303.5 3033.45   341.7 3031.52   375.7 3032.09   384.2 3030.99
   388.5 3030.38   401.2 3030.93   405.6 3032.04   456.4 3033.43   469.1 3039.79
   477.6 3040.72   490.4 3039.26   503.1 3034.71   532.8 3042.61     565 3045.92
   596.5 3052.84   621.4 3058.98   647.5 3068.68     673 3084.55   702.9 3100.42
#Mann= 8 ,-1,0
       0      .1       0     130     .06       0     240     .08       0
   384.2    .045       0   401.2     .08       0     450     .06       0
     550      .1       0     660     .12       0
#XS Ineff= 2 , 0
                          477.75         3047.89
Permanent Ineff=
       F       F
Bank Sta=384.2,401.2
XS Rating Curve= 0 ,0
Exp/Cntr(USF)=0,0
Exp/Cntr=0.3,0.1

Type RM Length L Ch R = 1 ,89512   ,557.8,527.1,493.5
XS GIS Cut Line= 3
2315529.01331871622367.7164275712315113.65905463622055.313220403
2314861.60646703622014.487801285
#Sta/Elev= 30
       0 3097.04   106.2 3077.07   161.2 3060.07   190.9  3052.8   208.1 3045.32
   233.8 3045.27   253.8 3040.88   306.4 3035.37   321.4 3032.03   368.1  3032.7
   391.4 3030.93   411.5 3032.51   418.43030.381   425.2 3028.84   439.5 3030.44
   481.5 3033.16   516.4 3050.63   529.3 3054.36   533.3 3051.98   545.5 3040.14
   561.2 3041.03   565.8 3046.74   575.2 3062.26   586.1 3071.47   634.7 3087.12
   671.2 3102.77   704.2 3121.35   727.9 3129.09   752.2    3140   775.1 3147.03
#Mann= 9 ,-1,0
       0      .1       0     160     .06       0     290      .1       0
     410     .06       0   418.4    .045       0   439.5     .06       0
  519.73      .1       0  529.73     .06       0  629.73      .1       0
Bank Sta=418.4,439.5
XS Rating Curve= 0 ,0
Exp/Cntr(USF)=0,0
Exp/Cntr=0.3,0.1

Type RM Length L Ch R = 1 ,88985   ,545.4,540.3,532.4
XS GIS Cut Line= 2
2315544.98848271621547.6580087562314840.30624836621886.686489262
#Sta/Elev= 30
       0  3120.2    76.7 3092.47     105 3084.49   116.3 3079.73   125.2 3079.59
   151.6 3069.17   165.1 3061.43   182.9 3060.41   191.8 3055.26   218.4 3044.45
   240.6 3032.01   248.33029.053   271.1 3027.75   280.8 3029.07   289.4 3031.28
   316.4 3030.33   329.4 3032.38   342.7 3031.37   480.3 3034.99   508.2 3038.77
   529.1 3037.34   555.8 3041.37   560.2  3043.1   573.5 3052.41   600.1 3064.59
   688.1 3101.21   697.8  3103.8   728.9 3117.25     739 3123.48     782 3139.96
#Mann= 7 ,-1,0
       0     .08       0      50     .06       0     160      .1       0
   248.3    .045       0   280.8      .1       0     490     .06       0
     600      .1       0
#XS Ineff= 2 , 0
                          426.37         3040.65
Permanent Ineff=
       F       F
Bank Sta=248.3,280.8
XS Rating Curve= 0 ,0
Exp/Cntr(USF)=0,0
Exp/Cntr=0.3,0.1

Type RM Length L Ch R = 1 ,88445   ,304.1,308,300.2
XS GIS Cut Line= 2
2315275.18571288621071.9531251152314616.65395232621512.157644305
#Sta/Elev= 30
       0 3094.92     9.4 3093.14    80.9 3072.01   104.7 3061.45   124.2 3060.12
   133.5 3055.25   176.1 3042.44   213.6 3038.92   224.9 3032.96   230.9 3031.15
   282.8 3030.97   321.2 3032.44   340.4 3030.53   383.8 3030.19   417.4 3032.21
   444.3 3028.56   455.9 3027.56   462.9 3028.65   475.1 3034.28   484.6 3035.87
   530.8 3031.39   576.2 3035.48   619.5 3046.95   657.2 3059.89   667.6 3061.62
   689.4 3069.44   712.5 3075.12   739.8 3085.56   768.6 3092.46   792.1 3103.41
#Mann= 7 ,-1,0
       0      .1       0      90     .06       0     210      .1       0
     440     .06       0   444.3    .045       0   462.9     .06       0
     560      .1       0
#XS Ineff= 2 , 0
                          487.21         3041.11
Permanent Ineff=
       F       F
Bank Sta=444.3,462.9
XS Rating Curve= 0 ,0
Exp/Cntr(USF)=0,0
Exp/Cntr=0.3,0.1

Type RM Length L Ch R = 1 ,88137   ,229.6,234.7,238.1
XS GIS Cut Line= 2
2315232.20620521620831.8996861662314537.10452173621310.346299468
#Sta/Elev= 30
       0 3112.95    38.3 3105.94   127.5 3085.99   140.9  3081.6     170 3075.18
   182.1 3071.13   193.6 3065.68   218.6 3065.13   228.8 3060.52     260 3053.49
     272 3051.78   282.8 3046.63   294.3 3043.31   315.7 3040.05   320.5 3038.45
   331.7  3030.8  346.65  3028.4   362.1 3027.52     369  3028.4   466.2 3032.98
   529.3 3031.96   581.9 3035.43   607.8 3033.01     674  3033.2   708.5 3039.92
   722.9  3044.4   745.9 3049.09   781.8 3058.69   791.6 3059.98   843.8 3073.77
#Mann= 8 ,-1,0
       0      .1       0      90     .06       0     260      .1       0
     280     .12       0  346.65    .045       0     369     .12       0
     520     .06       0     630      .1       0
#XS Ineff= 2 , 0
                           580.7         3037.27
Permanent Ineff=
       F       F
Bank Sta=346.65,369
XS Rating Curve= 0 ,0
Exp/Cntr(USF)=0,0
Exp/Cntr=0.3,0.1

Type RM Length L Ch R = 1 ,87903   ,481.8,485.2,481.8
XS GIS Cut Line= 2
      2315206.67      620639.8812314357.27770844621084.007109335
#Sta/Elev= 30
       0 3113.37    44.3  3107.8   142.7 3088.69   178.9 3083.09   251.1 3066.35
   264.6 3060.42   287.2 3058.84   296.2 3054.68   332.3 3045.69   359.4 3034.73
   372.9 3031.07   426.7 3030.07   462.2 3027.05   474.1 3025.63   486.2 3026.99
   508.4 3030.67   518.5 3029.55   544.5 3031.06   598.8 3029.38   616.7 3031.05
   641.6 3030.99   661.8 3035.14   687.5 3031.73   779.2 3032.13   797.2 3037.44
   842.4 3047.72   869.5 3056.36   901.1 3069.23   950.7  3094.2   958.5  3096.8
#Mann= 7 ,-1,0
       0      .1       0     230     .06       0     310     .12       0
   462.2    .045       0   486.2     .12       0     560     .06       0
     670      .1       0
#XS Ineff= 2 , 0
                          659.15          3039.6
Permanent Ineff=
       F       F
Bank Sta=462.2,486.2
XS Rating Curve= 0 ,0
Exp/Cntr=0.3,0.1

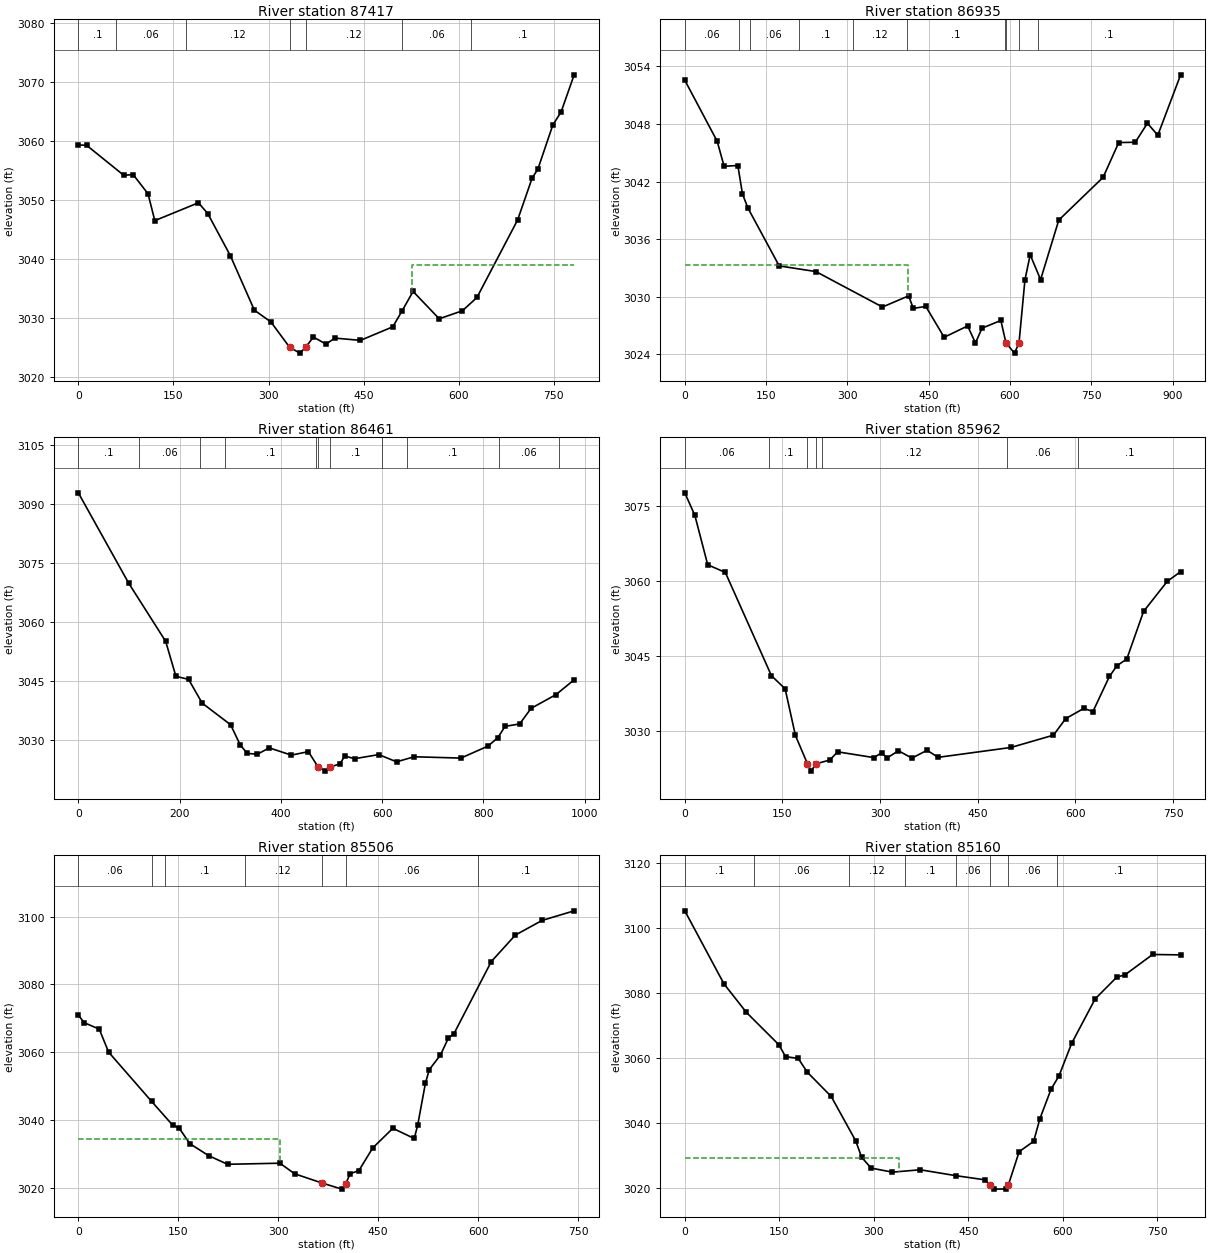
Type RM Length L Ch R = 1 ,87417   ,479.2,482.7,456.1
XS GIS Cut Line= 2
2314861.60646703620337.0955809822314178.22445135620716.949480606
#Sta/Elev= 30
       0 3059.38    12.9 3059.35    71.7 3054.25    86.4 3054.38   109.9 3051.12
   120.6 3046.57   189.4  3049.6   204.1 3047.77   239.6 3040.66   277.6  3031.4
   303.7  3029.4   333.2 3025.11   349.4 3024.12   358.6 3025.12   370.7 3026.85
   390.6 3025.64   404.4 3026.67   444.8 3026.28   495.9 3028.58     510 3031.18
   527.9 3034.57   569.1 3029.94   605.7  3031.3   628.6 3033.55   692.7 3046.68
   715.6 3053.77   724.7 3055.31   748.2 3062.76   761.3 3064.99   781.9 3071.28
#Mann= 7 ,-1,0
       0      .1       0      60     .06       0     170     .12       0
   333.2    .045       0   358.6     .12       0     510     .06       0
     620      .1       0
#XS Ineff= 2 , 0
                          526.42         3039.07
Permanent Ineff=
       F       F
Bank Sta=333.2,358.6
XS Rating Curve= 0 ,0
Exp/Cntr(USF)=0,0
Exp/Cntr=0.3,0.1

Type RM Length L Ch R = 1 ,86935   ,470.2,474,470.9
XS GIS Cut Line= 3
2314804.67094101620325.8641791392314416.19587097620190.831572724
2313997.17259265620470.221947673
#Sta/Elev= 30
       0 3052.55    59.8 3046.19    72.5 3043.59    97.9 3043.67   106.4 3040.71
   116.5 3039.24   174.2 3033.22   241.9 3032.63   364.7 3028.94     413  3030.1
   421.6  3028.8   444.7    3029   478.6 3025.79   521.9 3026.97   536.3  3025.2
   548.5 3026.74   583.2 3027.54  592.59  3025.2   608.4 3024.14  616.69  3025.2
   627.6 3031.75   637.3 3034.38   656.5 3031.79   690.1 3037.99   771.9 3042.44
   800.7 3046.06   831.2 3046.09   853.6 3048.07   872.8 3046.82   914.9 3053.11
#Mann= 10 ,-1,0
       0     .06       0     100      .1       0     120     .06       0
     210      .1       0     310     .12       0     410      .1       0
  591.27     .06       0  592.59    .045       0  616.69     .06       0
  651.27      .1       0
#XS Ineff= 2 , 0
          412.39 3033.32
Permanent Ineff=
       F       F
Bank Sta=592.59,616.69
XS Rating Curve= 0 ,0
Exp/Cntr(USF)=0,0
Exp/Cntr=0.3,0.1

Type RM Length L Ch R = 1 ,86461   ,497.5,499.1,494.7
XS GIS Cut Line= 2
2314815.06090626619637.0658409182313998.44319059620177.386187128
#Sta/Elev= 30
       0 3092.91    99.4 3069.97   172.5 3055.18   192.7  3046.3   217.7 3045.53
   244.6 3039.49   300.8 3033.99   319.7 3028.88   333.7 3026.72   353.6 3026.52
   377.2 3028.13   420.6 3026.28   454.3 3027.17   473.5 3023.28   487.9 3022.22
  497.05 3023.24   516.7 3024.09   526.3 3026.07   545.4 3025.37   593.4 3026.42
   628.5 3024.58   663.2 3025.87   755.5 3025.53   809.2 3028.59   828.4 3030.71
   842.8 3033.59   871.6 3034.21   894.1 3038.16   943.5 3041.67   979.2 3045.42
#Mann= 11 ,-1,0
       0      .1       0     120     .06       0     240     .12       0
     290      .1       0     470     .12       0   473.5    .045       0
  497.05      .1       0     600     .12       0     650      .1       0
     830     .06       0     950      .1       0
Bank Sta=473.5,497.05
XS Rating Curve= 0 ,0
Exp/Cntr(USF)=0,0
Exp/Cntr=0.3,0.1

Type RM Length L Ch R = 1 ,85962   ,452.1,455.2,465.8
XS GIS Cut Line= 3
2314413.45289416619468.8010755122314189.26532587619659.950905387
2313788.61251396619899.616958387
#Sta/Elev= 30
       0 3077.63    15.4 3073.13    35.2 3063.22    62.2  3061.7   133.1 3041.01
   154.1 3038.39   169.9 3029.05   188.4 3023.38   194.1 3021.91   201.4 3023.38
   222.5 3024.12   234.9 3025.77   290.3 3024.62   302.1 3025.56   310.9 3024.58
   328.2 3025.98   348.8 3024.52   372.1 3026.08   389.1 3024.67     501 3026.65
   566.2 3029.11   584.9 3032.41   612.8 3034.47   626.8 3033.83   652.1 3040.86
   663.8 3043.03   678.8 3044.35   704.6 3053.89   741.1 3059.92   761.5 3061.84
#Mann= 7 ,-1,0
       0     .06       0     130      .1       0   188.4    .045       0
   201.4      .1       0     210     .12       0  494.62     .06       0
  604.62      .1       0
Bank Sta=188.4,201.4
XS Rating Curve= 0 ,0
Exp/Cntr(USF)=0,0
Exp/Cntr=0.3,0.1

Type RM Length L Ch R = 1 ,85506   ,342.3,346.9,350.2
XS GIS Cut Line= 3
2314117.65111415619234.2142422262313730.02472707619595.107775027
2313516.16189282619610.701940025
#Sta/Elev= 30
       0 3070.99     8.8 3068.75    31.4 3066.86    45.4  3060.1     110 3045.58
   141.8 3038.54   151.1 3037.79   167.3 3033.15   195.6 3029.62   223.9 3027.08
   302.6  3027.4   324.5 3024.29   365.4 3021.59   395.5 3019.77     401 3021.23
   407.9 3024.29   421.1 3025.25   441.8 3031.89     472 3037.67   504.1 3034.67
   509.2 3038.52   520.9 3050.96   526.7 3054.94   543.5 3059.25   555.5  3064.3
   563.6 3065.47   619.7 3086.72   655.8 3094.53   695.9 3098.84   744.1 3101.67
#Mann= 7 ,-1,0
       0     .06       0     110     .12       0     130      .1       0
     250     .12       0   365.4    .045       0     401     .06       0
  599.62      .1       0
#XS Ineff= 2 , 0
          301.97 3034.52
Permanent Ineff=
       F       F
Bank Sta=365.4,401
XS Rating Curve= 0 ,0
Exp/Cntr(USF)=0,0
Exp/Cntr=0.3,0.1

Type RM Length L Ch R = 1 ,85160   ,330.3,346.4,361.4
XS GIS Cut Line= 2
2314014.92277488618961.4564585122313368.81614187619410.536068815
#Sta/Elev= 30
       0 3105.15    62.1 3082.72    97.6 3073.96   149.5 3063.94   159.8 3060.34
     180 3059.77   194.3 3055.57   232.3 3048.09   271.3 3034.41   280.5 3029.43
   295.6 3026.07   329.4 3024.82   373.6 3025.55     430 3023.74     476 3022.47
   484.6 3020.79   490.3  3019.6     510 3019.65   513.3  3020.8   530.6 3031.12
   553.6  3034.3   563.5 3041.25   581.2 3050.31   593.8 3054.42   613.9 3064.42
   651.2 3078.08   685.3 3084.73     699 3085.54   742.4 3091.73   786.8 3091.61
#Mann= 8 ,-1,0
       0      .1       0     110     .06       0     260     .12       0
     350      .1       0     430     .06       0   484.6    .045       0
   513.3     .06       0     590      .1       0
#XS Ineff= 2 , 0
          340.33 3029.15
Permanent Ineff=
       F       F
Bank Sta=484.6,513.3
XS Rating Curve= 0 ,0
Exp/Cntr(USF)=0,0
Exp/Cntr=0.3,0.1

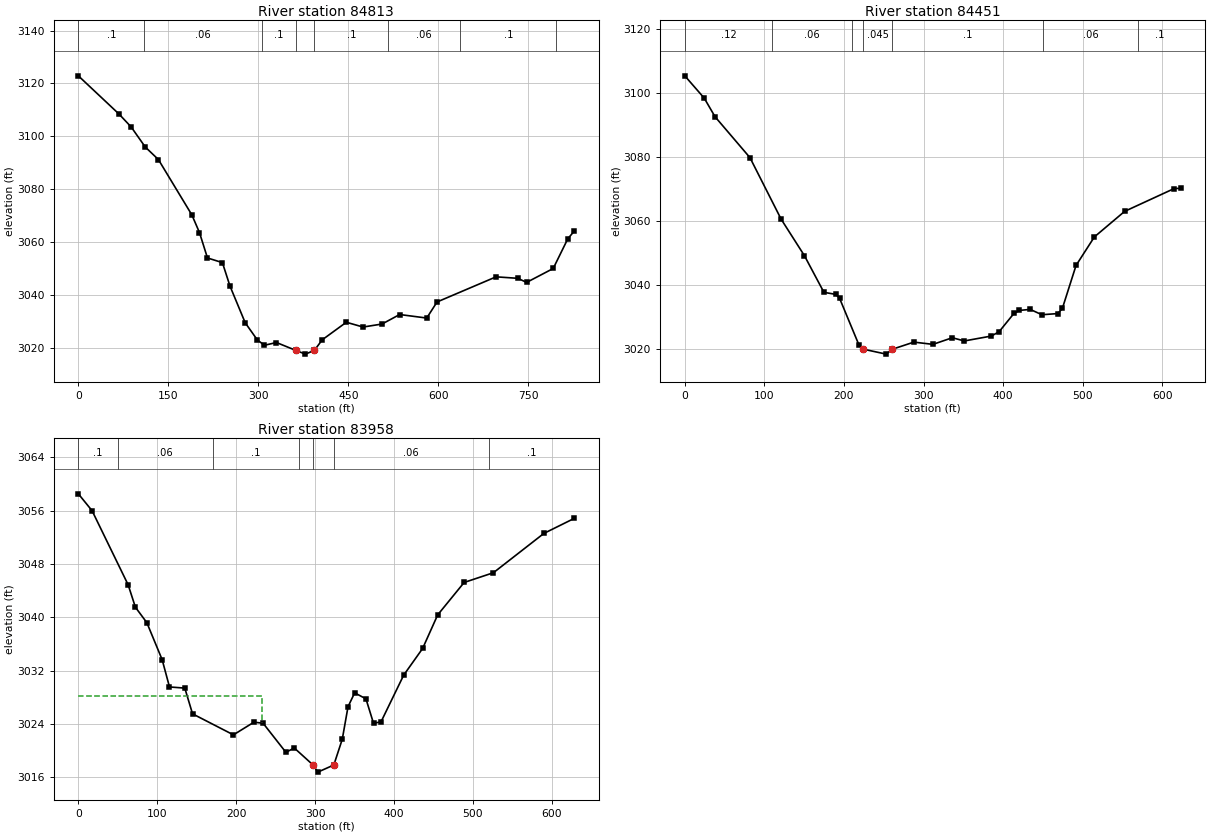
Type RM Length L Ch R = 1 ,84813   ,378.4,362.5,345.5
XS GIS Cut Line= 4
2313888.94477013 618752.011012492313657.84602861618903.669561612
 2313468.2728422618918.1132329572313175.78849747619127.546467459
#Sta/Elev= 30
       0 3122.89    67.8 3108.46    88.1 3103.57   111.5 3096.03   133.4 3091.29
   189.2 3070.39   201.9 3063.71   215.2 3054.13   240.1 3052.38   252.7 3043.53
   278.1 3029.67   298.3 3023.19   310.2 3021.18   330.2 3022.21   362.3 3019.25
   378.4 3017.83  393.32 3019.24   406.5 3023.24   446.6 3029.86   474.5 3028.06
   506.1 3029.19   535.5 3032.78   580.6 3031.45   597.8 3037.52   696.2 3047.01
   732.3 3046.45   747.1 3044.91   791.4 3050.16   815.7 3061.37   826.3 3064.24
#Mann= 8 ,-1,0
       0      .1       0     110     .06       0  306.42      .1       0
   362.3    .045       0  393.32      .1       0  516.54     .06       0
  636.54      .1       0  796.54     .12       0
Bank Sta=362.3,393.32
XS Rating Curve= 0 ,0
Exp/Cntr(USF)=0,0
Exp/Cntr=0.3,0.1

Type RM Length L Ch R = 1 ,84451   ,495.8,492.6,493.7
XS GIS Cut Line= 2
2313603.11854725618459.1263015322313093.68831738618817.679982486
#Sta/Elev= 30
       0 3105.27    24.4 3098.31      38  3092.5    81.9 3079.72     121 3060.54
   150.3 3049.13   174.8 3037.68   189.5 3037.06   194.4 3035.87   218.8 3021.26
   223.7 3019.97   253.1 3018.39   260.7 3019.91   287.8 3022.14   311.8 3021.44
   336.2 3023.51   351.1  3022.5   385.1 3024.03   394.9 3025.38   413.6 3031.11
   420.5 3032.04     434 3032.35   448.7 3030.69   468.7 3031.05   474.4 3032.65
   491.6 3046.08   514.6 3054.97   552.6 3062.95     615 3070.09     623 3070.14
#Mann= 7 ,-1,0
       0     .12       0     110     .06       0     210      .1       0
   223.7    .045       0   260.7      .1       0     450     .06       0
     570      .1       0
Bank Sta=223.7,260.7
XS Rating Curve= 0 ,0
Exp/Cntr(USF)=0,0
Exp/Cntr=0.3,0.1

Type RM Length L Ch R = 1 ,83958   ,376.5,398.3,424.3
XS GIS Cut Line= 2
2313272.96515786618137.8480032522312747.55976398618482.201538425
#Sta/Elev= 30
       0 3058.52    17.4 3055.99    63.1 3044.88    72.3 3041.52    86.8  3039.2
   106.2 3033.65   115.5 3029.56   134.9 3029.39   144.7 3025.53   196.5 3022.38
   222.5 3024.28   234.1 3024.12     263 3019.76   273.6 3020.41   297.5 3017.85
   303.4 3016.79   323.7 3017.86   334.4 3021.72   341.7  3026.6   350.1 3028.68
   364.4 3027.78     374 3024.11   383.5 3024.33   412.2 3031.33   436.2 3035.33
   455.3 3040.37   488.8 3045.23   525.9 3046.69   589.8 3052.58   628.2 3054.83
#Mann= 7 ,-1,0
       0      .1       0      50     .06       0     170      .1       0
     280     .06       0   297.5    .045       0   323.7     .06       0
     520      .1       0
#XS Ineff= 2 , 0
          232.68 3028.22
Permanent Ineff=
       F       F
Bank Sta=297.5,323.7
XS Rating Curve= 0 ,0
Exp/Cntr(USF)=0,0
Exp/Cntr=0.3,0.1