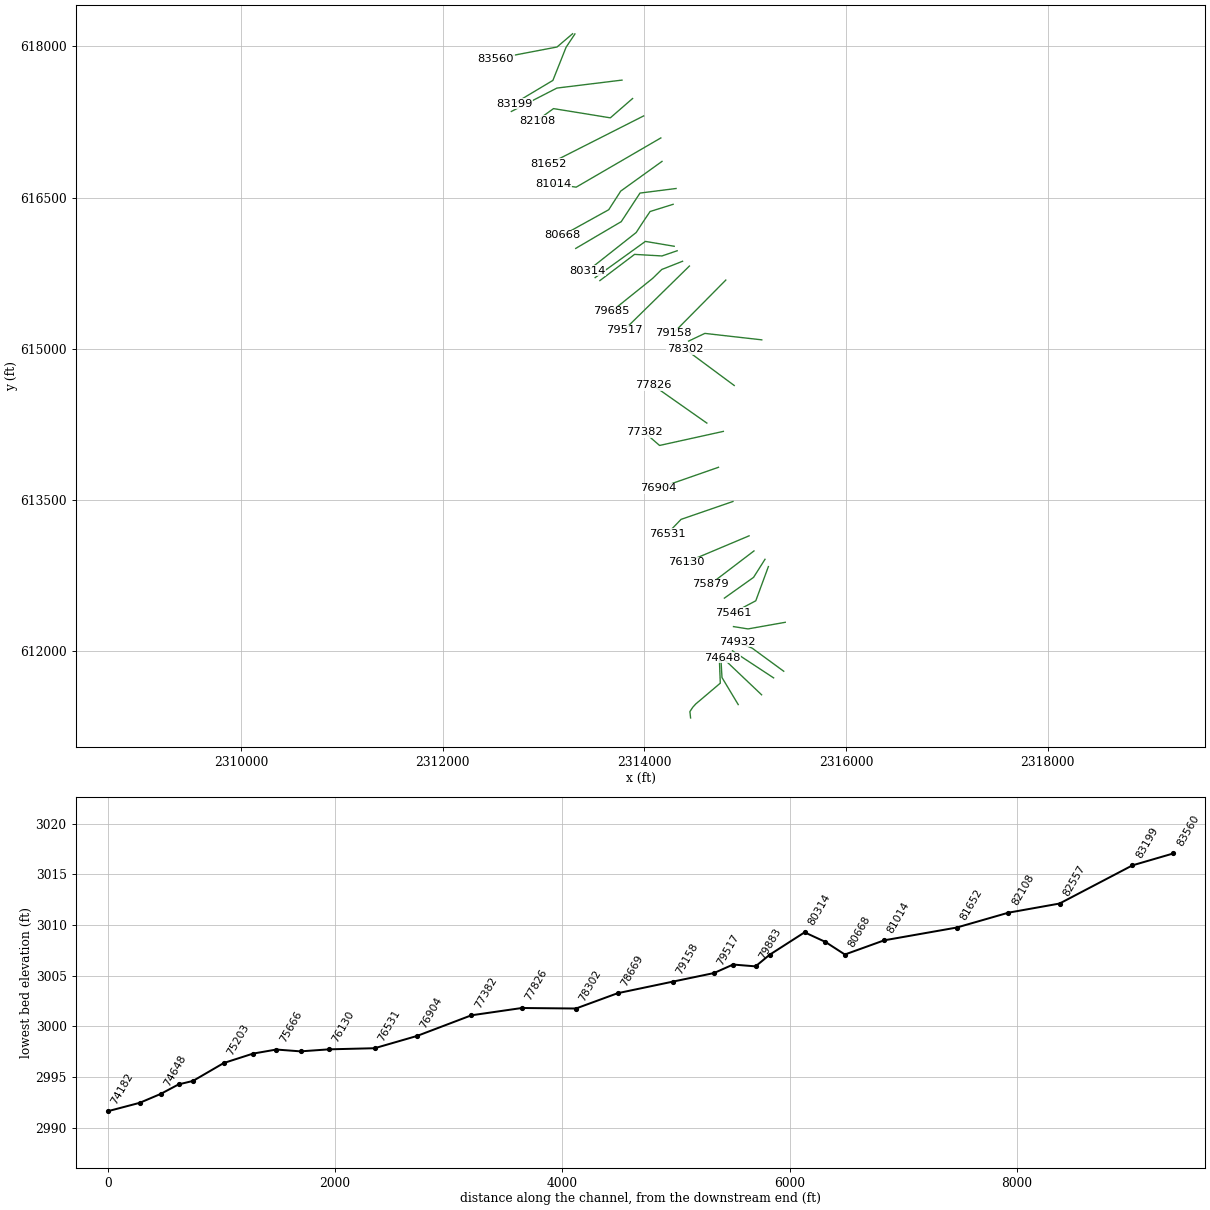
HEC-RAS study WFGRNBRRRV.prj: WFGRNBRRRV

--- WFGRNBRRRV.g01 (geometry) --- (continued)

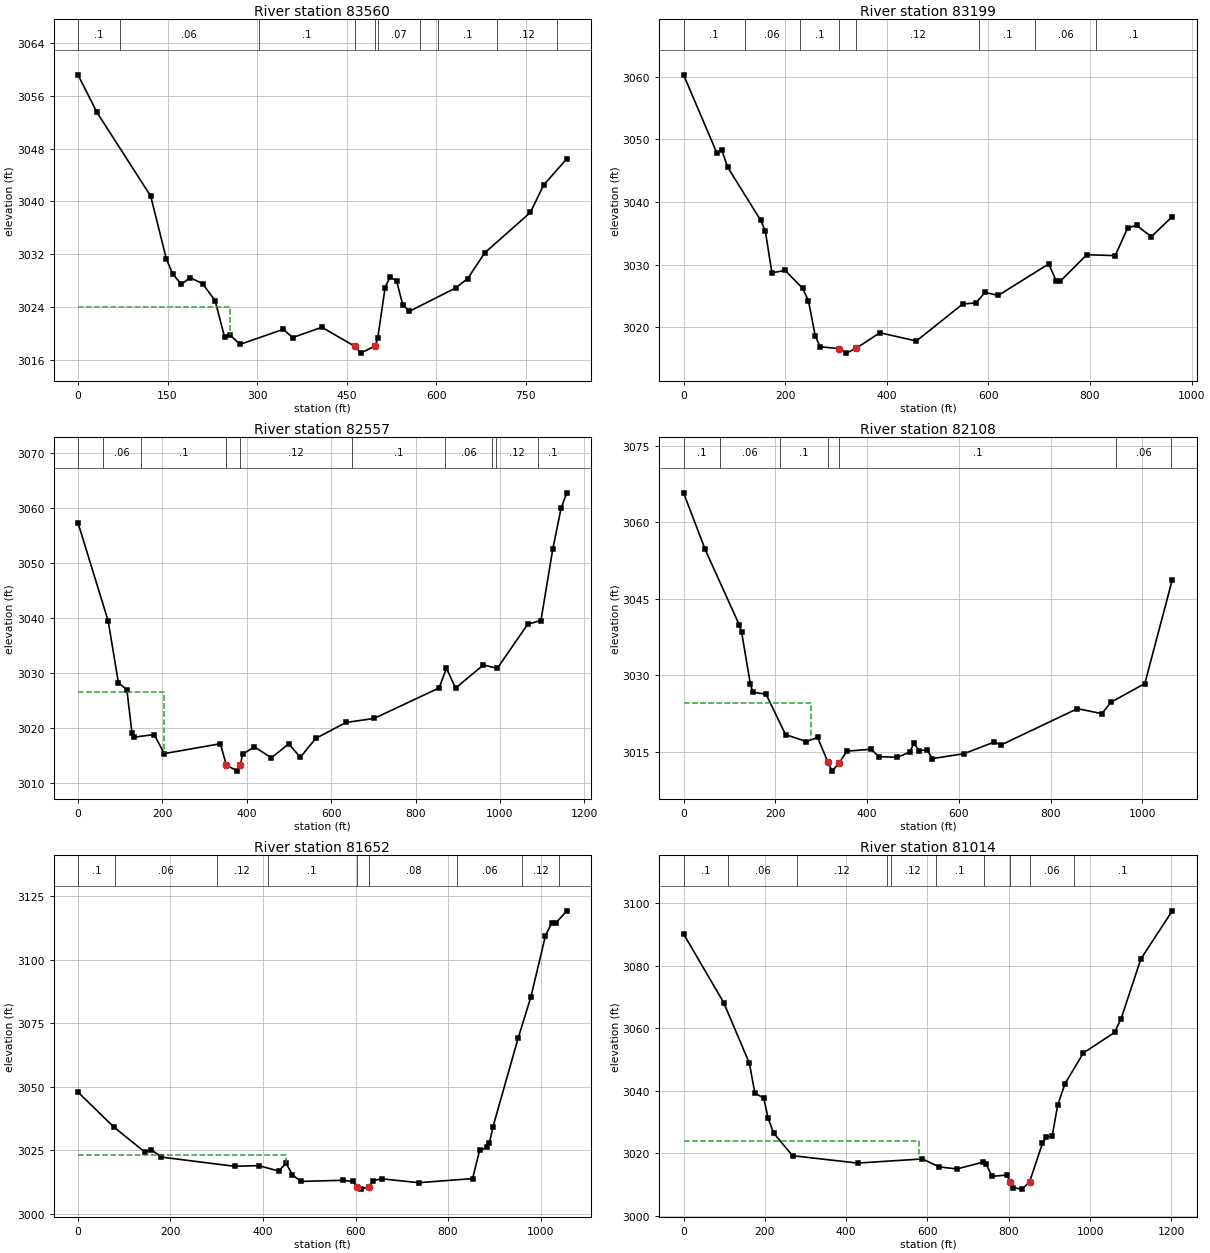
Type RM Length L Ch R = 1 ,83560   ,331.2,360.9,395.6
XS GIS Cut Line= 3
2313288.94032186618125.422875694 2313134.5137365617994.071527226
2312529.23252261617878.695342761
#Sta/Elev= 30
       0 3059.15    31.9 3053.46   121.8 3040.82     148 3031.34   158.5 3029.07
   173.2 3027.48     188 3028.49   208.9 3027.57   229.7 3025.01   245.8 3019.45
     254 3019.87   271.6 3018.39   343.6 3020.66   359.9 3019.43   408.7 3020.98
   463.8  3018.1   473.9 3017.07   498.3 3018.18   502.4 3019.42   514.6 3026.98
   522.7 3028.57   533.8 3027.99   544.1 3024.42   555.3 3023.39   632.7 3026.92
     653 3028.34   681.5 3032.23     758 3038.34   780.1 3042.47   818.9 3046.45
#Mann= 10 ,-1,0
       0      .1       0      70     .06       0  302.73      .1       0
   463.8    .045       0   498.3      .1       0  502.73     .07       0
  572.73     .06       0  602.73      .1       0  702.73     .12       0
  802.73      .1       0
#XS Ineff= 2 , 0
          254.57 3024.09
Permanent Ineff=
       F       F
Bank Sta=463.8,498.3
XS Rating Curve= 0 ,0
Exp/Cntr(USF)=0,0
Exp/Cntr=0.3,0.1

Type RM Length L Ch R = 1 ,83199   ,674.4,641.6,612.9
XS GIS Cut Line= 4
2313312.01555875618123.6478574722313224.22149988617991.003409245
2313093.71237778617662.965220498 2312707.7349788617432.045843453
#Sta/Elev= 30
       0 3060.28    65.3 3047.86    74.9 3048.36    86.7 3045.56   151.7 3037.08
     161 3035.34   173.9 3028.69   199.8 3029.09   234.2 3026.24   245.8 3024.25
   259.1 3018.66   268.7  3016.9   305.3 3016.62   320.3 3015.89   339.1 3016.63
   386.4 3019.14   458.1 3017.82   549.5 3023.73   575.8  3023.9   593.1 3025.58
   619.5  3025.1   718.7 3030.12   733.3 3027.44   741.5 3027.36   793.6 3031.59
   849.5 3031.44     874 3035.85   891.5 3036.27   920.7 3034.47   961.9 3037.67
#Mann= 8 ,-1,0
       0      .1       0     120     .06       0  229.07      .1       0
   305.3    .045       0   339.1     .12       0  582.11      .1       0
  692.11     .06       0  812.11      .1       0
Bank Sta=305.3,339.1
XS Rating Curve= 0 ,0
Exp/Cntr(USF)=0,0
Exp/Cntr=0.3,0.1

Type RM Length L Ch R = 1 ,82557   ,447.8,449.3,439.6
XS GIS Cut Line= 3
2313779.20871753617665.9139216622313133.32285012617586.790889128
2312681.88408975617355.064967111
#Sta/Elev= 30
       0 3057.27    71.6  3039.4    95.7 3028.22   115.9 3026.89     128 3019.02
     132 3018.28   180.4 3018.77   204.6 3015.31   337.5  3017.1   351.43013.234
   377.8 3012.12   384.8  3013.2   389.9 3015.18   418.1 3016.53   458.4 3014.54
   499.5 3017.08   526.9 3014.62   563.2 3018.06   635.2 3020.97   701.5 3021.69
   855.7 3027.24   873.2 3030.81   894.8 3027.21   960.8 3031.42   993.7 3030.81
  1065.9 3038.84  1097.1  3039.5  1125.2 3052.51  1144.8 3059.88  1158.2 3062.71
#Mann= 11 ,-1,0
       0      .1       0      60     .06       0     150      .1       0
     350     .12       0   351.4    .045       0   384.8     .12       0
     650      .1       0  870.71     .06       0  980.71      .1       0
  990.71     .12       0 1090.71      .1       0
#XS Ineff= 2 , 0
          203.32 3026.54
Permanent Ineff=
       F       F
Bank Sta=351.4,384.8
XS Rating Curve= 0 ,0
Exp/Cntr(USF)=0,0
Exp/Cntr=0.3,0.1

Type RM Length L Ch R = 1 ,82108   ,441.5,456.2,476.1
XS GIS Cut Line= 5
2313883.73863919617483.2122867852313663.19259137617291.626831101
2313448.11518364617326.8616997482313099.78244155617383.177730039
2312935.57689943617265.125980187
#Sta/Elev= 30
       0 3065.79    47.1 3054.68   121.3 3039.91   126.6 3038.42   145.7 3028.24
   151.4 3026.69   179.8 3026.31   222.3 3018.38   267.7 3017.02   292.1 3017.83
   314.13013.095   323.6 3011.22   338.93012.802     356 3015.14   408.7 3015.51
   425.5 3014.07   465.4 3013.92   492.7 3014.94   501.9 3016.64   514.1 3015.23
   530.3  3015.4   542.4 3013.68   611.3 3014.64   676.2 3016.89   692.4 3016.37
   858.5 3023.47   911.7 3022.49   931.4 3024.72  1005.3 3028.39  1065.2 3048.75
#Mann= 7 ,-1,0
       0      .1       0      80     .06       0     210      .1       0
   314.1    .045       0   338.9      .1       0  942.94     .06       0
 1062.94     .12       0
#XS Ineff= 2 , 0
          277.08 3024.49
Permanent Ineff=
       F       F
Bank Sta=314.1,338.9
XS Rating Curve= 0 ,0
Exp/Cntr(USF)=0,0
Exp/Cntr=0.3,0.1

Type RM Length L Ch R = 1 ,81652   ,617.3,637.5,640.8
XS GIS Cut Line= 2
2313993.62255621617310.6895115472313051.08788004616833.209609683
#Sta/Elev= 30
       0 3047.88    77.9 3034.09   145.1 3024.24   158.6 3025.27   180.4 3022.34
   338.5 3018.73   390.6 3018.98   433.8 3016.86     450 3019.92   463.6  3015.4
   481.4 3012.78   573.6 3013.22   594.5 3012.75   602.5 3010.74   612.3 3009.75
     6293010.708   638.3  3013.1   656.3 3013.79     737 3012.29   853.1 3013.89
   868.3 3025.01     885 3026.13   889.5 3027.99   897.3 3034.32   951.6 3069.12
   979.1 3085.26  1010.5 3109.29    1024 3114.37  1032.9 3114.28  1056.6 3119.14
#Mann= 10 ,-1,0
       0      .1       0      80     .06       0     300     .12       0
     410      .1       0   602.5    .045       0     629      .1       0
     630     .08       0     820     .06       0     960     .12       0
    1040      .1       0
#XS Ineff= 2 , 0
          450.45 3023.27
Permanent Ineff=
       F       F
Bank Sta=602.5,629
XS Rating Curve= 0 ,0
Exp/Cntr(USF)=0,0
Exp/Cntr=0.3,0.1

Type RM Length L Ch R = 1 ,81014   ,327.1,345.9,363.9
XS GIS Cut Line= 3
2314164.02430557617092.3622701742313324.44068631616604.232258975
 2313095.4633356616636.182586981
#Sta/Elev= 30
       0 3090.17    98.8 3068.17   161.8 3048.83   175.6 3039.17   197.3 3037.66
     208 3031.18   221.9 3026.36   268.2 3019.19   428.1 3016.83   587.7 3018.15
   629.1  3015.6   672.2 3014.95   735.5 3017.07   744.8 3016.47   758.6 3012.59
   795.7 3012.99   803.93010.663   809.8 3008.95   832.7 3008.49   851.2 3010.77
   882.9 3023.13   892.8 3025.16   906.7 3025.34   920.6 3035.47   938.5 3042.24
   983.6 3052.06  1060.3 3058.63  1076.4 3063.01  1124.9 3082.12  1202.4 3097.56
#Mann= 10 ,-1,0
       0      .1       0     110     .06       0     280     .12       0
     500      .1       0     510     .12       0     620      .1       0
     740     .06       0   803.9    .045       0   851.2     .06       0
     960      .1       0
#XS Ineff= 2 , 0
          578.14 3023.87
Permanent Ineff=
       F       F
Bank Sta=803.9,851.2
XS Rating Curve= 0 ,0
Exp/Cntr(USF)=0,0
Exp/Cntr=0.3,0.1

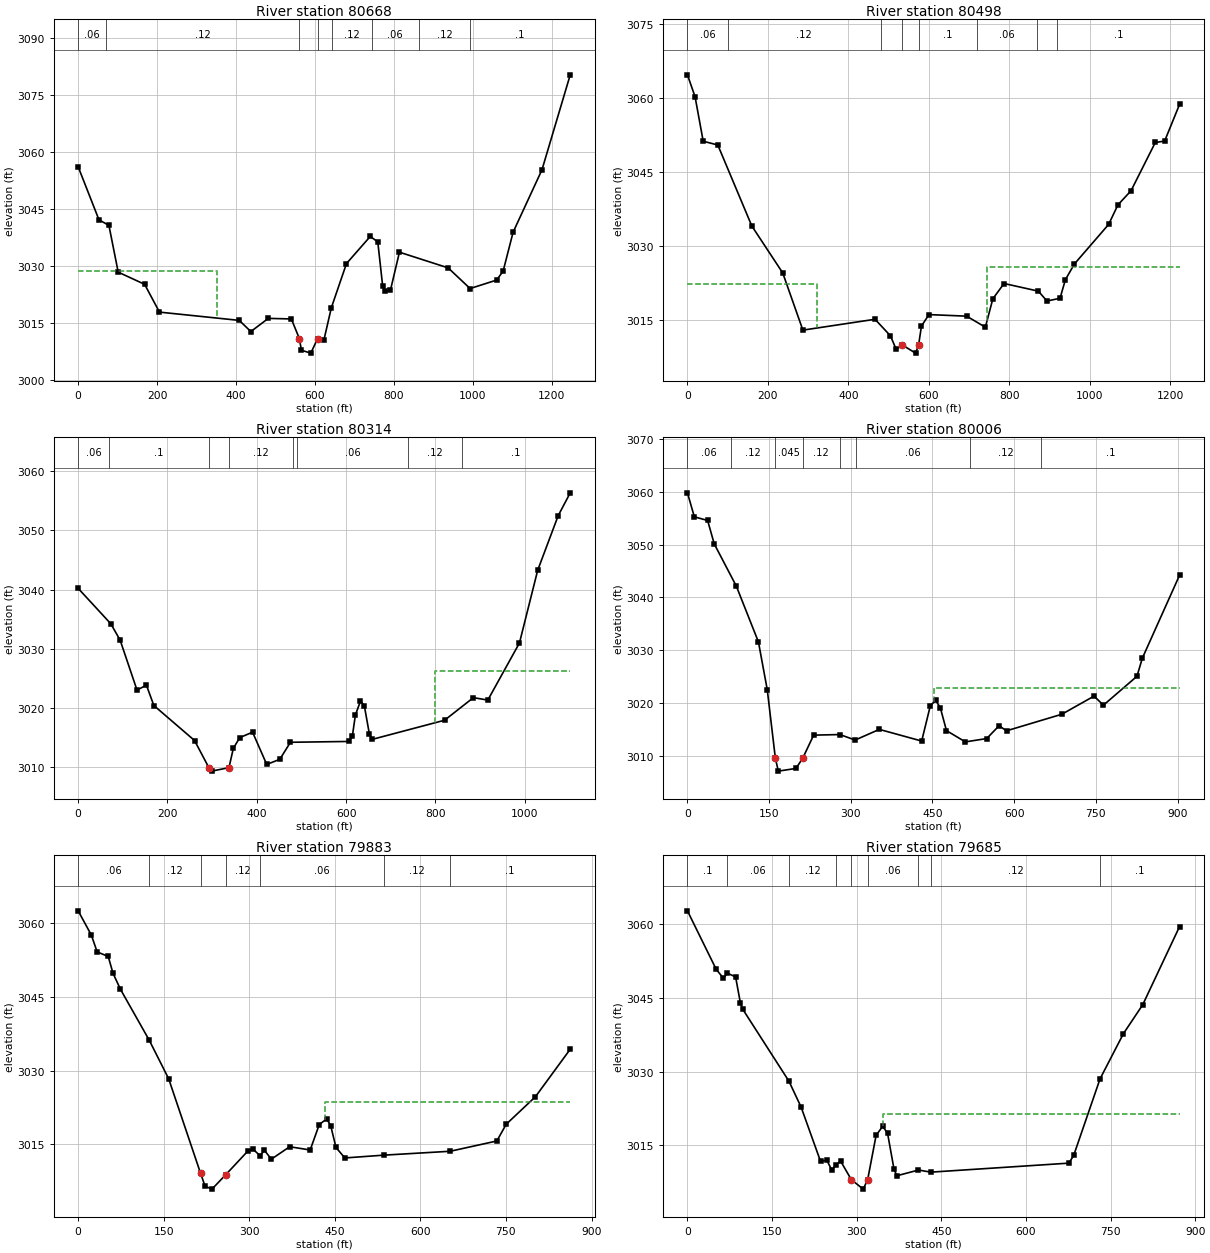
Type RM Length L Ch R = 1 ,80668   ,173,170.8,171.3
XS GIS Cut Line= 4
2314175.48407235 616859.596137882313766.48250507 616565.42060322
2313647.49400281616380.579962935 2313189.5393014616126.752357111
#Sta/Elev= 30
       0 3056.18    52.8 3042.19      78 3040.74   101.5 3028.42   168.5 3025.21
   206.1 3017.89   408.3 3015.71   437.7 3012.77     482 3016.24   540.4 3016.09
   560.6 3010.93   565.9 3007.85   589.7 3007.09   606.9 3010.92     623 3010.58
   641.7 3019.03   680.1 3030.68   740.3 3037.81   759.4 3036.41   771.9 3024.69
   777.7 3023.44   791.5 3023.65   814.3 3033.67   937.8 3029.54   993.4  3024.1
  1060.7 3026.33  1077.2 3028.71  1102.4 3038.94  1175.6 3055.38  1247.2 3080.38
#Mann= 8 ,-1,0
       0     .06       0      70     .12       0   560.6    .045       0
   606.9      .1       0  643.81     .12       0  743.63     .06       0
  863.63     .12       0  993.63      .1       0
#XS Ineff= 2 , 0
          351.16 3028.76
Permanent Ineff=
       F       F
Bank Sta=560.6,606.9
XS Rating Curve= 0 ,0
Exp/Cntr(USF)=0,0
Exp/Cntr=0.3,0.1

Type RM Length L Ch R = 1 ,80498   ,185.1,183.5,183.6
XS GIS Cut Line= 4
 2314315.0330748616590.8766874982313957.55220902616545.740214545
2313771.58994045  616262.28316442313320.22521092615996.880703436
#Sta/Elev= 30
       0 3064.73      19 3060.28    39.2 3051.27    75.5 3050.51   160.1 3034.08
   236.8 3024.59   286.9 3012.99   466.2 3015.19   504.5 3011.84   518.9 3009.07
  534.25 3009.98   566.8 3008.33   574.3  3009.9   581.6 3013.81   600.2 3016.14
   693.9 3015.82   740.4 3013.59     759 3019.34   786.8 3022.44   872.1 3020.89
   893.5 3018.89     926 3019.45   939.3 3023.22   961.9 3026.42  1046.7 3034.41
  1069.9 3038.38  1102.4 3041.24  1162.7 3051.02  1185.9  3051.3  1222.9 3058.72
#Mann= 8 ,-1,0
       0     .06       0     100     .12       0  480.32      .1       0
  534.25    .045       0   574.3      .1       0  719.33     .06       0
  869.33     .12       0  919.33      .1       0
#XS Ineff= 2 , 0
          320.93 3022.37  744.19         3025.78
Permanent Ineff=
       F       F
Bank Sta=534.25,574.3
XS Rating Curve= 0 ,0
Exp/Cntr(USF)=0,0
Exp/Cntr=0.3,0.1

Type RM Length L Ch R = 1 ,80314   ,353.7,308.3,265.8
XS GIS Cut Line= 5
2314286.00281829616434.1692098742314057.45171374  616362.7469897
2313984.24393806616253.828103935 2313919.5373119616154.346602395
2313438.95345403615774.811736203
#Sta/Elev= 30
       0  3040.2    73.2  3034.2    94.1 3031.42   131.8 3022.98   152.8 3023.83
   169.5 3020.38   260.6 3014.46  292.79 3009.85   299.1 3009.28   337.7 3009.87
   347.4 3013.13   361.8 3014.95   390.5 3015.87   422.2 3010.41   451.5 3011.28
   475.3 3014.16   605.8  3014.3   613.9 3015.19   620.7 3018.77   632.1 3021.13
   640.7 3020.35   652.1 3015.53   657.8 3014.64   820.4 3017.89   884.9 3021.71
   917.2  3021.3     988 3030.96  1028.8 3043.25  1074.7 3052.49  1101.7 3056.36
#Mann= 8 ,-1,0
       0     .06       0      70      .1       0  292.79    .045       0
   337.7     .12       0  480.69      .1       0  489.36     .06       0
  739.36     .12       0  859.36      .1       0
#XS Ineff= 2 , 0
                          799.34          3026.2
Permanent Ineff=
       F       F
Bank Sta=292.79,337.7
XS Rating Curve= 0 ,0
Exp/Cntr(USF)=0,0
Exp/Cntr=0.3,0.1

Type RM Length L Ch R = 1 ,80006   ,119.4,123.4,127.8
XS GIS Cut Line= 3
2314296.71615132616018.1347773622314011.02727063616066.344775979
2313512.85728491615707.448119607
#Sta/Elev= 30
       0  3059.8    12.7 3055.25    37.1 3054.56    49.2 3050.13    89.8 3042.12
   130.4 3031.54   146.6 3022.49  161.46 3009.53   166.9 3007.06   199.3 3007.57
   211.7  3009.5   231.8 3013.88     280 3013.99     308 3012.95   352.4 3014.97
   430.2 3012.76   446.1 3019.47   455.9 3020.47   464.5 3019.05   475.7 3014.74
   510.4  3012.6   549.6 3013.23   572.3 3015.66     586  3014.7   687.6 3017.84
   746.8 3021.28   763.9 3019.55   825.5 3025.03   835.5 3028.48   903.7 3044.17
#Mann= 8 ,-1,0
       0     .06       0      80     .12       0  161.46    .045       0
   211.7     .12       0     280      .1       0  309.73     .06       0
  519.73     .12       0  649.73      .1       0
#XS Ineff= 2 , 0
                          453.52         3022.76
Permanent Ineff=
       F       F
Bank Sta=161.46,211.7
XS Rating Curve= 0 ,0
Exp/Cntr(USF)=0,0
Exp/Cntr=0.3,0.1

Type RM Length L Ch R = 1 ,79883   ,174.1,197.5,224.4
XS GIS Cut Line= 4
2314326.02845411615973.6129194682314175.93521729615922.151492583
2313903.57411714615937.552022945 2313559.5423689615677.527423678
#Sta/Elev= 30
       0 3062.51    23.1 3057.59    33.3 3054.16    52.7 3053.23    61.2 3049.79
    74.2 3046.55   124.5 3036.23   158.7 3028.36   214.7 3009.11   222.5 3006.51
   234.6 3005.92   258.6 3008.83   297.8  3013.7   306.7 3014.04   318.7 3012.73
   326.7  3013.8   338.7 3012.01   370.8 3014.54   406.8 3013.88   422.7 3019.05
   435.7  3020.2   442.7 3018.85     452  3014.4   467.5 3012.26     536 3012.83
   652.3 3013.62     734 3015.71   750.5 3019.12   801.7 3024.71   862.7 3034.37
#Mann= 7 ,-1,0
       0     .06       0   124.5     .12       0   214.7    .045       0
   258.6     .12       0   318.7     .06       0     536     .12       0
   652.3      .1       0
#XS Ineff= 2 , 0
                          432.11         3023.57
Permanent Ineff=
       F       F
Bank Sta=214.7,258.6
XS Rating Curve= 0 ,0
Exp/Cntr(USF)=0,0
Exp/Cntr=0.3,0.1

Type RM Length L Ch R = 1 ,79685   ,168.4,168.1,167.9
XS GIS Cut Line= 4
2314379.60146047615869.4410098662314173.34456057615787.903777764
2314082.00730845615698.7942634922313674.33128065615371.316798543
#Sta/Elev= 30
       0 3062.65      51 3050.76    63.9 3048.94    70.7 3049.99    85.4 3049.22
      94 3043.86    98.3 3042.61     180 3028.02   201.5 3022.77   235.9 3011.76
   247.2 3011.95   255.7 3010.01   264.1  3011.1   271.5 3011.81   290.5 3008.03
   311.6  3006.1  319.45 3008.01   334.5 3017.05     346 3018.84   354.7 3017.49
   366.1 3010.21   371.1 3008.81   409.5 3009.98   431.5 3009.55   676.2 3011.38
   684.7 3012.95   731.4  3028.5   772.9  3037.7   807.1 3043.57   872.3 3059.43
#Mann= 9 ,-1,0
       0      .1       0    70.7     .06       0     180     .12       0
   264.1     .06       0   290.5    .045       0  319.45     .06       0
   409.5      .1       0   431.5     .12       0   731.4      .1       0
#XS Ineff= 2 , 0
                          345.92         3021.28
Permanent Ineff=
       F       F
Bank Sta=290.5,319.45
XS Rating Curve= 0 ,0
Exp/Cntr(USF)=0,0
Exp/Cntr=0.3,0.1

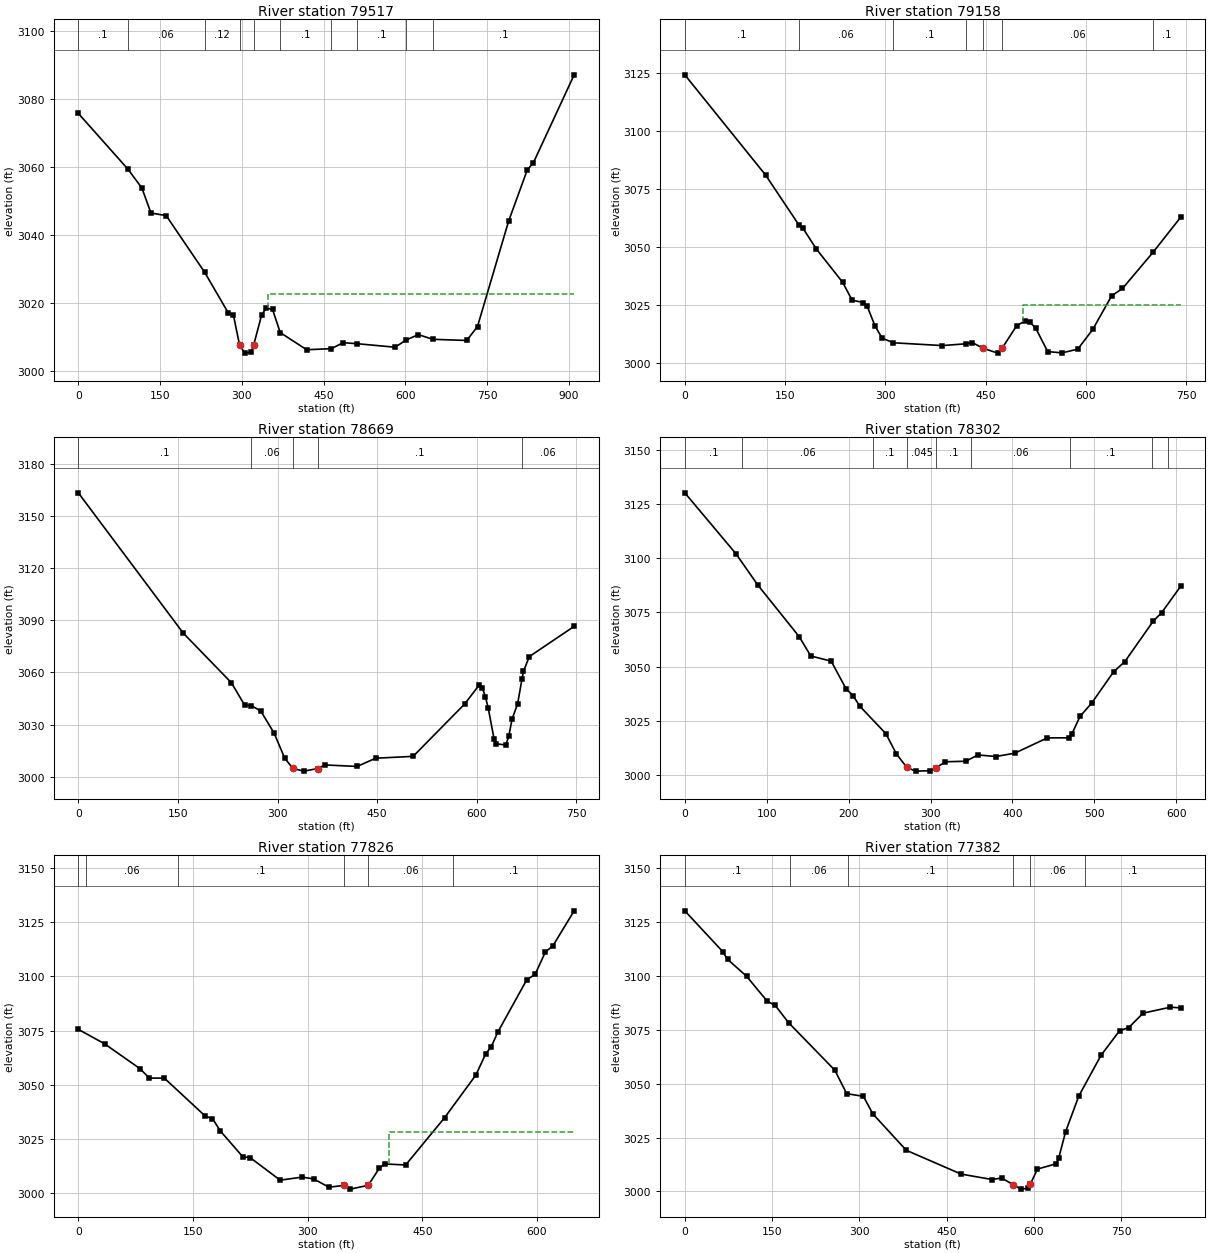
Type RM Length L Ch R = 1 ,79517   ,359,359.4,359.7
XS GIS Cut Line= 2
 2314447.3659773615822.017945332 2313797.5969773615184.908945332
#Sta/Elev= 30
       0 3075.85    90.5 3059.53   116.5 3053.93   133.3 3046.52   161.2 3045.76
     232 3029.03   275.4 3017.05   284.6 3016.51   295.8 3007.72   305.5 3005.26
   316.8  3005.5  321.82 3007.65   336.6  3016.6   345.1 3018.51   356.4 3018.12
   370.6 3011.31     419 3006.26     464 3006.57   486.2 3008.34     512 3008.03
   581.5    3007   601.1 3009.08     624 3010.71   650.6 3009.33   712.8 3008.99
   732.6  3013.1   789.6 3044.08   823.9 3059.19   835.3 3061.37     910 3087.21
#Mann= 10 ,-1,0
       0      .1       0    90.5     .06       0     232     .12       0
   295.8    .045       0  321.82     .06       0   370.6      .1       0
     464     .12       0     512      .1       0   601.1     .12       0
   650.6      .1       0
#XS Ineff= 2 , 0
                          347.61         3022.61
Permanent Ineff=
       F       F
Bank Sta=295.8,321.82
XS Rating Curve= 0 ,0
Exp/Cntr=0.3,0.1

Type RM Length L Ch R = 1 ,79158   ,517.8,488.7,454
XS GIS Cut Line= 2
2314808.35592035615682.9978014762314286.50056293615155.817389381
#Sta/Elev= 30
       0 3124.28   120.8 3081.14   170.8  3059.6   176.8 3058.17   196.6 3049.36
   236.2  3034.9   250.3 3027.22   267.3 3026.21   272.7 3024.74   284.5 3016.18
   295.2 3010.88   312.1 3008.88   385.3 3007.67     420 3008.43   430.3 3008.97
   445.5 3006.61   468.1 3004.42   475.3  3006.8   496.4 3016.16   509.1 3018.31
   516.2 3017.77   524.7 3015.33   542.9 3005.08   564.3 3004.53   587.9 3006.13
   610.4 3014.66   638.6 3029.11   654.8 3032.26   700.5 3047.83   741.8 3062.91
#Mann= 7 ,-1,0
       0      .1       0   170.8     .06       0   312.1      .1       0
     420     .06       0   445.5    .045       0   475.3     .06       0
   700.5      .1       0
#XS Ineff= 2 , 0
                          506.14         3025.33
Permanent Ineff=
       F       F
Bank Sta=445.5,475.3
XS Rating Curve= 0 ,0
Exp/Cntr(USF)=0,0
Exp/Cntr=0.3,0.1

Type RM Length L Ch R = 1 ,78669   ,384.5,366.8,349.2
XS GIS Cut Line= 3
2315165.13458309615090.1417151472314600.67878832615154.042371158
2314439.15213007615077.716587589
#Sta/Elev= 30
       0 3163.27     158 3082.62   230.4 3054.13   250.5 3041.17   260.4 3040.98
   274.7 3037.83   294.8 3025.16   310.9 3010.64     323 3004.87   339.1 3003.27
   360.8 3004.74   371.3 3006.83   419.8 3005.96   447.8 3010.69   504.2 3011.76
   581.9  3041.9     604 3052.94   608.4  3051.3   612.9 3046.13   617.2 3039.73
   626.1 3021.71   629.2 3018.98   643.8  3018.3   648.3 3023.42   653.2 3033.25
   661.5 3041.86   668.2 3056.36   670.4 3060.71   679.2 3069.13   746.7  3086.5
#Mann= 5 ,-1,0
       0      .1       0   260.4     .06       0     323    .045       0
   360.8      .1       0   668.2     .06       0
Bank Sta=323,360.8
XS Rating Curve= 0 ,0
Exp/Cntr(USF)=0,0
Exp/Cntr=0.3,0.1

Type RM Length L Ch R = 1 ,78302   ,475.6,475.7,476.5
XS GIS Cut Line= 2
2314891.78177681614637.5120683982314405.42678384614997.840767574
#Sta/Elev= 30
       0 3130.22    62.4 3102.12    89.1 3087.67   139.6 3063.86   153.8 3054.91
   178.7 3052.52   196.8  3039.8   205.4 3036.57   213.9 3031.63   245.4 3019.09
   258.4 3009.66   271.1 3003.45   281.7 3001.76   299.7 3001.95   307.1 3003.36
   318.1 3006.08     343 3006.32   357.9 3009.23   379.8 3008.51   402.7 3010.03
   442.7 3017.12   468.5 3017.13   472.4 3018.81   482.4 3026.98   496.7 3033.16
   523.5 3047.61   537.2 3052.32     572 3071.06     582 3074.84   605.3 3087.04
#Mann= 9 ,-1,0
       0      .1       0      70     .06       0     230      .1       0
   271.1    .045       0   307.1      .1       0     350     .06       0
     470      .1       0     570     .06       0     590      .1       0
Bank Sta=271.1,307.1
XS Rating Curve= 0 ,0
Exp/Cntr(USF)=0,0
Exp/Cntr=0.3,0.1

Type RM Length L Ch R = 1 ,77826   ,418.4,444.3,468.3
XS GIS Cut Line= 2
2314620.20398877614264.7582416642314089.47354023614637.512068398
#Sta/Elev= 30
       0 3075.58    34.3 3068.91    80.5 3057.46    92.9 3053.07   112.5 3053.06
   166.2 3035.47   175.5 3034.36   185.8 3028.65   215.1 3016.76   224.9 3016.32
     264 3005.95     293 3007.36     308  3006.5   327.8  3002.7   347.8 3003.54
   355.7 3001.81   379.3 3003.58   393.7 3011.47   400.9 3013.43   428.2 3012.96
   479.1 3034.78     520 3054.47   532.8  3064.2   540.3 3067.64   548.7 3074.29
   586.6 3098.46   597.6 3101.01     611 3111.32   620.8 3114.16   648.6  3130.3
#Mann= 6 ,-1,0
       0      .1       0      10     .06       0     130      .1       0
   347.8    .045       0   379.3     .06       0     490      .1       0
#XS Ineff= 2 , 0
                          406.98         3028.29
Permanent Ineff=
       F       F
Bank Sta=347.8,379.3
XS Rating Curve= 0 ,0
Exp/Cntr(USF)=0,0
Exp/Cntr=0.3,0.1

Type RM Length L Ch R = 1 ,77382   ,471.7,478.6,474.6
XS GIS Cut Line= 3
     2314783.829      614182.3222314151.59917801614042.880963846
2313996.77707737614176.547204928
#Sta/Elev= 30
       0 3130.09    65.2 3111.18    73.4 3107.62   106.1 3099.78   141.6 3088.19
   155.3 3086.26   178.5 3078.19   257.7 3056.25   278.2 3045.34   306.9  3044.1
   323.2 3035.94   380.6 3019.09   474.8 3008.06     528 3005.55   544.4 3006.24
   564.5 3003.12   577.2 3001.09   589.5 3001.51   593.6 3003.28   605.9 3010.39
   638.6 3012.87   642.7 3015.66   654.3 3027.66     677 3044.23   715.4  3063.2
   747.1 3074.49   762.9    3076   787.6 3082.66   834.6 3085.44     852 3085.09
#Mann= 6 ,-1,0
       0      .1       0     180     .06       0     280      .1       0
   564.5    .045       0   593.6     .06       0  687.42      .1       0
Bank Sta=564.5,593.6
XS Rating Curve= 0 ,0
Exp/Cntr=0.3,0.1

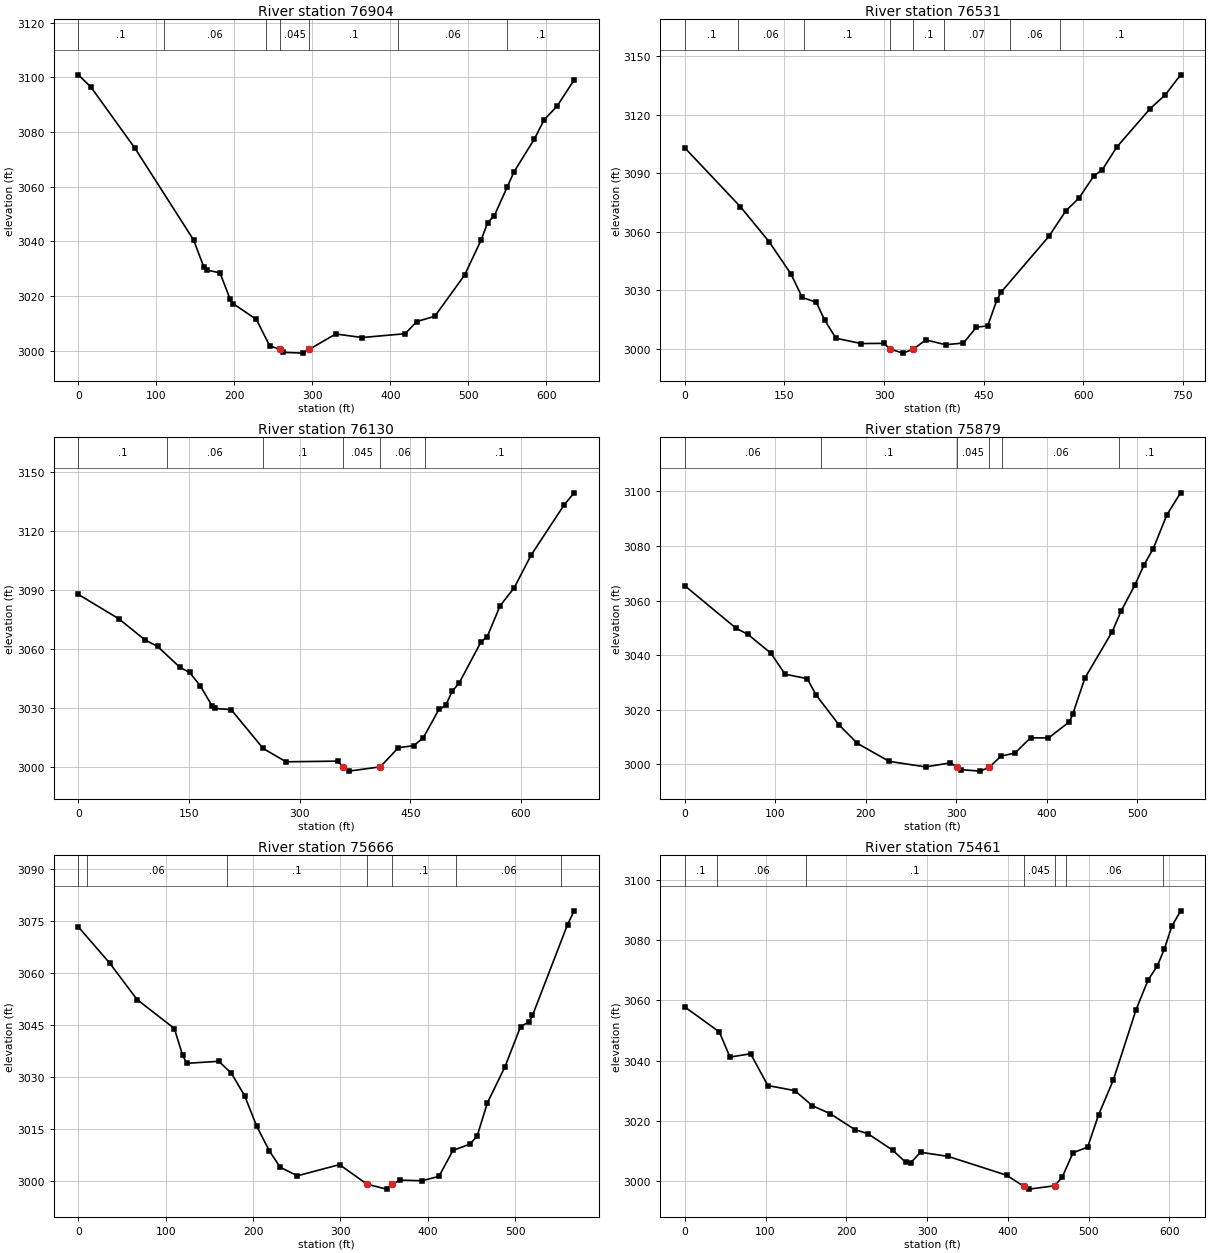
Type RM Length L Ch R = 1 ,76904   ,372.1,373,371.5
XS GIS Cut Line= 2
2314735.58017323613826.3287406962314135.62401401613616.876590436
#Sta/Elev= 30
       0  3100.9    16.1 3096.43    72.7 3073.98   147.7 3040.48   160.6 3030.75
   164.6 3029.47   181.6 3028.41   194.3 3018.99   198.3 3017.18   228.2 3011.38
   245.1  3001.8   258.3 3000.39     262 2999.36   287.5 2999.05   295.9  3000.4
   329.8 3006.06   363.7 3004.76   418.8 3006.15   433.8  3010.6   456.9 3012.55
   495.1 3027.62   516.3 3040.47   524.7 3046.84   533.2 3049.36     550 3060.03
   558.6 3065.49   584.6 3077.44   597.1 3084.47   613.7 3089.48   635.5 3099.04
#Mann= 7 ,-1,0
       0      .1       0     110     .06       0     240      .1       0
   258.3    .045       0   295.9      .1       0     410     .06       0
     550      .1       0
Bank Sta=258.3,295.9
XS Rating Curve= 0 ,0
Exp/Cntr(USF)=0,0
Exp/Cntr=0.3,0.1

Type RM Length L Ch R = 1 ,76531   ,397.4,400.1,403.5
XS GIS Cut Line= 3
2314879.35664926613487.3002601912314364.60136472613309.798437936
2314224.37492514613164.246943688
#Sta/Elev= 30
       0 3102.95    83.8 3072.78   126.9  3054.9   159.9 3038.34   176.8 3026.36
     198 3023.87   210.7 3014.68   227.6 3005.47   265.7 3002.73   299.5 3002.85
   309.4 2999.95   328.2 2997.84     344 2999.85     344 2999.86     363 3004.63
   392.6 3002.15   419.5 3003.01   439.2 3011.12   456.1 3011.82   469.8 3024.91
   476.1 3028.97   548.1 3057.57   573.9 3070.77   593.3 3077.14     616 3088.59
   628.7 3091.78   650.9 3103.54   700.8 3123.06   723.5 3130.07   746.6 3140.34
#Mann= 8 ,-1,0
       0      .1       0      80     .06       0     180      .1       0
   309.4    .045       0     344      .1       0     390     .07       0
     490     .06       0   564.5      .1       0
Bank Sta=309.4,344
XS Rating Curve= 0 ,0
Exp/Cntr(USF)=0,0
Exp/Cntr=0.3,0.1

Type RM Length L Ch R = 1 ,76130   ,239.8,251.7,261.8
XS GIS Cut Line= 2
2315039.10828929613146.4967614632314419.62692962612885.569082749
#Sta/Elev= 30
       0 3087.84    55.2 3075.33      90 3064.72   107.4 3061.32   137.7 3050.65
   150.8 3048.06   165.1 3041.36   181.1 3031.13   185.5 3029.68   207.2 3029.08
   250.6 3009.28   281.6 3002.49   351.4 3002.83   359.1 2999.85   366.7 2997.73
   409.4 2999.92   433.9  3009.7   454.6 3010.68   467.6 3014.69   488.8 3029.17
     498 3031.21   506.7 3038.36   516.3 3042.68   545.7 3063.45   554.4 3066.34
   571.8 3082.05   590.8 3091.13     614 3107.98   658.6 3133.46   672.2 3139.63
#Mann= 6 ,-1,0
       0      .1       0     120     .06       0     250      .1       0
   359.1    .045       0   409.4     .06       0     470      .1       0
Bank Sta=359.1,409.4
XS Rating Curve= 0 ,0
Exp/Cntr(USF)=0,0
Exp/Cntr=0.3,0.1

Type RM Length L Ch R = 1 ,75879   ,210.6,212.9,209.7
XS GIS Cut Line= 2
2315087.71723974612996.9748640152314652.04169668612664.861540207
#Sta/Elev= 30
       0 3065.45    56.6  3049.9    69.8 3047.61      95 3040.78   110.8 3033.04
   135.2 3031.42   145.3  3025.3   170.4 3014.45   190.7  3007.7   225.8 3001.11
     266 2999.08   293.5 3000.55   301.2 2998.92   304.9 2998.07   326.4 2997.53
   336.4 2998.96   349.4 3003.04   364.8 3004.17     382 3009.75   401.8 3009.68
   424.8 3015.56   428.5 3018.28     442  3031.6   472.2 3048.63   482.3 3056.35
   497.4 3065.79   507.5 3073.21   517.5 3078.99   532.6 3091.45   547.8  3099.5
#Mann= 6 ,-1,0
       0     .06       0     150      .1       0   301.2    .045       0
   336.4      .1       0     350     .06       0     480      .1       0
Bank Sta=301.2,336.4
XS Rating Curve= 0 ,0
Exp/Cntr(USF)=0,0
Exp/Cntr=0.3,0.1

Type RM Length L Ch R = 1 ,75666   ,205.5,204.8,200.5
XS GIS Cut Line= 3
2315197.08491109612913.9693743092315083.48374485612734.692533833
2314794.15577457612528.790420018
#Sta/Elev= 30
       0 3073.41      36 3062.92    67.2 3052.43   109.9 3044.07   119.3 3036.36
   124.1 3034.02   160.7 3034.61   175.2 3031.15   190.4 3024.61   204.1 3015.89
   218.6 3008.75     231 3004.02   250.7 3001.56   298.9 3004.78   330.4 2999.13
   352.8 2997.71   359.1 2999.16   368.5 3000.31     393 3000.12   412.7 3001.39
   428.7 3008.87     448 3010.69   456.3 3012.98   468.1 3022.61   488.2 3033.01
     506 3044.57   515.8 3046.07   519.7 3047.83   559.8 3074.05   567.4 3078.04
#Mann= 7 ,-1,0
       0      .1       0      10     .06       0     170      .1       0
   330.4    .045       0   359.1      .1       0  432.24     .06       0
  552.24      .1       0
Bank Sta=330.4,359.1
XS Rating Curve= 0 ,0
Exp/Cntr(USF)=0,0
Exp/Cntr=0.3,0.1

Type RM Length L Ch R = 1 ,75461   ,263.8,257.7,232.3
XS GIS Cut Line= 3
2315230.56168009612841.6315351372315105.57279479612502.375989312
2314882.37835674612384.529326025
#Sta/Elev= 30
       0 3057.82    42.7 3049.55    55.9 3041.18    81.5 3042.27   102.8 3031.72
   136.2 3030.03     158    3025   179.8 3022.41   210.9 3017.02   226.4 3015.77
   257.7 3010.19   273.3 3006.26   279.5 3006.01   291.9 3009.56   326.2 3008.17
   398.4 3001.94   419.5 2998.28   426.5 2997.31   457.9 2998.43   467.2 3001.24
   480.7 3009.41   498.8 3011.26   512.4 3022.05   530.5  3033.5   558.8 3056.97
   573.6 3066.77   584.8 3071.32   593.8  3077.1   602.9 3084.59   613.9 3089.76
#Mann= 7 ,-1,0
       0      .1       0      40     .06       0     150      .1       0
   419.5    .045       0   457.9      .1       0  471.55     .06       0
  591.55      .1       0
Bank Sta=419.5,457.9
XS Rating Curve= 0 ,0
Exp/Cntr(USF)=0,0
Exp/Cntr=0.3,0.1

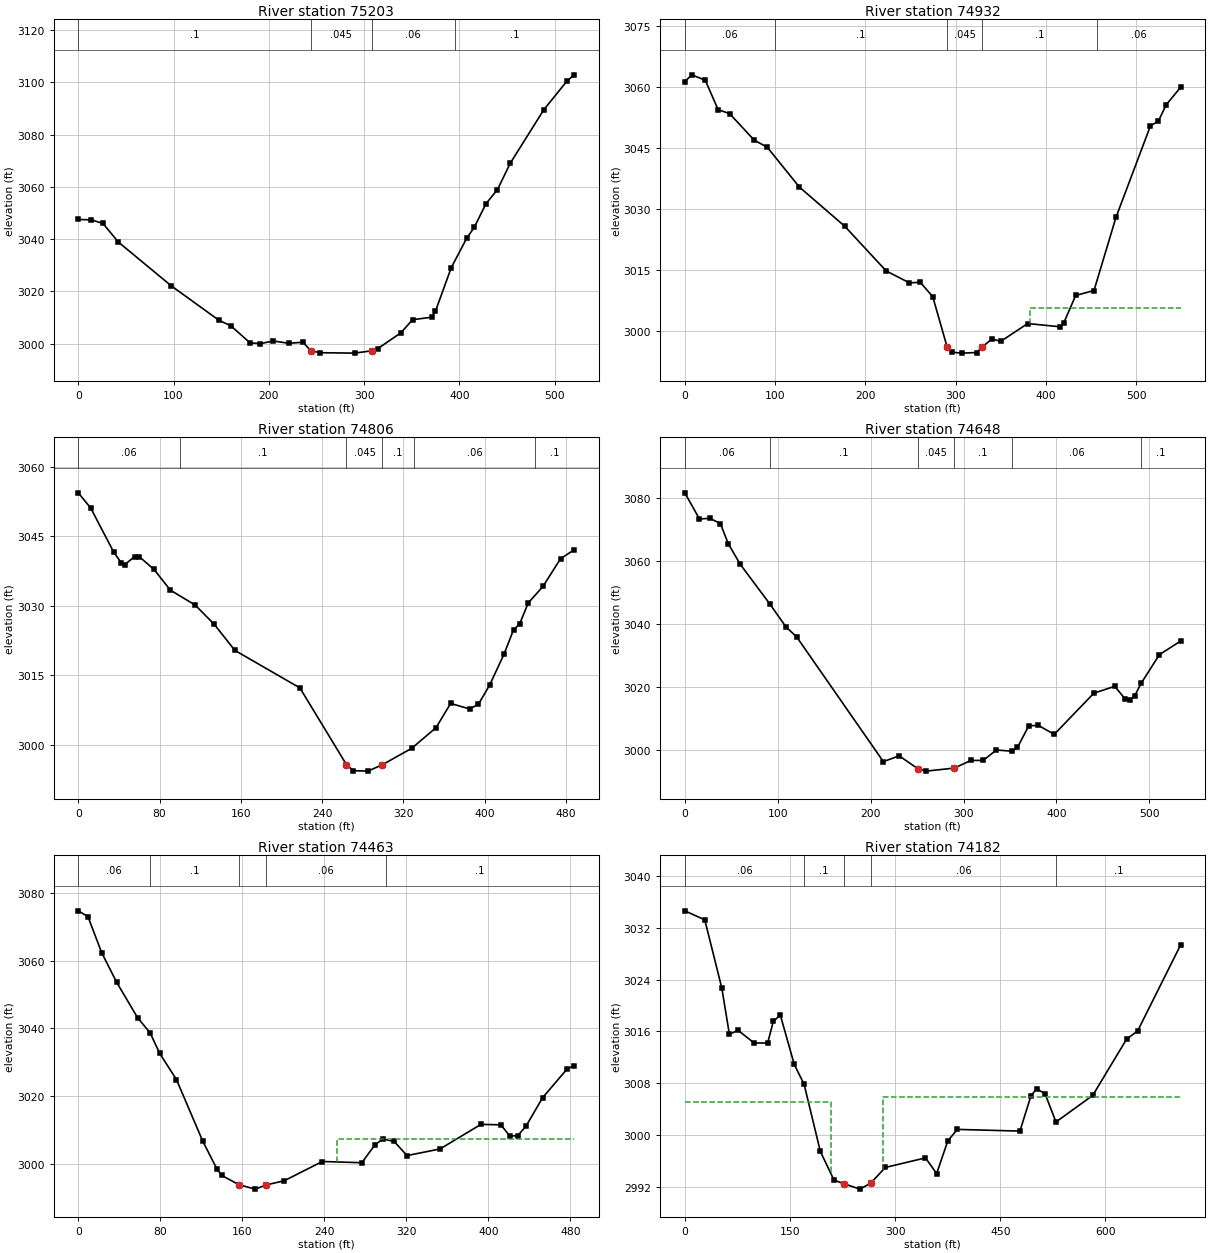
Type RM Length L Ch R = 1 ,75203   ,301.3,271.2,242.4
XS GIS Cut Line= 3
2315397.66197024612289.1629599742315028.45817995 612223.48728574
2314884.68170392612246.562522633
#Sta/Elev= 30
       0 3047.52    13.7 3047.37    25.9 3045.98    42.1 3038.85    97.8 3022.06
   147.8 3008.91     160 3006.87   180.3 3000.31     191    3000   204.8 3001.03
   220.9 3000.14   235.8 3000.55     244 2997.35   253.4 2996.54     290 2996.38
   308.2 2997.28   314.3 2998.07   338.7 3004.16   350.9 3009.16   371.2 3010.13
     375 3012.45   391.5 3029.04   407.7 3040.29   415.8 3044.56     428 3053.54
   440.1 3058.96   453.5 3069.04   488.7 3089.48     513 3100.45   520.6 3102.86
#Mann= 4 ,-1,0
       0      .1       0     244    .045       0   308.2     .06       0
     395      .1       0
Bank Sta=244,308.2
XS Rating Curve= 0 ,0
Exp/Cntr(USF)=0,0
Exp/Cntr=0.3,0.1

Type RM Length L Ch R = 1 ,74932   ,125.9,126.3,128.8
XS GIS Cut Line= 3
2315382.46564871611803.878875394 2315070.9102726612032.046663917
2314921.58069286612096.597821655
#Sta/Elev= 30
       0 3061.27     7.8 3062.91    22.7 3061.58    36.9 3054.35    49.6  3053.4
    76.7  3046.9    91.3 3045.14   126.8 3035.37   177.2 3025.72   222.9 3014.79
   248.7 3011.85   260.7    3012   274.5 3008.45   290.4 2996.12   295.4 2994.84
   306.8 2994.61   323.1 2994.75   328.8 2996.06     340 2998.06   349.9 2997.52
   379.6 3001.87   415.3 3001.08   419.7 3002.11   432.7 3008.76     453 3009.98
   477.3 3027.91   515.5  3050.4   524.2 3051.52     533 3055.59   548.9 3059.84
#Mann= 5 ,-1,0
       0     .06       0     100      .1       0   290.4    .045       0
   328.8      .1       0  456.17     .06       0
#XS Ineff= 2 , 0
                           382.3         3005.79
Permanent Ineff=
       F       F
Bank Sta=290.4,328.8
XS Rating Curve= 0 ,0
Exp/Cntr(USF)=0,0
Exp/Cntr=0.3,0.1

Type RM Length L Ch R = 1 ,74806   ,164.3,157.4,151.7
XS GIS Cut Line= 2
2315282.39796313611737.9836614792314874.54479353 612006.09431082
#Sta/Elev= 30
       0 3054.32    12.2 3051.04    34.9 3041.49    42.2 3039.25    45.7 3038.82
    55.3 3040.55    60.1 3040.52    74.5 3037.79    90.6 3033.32     115 3030.11
   133.9 3025.92   154.1 3020.32   218.1 3012.23   263.9 2995.69   270.7 2994.36
   285.1 2994.27   299.4 2995.66   328.2  2999.2   352.1 3003.64   366.5 3008.88
   385.2 3007.68   393.8 3008.69   404.8 3012.79   419.1 3019.53   428.5 3024.82
   434.3 3025.97   442.9 3030.56   457.4 3034.13   474.7  3040.1   488.1 3042.02
#Mann= 6 ,-1,0
       0     .06       0     100      .1       0   263.9    .045       0
   299.4      .1       0     330     .06       0     450      .1       0
Bank Sta=263.9,299.4
XS Rating Curve= 0 ,0
Exp/Cntr(USF)=0,0
Exp/Cntr=0.3,0.1

Type RM Length L Ch R = 1 ,74648   ,193.6,185.2,179.2
XS GIS Cut Line= 2
2315163.35956486611570.2805798452314776.40559235611937.709351911
#Sta/Elev= 30
       0 3081.55    15.8 3073.25    26.9 3073.48    38.3 3071.81    46.7 3065.48
    59.6 3058.92    91.3 3046.41   108.8 3039.07   120.4 3035.88   213.7 2996.34
   230.7 2998.18   250.5 2994.15   259.8 2993.33   290.1  2994.3   307.8 2996.71
   321.2 2996.73   335.3 3000.03   351.9 2999.65     358 3000.83   370.2 3007.71
   380.6  3007.8   397.6 3004.99   440.2 3018.03   462.7 3020.22     474 3016.15
   478.8  3015.8   484.3 3017.27     491 3021.13   510.8 3030.26   533.6 3034.56
#Mann= 6 ,-1,0
       0     .06       0    91.3      .1       0   250.5    .045       0
   290.1      .1       0   351.9     .06       0     491      .1       0
Bank Sta=250.5,290.1
XS Rating Curve= 0 ,0
Exp/Cntr(USF)=0,0
Exp/Cntr=0.3,0.1

Type RM Length L Ch R = 1 ,74463   ,333.1,280.8,225.8
BEGIN DESCRIPTION:
xs 4
END DESCRIPTION:
XS GIS Cut Line= 3
2314931.41674945 611473.122838192314770.55035985611741.233487531
2314760.80088169611911.849355294
#Sta/Elev= 30
       0 3074.75     9.4 3073.03    22.8 3062.35    37.4  3053.6    57.8 3043.14
      70 3038.67    79.4 3032.56    95.7 3024.86   121.3 3006.66   135.3 2998.33
     140 2996.49   156.9 2993.71   172.7 2992.45   183.2  2993.7   200.7 2994.91
     238 3000.62   276.5 3000.26   289.3 3005.54   296.9 3007.24   307.9  3006.6
   320.6 3002.37   352.8 3004.33   392.7  3011.6   412.1 3011.47   420.8 3008.17
   428.6 3008.25   436.8 3011.15   452.8 3019.48   476.9 3028.05   483.6 3028.93
#Mann= 5 ,-1,0
       0     .06       0      70      .1       0   156.9    .045       0
   183.2     .06       0     300      .1       0
#XS Ineff= 2 , 0
                          252.11         3007.39
Permanent Ineff=
       F       F
Bank Sta=156.9,183.2
XS Rating Curve= 0 ,0
Exp/Cntr(USF)=0,0
Exp/Cntr=0.5,0.3

Type RM Length L Ch R = 1 ,74182   ,91.2,103,118.2
BEGIN DESCRIPTION:
xs 3
END DESCRIPTION:
XS GIS Cut Line= 6
2314459.01078347611340.6711471192314452.28362415611403.880220531
2314481.63127844611447.9017019612314510.57071404611479.563518505
2314753.74821052 611685.465632322314744.87311941611914.442983027
#Sta/Elev= 30
       0 3034.63    28.5 3033.24    52.8 3022.69    63.6 3015.55      76 3016.16
    98.8 3014.21   118.2  3014.2   126.2 3017.53   136.2 3018.54   156.1  3010.9
   170.2 3007.81   193.3 2997.46   212.8 2993.01     227 2992.45   249.8 2991.62
   265.2 2992.54     286 2994.97   343.3 2996.45   359.2 2994.02   375.2  2999.1
   388.8 3000.85     478 3000.59   493.8 3006.06   501.8 3007.12   513.8 3006.37
   529.4    3002   581.8  3006.1   630.2 3014.81   645.9 3016.07   707.2 3029.36
#Mann= 5 ,-1,0
       0     .06       0   170.2      .1       0     227    .045       0
   265.2     .06       0   529.4      .1       0
#XS Ineff= 2 , 0
             209 3005.04     283         3005.88
Permanent Ineff=
       F       F
Bank Sta=227,265.2
XS Rating Curve= 0 ,0
Exp/Cntr(USF)=0,0
Exp/Cntr=0.5,0.3