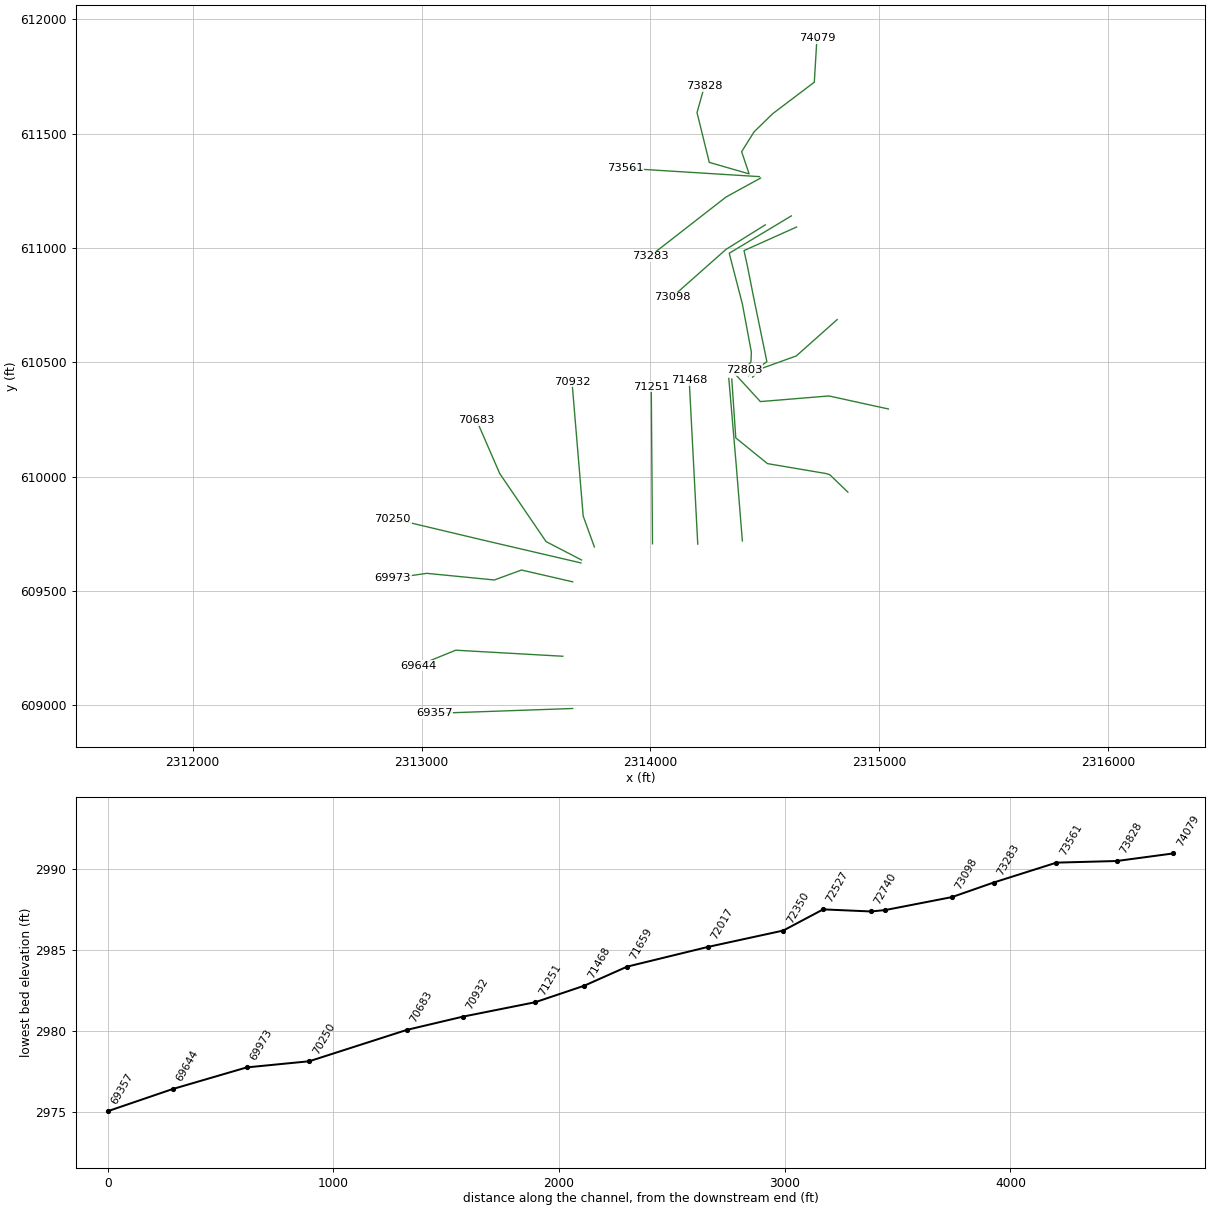
HEC-RAS study WFGRNBRRRV.prj: WFGRNBRRRV

--- WFGRNBRRRV.g01 (geometry) --- (continued)

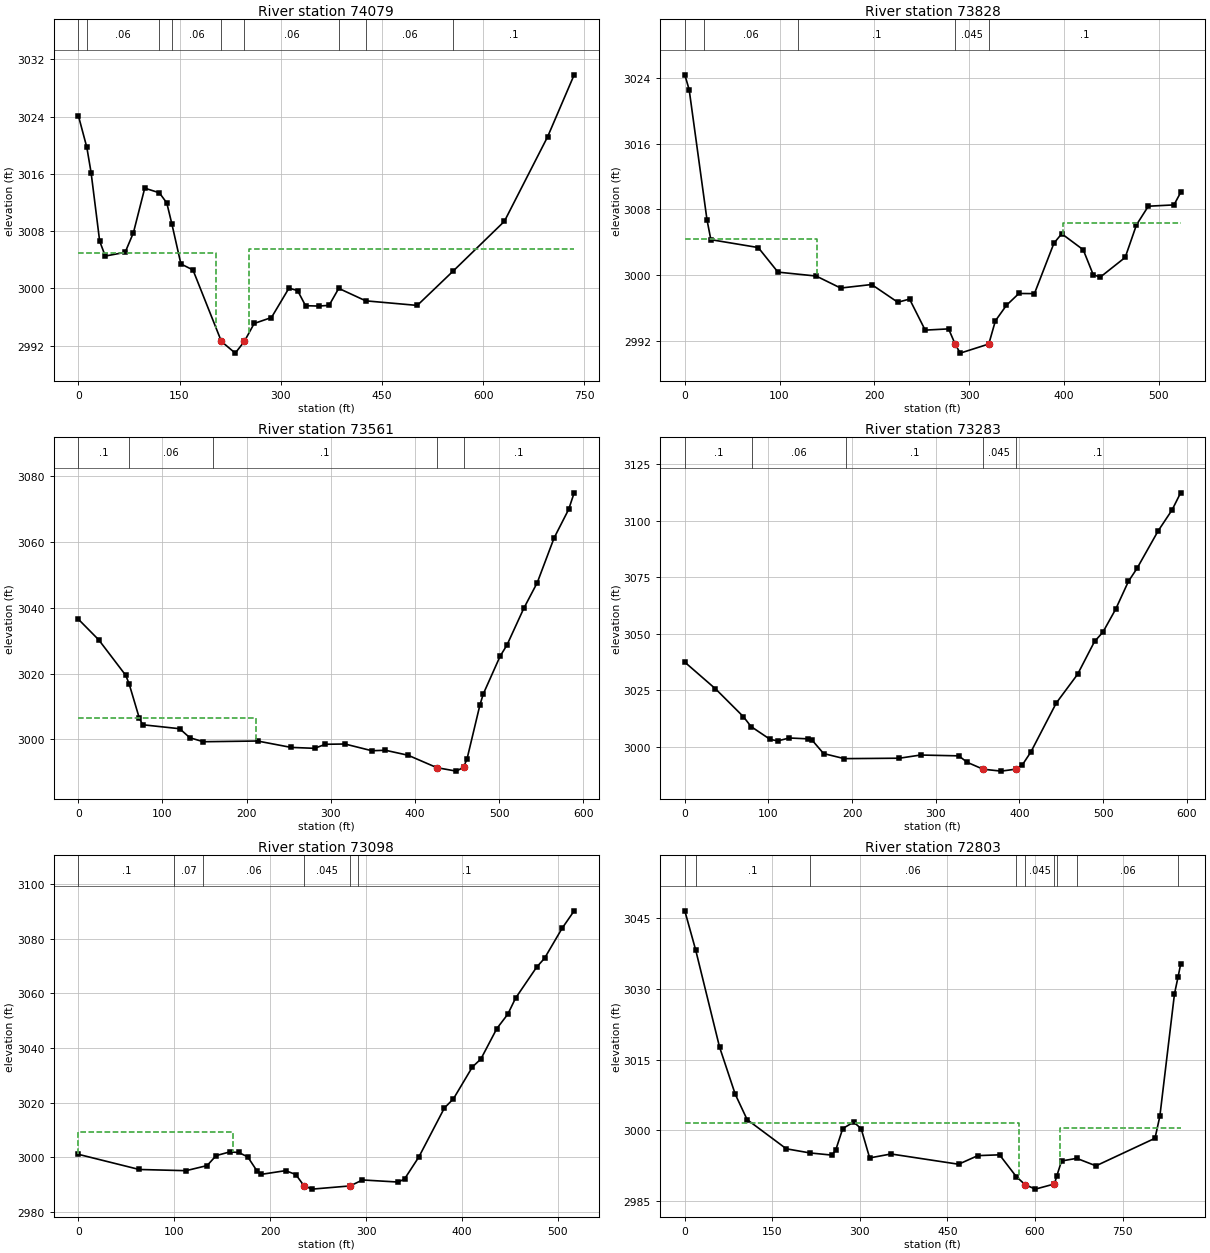
Type RM Length L Ch R = 1 ,74079   ,218.7,251.6,284.4
BEGIN DESCRIPTION:
xs 2
END DESCRIPTION:
XS GIS Cut Line= 6
2314430.27288344611327.3666932852314398.82896813611420.650308695
2314453.33175466611507.6451410442314535.08593446611587.303059821
2314716.41251273611724.6081566612314727.94194834611916.416040033
#Sta/Elev= 30
       0 3024.14    12.6 3019.69    18.9 3016.18    31.6 3006.61    39.9 3004.52
    69.4 3005.04    81.7  3007.8    98.4    3014   120.1 3013.35   131.1 3011.93
   138.6 3009.01     152 3003.42   169.9 3002.58  212.03  2992.6   232.5 2990.97
  246.01  2992.6   260.6 2995.11   286.2 2995.94   312.2 3000.05     325 2999.69
   336.7 2997.59   356.7 2997.54   371.6 2997.64   385.9 3000.01   425.9 2998.27
   502.3 2997.63   555.3 3002.41   631.4 3009.37   695.5 3021.18   734.8 3029.82
#Mann= 9 ,-1,0
       0      .1       0    12.6     .06       0   120.1      .1       0
   138.6     .06       0  212.03    .045       0  246.01     .06       0
   385.9      .1       0   425.9     .06       0   555.3      .1       0
#XS Ineff= 2 , 0
             204    3005     253          3005.5
Permanent Ineff=
       F       F
Bank Sta=212.03,246.01
XS Rating Curve= 0 ,0
Exp/Cntr(USF)=0,0
Exp/Cntr=0.5,0.3

Type RM Length L Ch R = 1 ,73828   ,229.7,266.7,309.2
BEGIN DESCRIPTION:
xs 1
END DESCRIPTION:
XS GIS Cut Line= 4
2314430.63281414611323.9093564462314257.43393022611373.904910567
2314203.86726509611591.7426820972314236.00726417611706.018234375
#Sta/Elev= 30
       0 3024.37     4.6 3022.57    23.4 3006.74    27.5 3004.31    77.5 3003.35
    98.3 3000.36   138.7 2999.88   164.5 2998.42   197.2 2998.85   224.8 2996.69
   237.2 2997.08   253.7  2993.3   278.4 2993.45  285.41 2991.58   290.7  2990.5
  320.84 2991.61   327.8 2994.43   339.4 2996.31   352.6 2997.76     369 2997.74
   389.6 3003.88   397.8 3005.03   420.5 3003.08     431 3000.06   438.4 2999.74
   464.8 3002.15   476.7 3006.11   489.2 3008.38   516.3 3008.54   523.3 3010.05
#Mann= 5 ,-1,0
       0      .1       0      20     .06       0     120      .1       0
  285.41    .045       0  320.84      .1       0
#XS Ineff= 2 , 0
          139.53 3004.34  399.21         3006.31
Permanent Ineff=
       F       F
Bank Sta=285.41,320.84
XS Rating Curve= 0 ,0
Exp/Cntr(USF)=0,0
Exp/Cntr=0.3,0.1

Type RM Length L Ch R = 1 ,73561   ,259.8,278.3,305
XS GIS Cut Line= 2
2314476.39062589611311.6447356312313888.38940965611348.329303489
#Sta/Elev= 30
       0 3036.51    24.3 3030.22    56.3 3019.48    60.3 3016.92    72.4 3006.53
    76.4 3004.47   120.4 3003.27   132.5 3000.53   148.5 2999.32   212.9 2999.54
   252.7  2997.6   280.7 2997.32   293.5 2998.55   316.8 2998.63   348.7 2996.59
   364.9 2996.73   391.8 2995.22     426 2991.45   449.1  2990.4  457.71 2991.57
   461.9 2994.19   477.1 3010.44   481.1  3013.8   501.2 3025.31   509.2 3028.62
   529.2 3039.77   545.3 3047.62   565.3 3061.18   582.6 3069.84   589.1 3074.85
#Mann= 5 ,-1,0
       0      .1       0      60     .06       0     160      .1       0
     426    .045       0  457.71      .1       0
#XS Ineff= 2 , 0
           211.3 3006.59
Permanent Ineff=
       F       F
Bank Sta=426,457.71
XS Rating Curve= 0 ,0
Exp/Cntr(USF)=0,0
Exp/Cntr=0.3,0.1

Type RM Length L Ch R = 1 ,73283   ,182.2,184.6,186.7
XS GIS Cut Line= 3
2314481.63127844 611305.355952572314330.73930461611222.527762496
2313998.97364842610964.066542603
#Sta/Elev= 30
       0 3037.42    36.6 3025.64    70.1 3013.26    79.2 3008.91     102 3003.22
   111.2 3002.56   124.9 3003.85   147.7 3003.45   152.2 3002.88   165.9 2996.95
   190.6  2994.7   256.5 2994.89   281.9  2996.3   327.5 2995.93   337.6 2993.07
   356.6 2990.02   378.2 2989.17   395.6 2990.04   403.6 2991.98   413.7 2997.66
   444.1 3019.36   469.5 3032.03   489.8 3046.58   499.8  3050.7   515.1 3060.91
   530.3 3073.19   540.5  3078.9   565.8 3095.53   582.5 3104.84   592.7  3112.4
#Mann= 5 ,-1,0
       0      .1       0      80     .06       0  192.13      .1       0
   356.6    .045       0   395.6      .1       0
Bank Sta=356.6,395.6
XS Rating Curve= 0 ,0
Exp/Cntr(USF)=0,0
Exp/Cntr=0.3,0.1

Type RM Length L Ch R = 1 ,73098   ,68.7,294.8,336.5
BEGIN DESCRIPTION:
xs 4
END DESCRIPTION:
XS GIS Cut Line= 3
2314502.05503432611100.714918403 2314330.6417059610993.581588142
2314094.94837933610784.671594134
#Sta/Elev= 30
       0 3001.03    63.5 2995.47   112.3 2995.03   134.3  2996.9   143.7 3000.55
   157.8  3001.9   167.3  3001.7   176.7 3000.07   186.2    2995   190.9 2993.69
   216.1 2995.04   226.8 2993.63   235.3 2989.51   243.8 2988.27   283.5 2989.45
   296.3 2991.63   333.7 2990.86   340.2 2991.99   355.1 3000.03   381.8 3018.03
   391.2 3021.37     411 3033.06   419.8 3035.95   436.5 3047.14   447.9 3052.39
     456 3058.27     478 3069.63   486.2 3072.88   504.5 3083.85   517.1 3090.27
#Mann= 6 ,-1,0
       0      .1       0     100     .07       0     130     .06       0
   235.3    .045       0   283.5     .06       0  292.14      .1       0
#XS Ineff= 2 , 0
          161.58 3009.25
Permanent Ineff=
       F       F
Bank Sta=235.3,283.5
XS Rating Curve= 0 ,0
Exp/Cntr(USF)=0,0
Exp/Cntr=0.5,0.3

Type RM Length L Ch R = 1 ,72803   ,260.8,63.4,58.7
BEGIN DESCRIPTION:
xs 3
END DESCRIPTION:
XS GIS Cut Line= 6
2314616.07952744611139.8616330142314344.68644012610976.644448889
2314402.29460246610753.5810654852314441.34500336610544.128915225
2314439.56998513610501.5284778842314409.39467535610466.028113433
#Sta/Elev= 30
       0 3046.61    18.6  3038.3    59.5 3017.67    86.4 3007.64   106.8 3002.24
   173.9 2996.04   214.4 2995.16   251.9  2994.7   258.4 2995.72   270.6 3000.35
   289.3 3001.72   302.1 3000.32   316.7  2994.1   353.3 2994.94     469 2992.76
     502 2994.59   539.2 2994.76   567.9 2990.12     583 2988.42   600.5 2987.47
   633.22988.568   637.2 2990.23   645.4 2993.45   671.4 2994.01   704.4 2992.42
   805.5 2998.28   813.8 3002.95   838.9 3028.98   845.1 3032.62   849.4 3035.24
#Mann= 9 ,-1,0
       0     .06       0    18.6      .1       0   214.4     .06       0
   567.9      .1       0     583    .045       0   633.2      .1       0
   637.2     .07       0   671.4     .06       0   845.1      .1       0
#XS Ineff= 2 , 0
             573 3001.42     643         3000.55
Permanent Ineff=
       F       F
Bank Sta=583,633.2
XS Rating Curve= 0 ,0
Exp/Cntr(USF)=0,0
Exp/Cntr=0.5,0.3

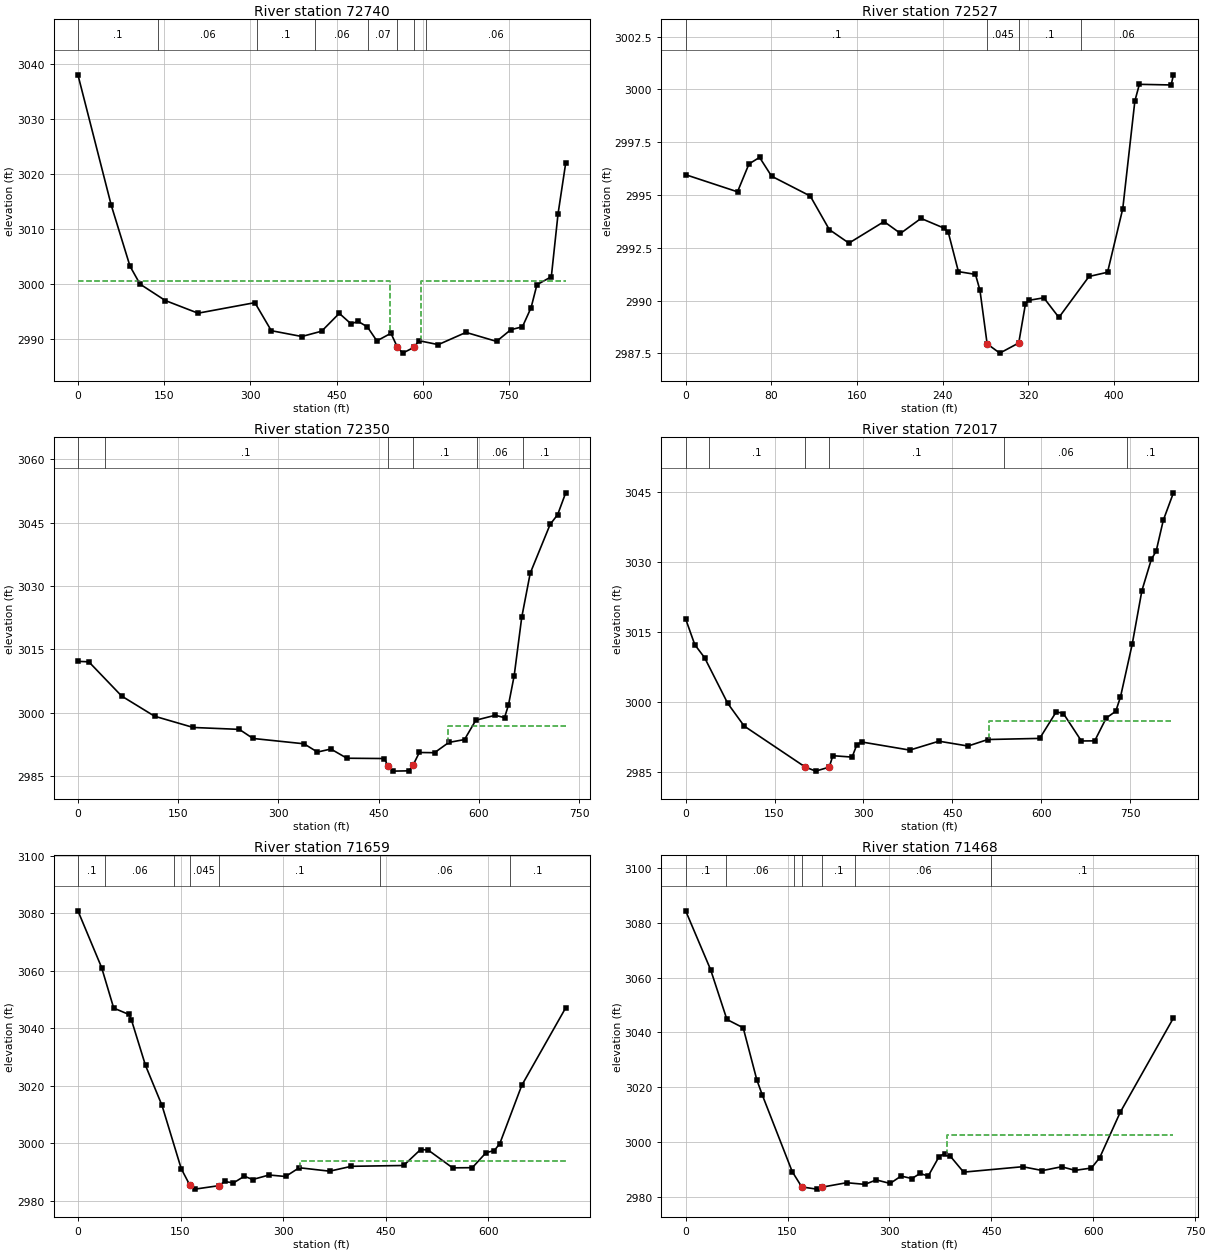
Type RM Length L Ch R = 1 ,72740   ,253.1,212.6,170.5
BEGIN DESCRIPTION:
xs 2
END DESCRIPTION:
XS GIS Cut Line= 6
2314638.83504478611091.1873685882314409.25418075610988.193775814
2314424.37103324610919.1769353152314450.22009447610788.858835923
2314509.09227693610502.8289663142314428.36115651610441.138314168
#Sta/Elev= 30
       0 3038.11      58 3014.33    90.6 3003.23   108.1 2999.96     152 2996.97
     209 2994.66   307.9 2996.58   336.5 2991.47   389.6 2990.41   424.1 2991.38
   454.8 2994.63   475.2 2992.72   487.5 2993.17   503.7 2992.16   520.2 2989.61
   544.7    2991   555.7 2988.51   565.1 2987.38   584.32988.408   593.7 2989.64
   627.1 2988.93   675.3 2991.16   728.4 2989.52   753.3 2991.65   773.5 2992.18
   788.6 2995.68   798.7 2999.84   823.8 3001.31   835.5 3012.79   848.8 3022.02
#Mann= 8 ,-1,0
       0      .1       0     140     .06       0  311.62      .1       0
  412.28     .06       0  505.13     .07       0   555.7    .045       0
   584.3     .07       0  605.13     .06       0
#XS Ineff= 2 , 0
           543.7 3000.55   596.3         3000.55
Permanent Ineff=
       F       F
Bank Sta=555.7,584.3
XS Rating Curve= 0 ,0
Exp/Cntr(USF)=0,0
Exp/Cntr=0.5,0.3

Type RM Length L Ch R = 1 ,72527   ,182.4,176.9,168.9
BEGIN DESCRIPTION:
xs 1
END DESCRIPTION:
XS GIS Cut Line= 4
2314816.31280308610686.4660413952314637.75725265610527.551601509
2314484.19947927610472.1993808742314446.70281368610434.702715283
#Sta/Elev= 30
       0 2995.96    48.4 2995.15    59.1 2996.47      69 2996.78    80.2 2995.89
   116.3 2994.95   134.1 2993.36   152.4 2992.72   185.2 2993.74   200.5 2993.18
   219.7 2993.89   240.7 2993.44     245 2993.26   254.6 2991.37   270.5 2991.24
   274.7 2990.49   281.4 2987.95   293.2 2987.51   310.9 2987.99   317.2 2989.85
   320.3 2990.01   334.3 2990.13   348.4  2989.2   376.5 2991.14   393.8 2991.34
     408 2994.35   419.3 2999.45   423.5 3000.24   453.2 3000.21   455.3 3000.69
#Mann= 4 ,-1,0
       0      .1       0   281.4    .045       0   310.9      .1       0
  369.03     .06       0
Bank Sta=281.4,310.9
XS Rating Curve= 0 ,0
Exp/Cntr(USF)=0,0
Exp/Cntr=0.3,0.1

Type RM Length L Ch R = 1 ,72350   ,341.2,333.1,323
XS GIS Cut Line= 4
2315040.08109113 610295.575837582314780.13825665610352.528000169
 2314480.7656503610327.8541654632314370.34427445610448.277931208
#Sta/Elev= 30
       0 3012.18    16.3 3012.07    65.4 3003.97   114.6  2999.2   172.6 2996.53
   241.5 2996.08     262 2993.93   338.3 2992.67   358.4 2990.71   378.5 2991.43
   402.5 2989.25   458.7 2989.18   463.42987.529   470.8  2986.2   495.4 2986.27
   501.2 2987.54   510.9 2990.61   533.6 2990.56     555 2992.99   578.5 2993.67
   595.4 2998.25   624.5 2999.42   638.4 2998.85   644.3 3001.88   652.8 3008.78
   664.1 3022.59   676.8 3033.03   706.6 3044.58   717.9 3046.91   729.9 3052.06
#Mann= 6 ,-1,0
       0     .06       0      40      .1       0   463.4    .045       0
   501.2      .1       0   596.5     .06       0   666.5      .1       0
#XS Ineff= 2 , 0
                          554.03         2996.94
Permanent Ineff=
       F       F
Bank Sta=463.4,501.2
XS Rating Curve= 0 ,0
Exp/Cntr(USF)=0,0
Exp/Cntr=0.3,0.1

Type RM Length L Ch R = 1 ,72017   ,407.5,358.5,314
XS GIS Cut Line= 6
2314863.24785012609931.814317962  2314784.172804610007.954949745
2314768.27565204 610013.099413062314511.73423848610056.582260237
2314373.21975032610169.127988112 2314355.7877797610426.308557644
#Sta/Elev= 30
       0 3017.82    15.4 3012.31      32 3009.51      71 2999.72    98.7 2994.86
   201.52986.089   219.3 2985.19   242.2 2986.05   248.3  2988.5   280.8  2988.2
   288.9 2990.88     297 2991.44   378.1  2989.7   427.3 2991.61   476.4 2990.57
   509.8 2991.97   597.3 2992.21   625.3 2997.93   637.4 2997.52   667.6 2991.66
   690.1 2991.68   709.5 2996.58   725.6 2998.03   733.6 3001.11   753.3 3012.38
   769.7  3023.9   785.7 3030.64   793.7 3032.34   805.8    3039   822.9 3044.88
#Mann= 6 ,-1,0
       0     .06       0      40      .1       0   201.5    .045       0
   242.2      .1       0  536.68     .06       0  745.16      .1       0
#XS Ineff= 2 , 0
                          511.32            2996
Permanent Ineff=
       F       F
Bank Sta=201.5,242.2
XS Rating Curve= 0 ,0
Exp/Cntr(USF)=0,0
Exp/Cntr=0.3,0.1

Type RM Length L Ch R = 1 ,71659   ,191.3,190.2,189.5
XS GIS Cut Line= 3
2314402.06392607609718.6949580422314375.28059351610049.022726345
 2314342.7916704 610429.17616217
#Sta/Elev= 30
       0  3080.9    34.6 3061.16    52.3 3047.02    74.6  3044.8    78.3 3042.83
    98.8 3027.03   122.9 3013.12     151 2991.09   163.7 2985.29   171.1 2983.97
   205.9 2985.17   214.6 2986.64   227.2 2986.12   243.3 2988.48   255.3 2987.31
   279.4 2988.89   303.5 2988.37   323.5 2991.42   367.9 2990.22   399.8 2991.92
   476.1  2992.2   500.9 2997.77     512 2997.57   547.7 2991.38   576.5 2991.44
   596.5 2996.65   608.6 2997.41   616.6 2999.79   648.8 3020.13     713 3047.12
#Mann= 7 ,-1,0
       0      .1       0      40     .06       0     140      .1       0
   163.7    .045       0   205.9      .1       0  441.41     .06       0
  631.41      .1       0
#XS Ineff= 2 , 0
                          324.88         2993.86
Permanent Ineff=
       F       F
Bank Sta=163.7,205.9
XS Rating Curve= 0 ,0
Exp/Cntr(USF)=0,0
Exp/Cntr=0.3,0.1

Type RM Length L Ch R = 1 ,71468   ,218.3,217.2,219.2
XS GIS Cut Line= 2
2314207.04259798609704.5452959632314169.76721531 610421.65265787
#Sta/Elev= 30
       0 3084.34    36.7 3062.89    60.7 3044.71    84.7 3041.66   104.8 3022.64
   112.8 3017.16   156.8 2989.22   170.9 2983.59   192.9 2982.79   201.3 2983.53
     237 2985.13   263.8 2984.53   280.7 2986.15     301 2984.86   317.1 2987.56
   333.1 2986.66   345.1  2988.5   357.1 2987.57   373.1 2994.66   381.1 2995.77
   389.2 2994.93   409.2 2988.99   496.2 2990.97   525.3 2989.56   553.4 2990.95
   573.4 2989.64   597.4 2990.49   609.5 2994.23   639.8 3010.85   718.1 3045.23
#Mann= 7 ,-1,0
       0      .1       0      60     .06       0     160      .1       0
   170.9    .045       0   201.3      .1       0     250     .06       0
     450      .1       0
#XS Ineff= 2 , 0
                           384.9         3002.61
Permanent Ineff=
       F       F
Bank Sta=170.9,201.3
XS Rating Curve= 0 ,0
Exp/Cntr(USF)=0,0
Exp/Cntr=0.3,0.1

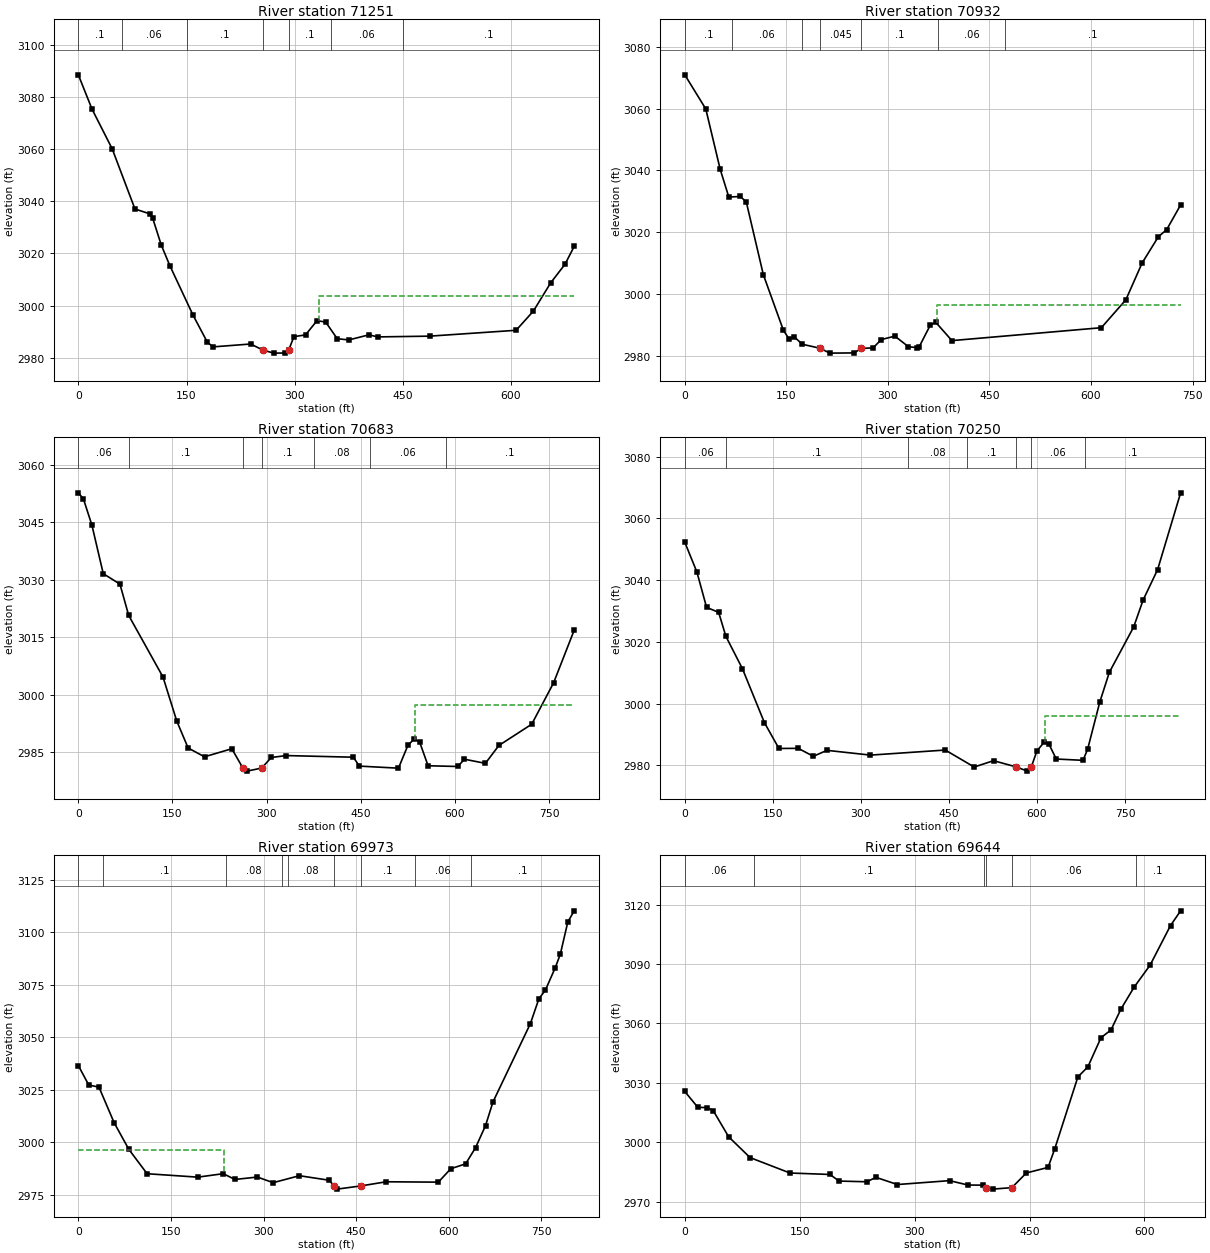
Type RM Length L Ch R = 1 ,71251   ,318.6,319.8,320.7
XS GIS Cut Line= 2
2314009.24171512609706.1960695112314003.88504861610393.634938683
#Sta/Elev= 30
       0 3088.49      19 3075.33      47 3060.08    78.5 3037.04      99  3035.2
     103 3033.61     115 3023.21     127 3015.25   158.8 2996.47     179  2985.9
     187 2984.17     239 2985.27   255.9 2982.94     271 2981.77     287 2981.81
  291.67 2982.98     299  2988.1     315 2988.75     331 2994.24     343 2993.66
     359  2987.3     375 2986.83     403 2988.79     415 2987.99     487 2988.28
     607 2990.53   630.9 2997.87     655 3008.74   674.8 3015.84   687.5 3022.68
#Mann= 7 ,-1,0
       0      .1       0      60     .06       0     150      .1       0
   255.9    .045       0  291.67      .1       0     350     .06       0
     450      .1       0
#XS Ineff= 2 , 0
                          333.63         3003.52
Permanent Ineff=
       F       F
Bank Sta=255.9,291.67
XS Rating Curve= 0 ,0
Exp/Cntr(USF)=0,0
Exp/Cntr=0.3,0.1

Type RM Length L Ch R = 1 ,70932   ,225.3,248.8,270.1
XS GIS Cut Line= 3
2313755.30816176609692.0504053762313706.48745922609827.021553318
2313657.53049425610413.874783569
#Sta/Elev= 30
       0 3070.96      31 3059.92    52.2 3040.44      65  3031.4      82 3031.58
    90.8 3029.84     116 3006.28   145.7 2988.24   153.7 2985.59   161.7 2986.14
   173.6 2983.75   199.5 2982.47   214.4 2980.88   250.1 2980.95   260.8  2982.4
   278.2 2982.59   290.2 2985.26   310.3 2986.38   330.3 2982.97   342.4 2982.65
   346.4    2983   362.4 2989.85   370.5  2990.9   394.6 2984.93   615.3 2989.11
   651.5 2998.14   675.5 3010.05   699.6 3018.58   711.7 3020.81   732.4 3028.85
#Mann= 7 ,-1,0
       0      .1       0      70     .06       0  173.53      .1       0
   199.5    .045       0   260.8      .1       0  373.53     .06       0
  473.53      .1       0
#XS Ineff= 2 , 0
                          371.83         2996.58
Permanent Ineff=
       F       F
Bank Sta=199.5,260.8
XS Rating Curve= 0 ,0
Exp/Cntr=0.3,0.1

Type RM Length L Ch R = 1 ,70683   ,409.5,432.8,448.8
XS GIS Cut Line= 4
2313699.37552126609635.0267261852313544.11392241609715.636294428
2313341.52066214610013.3643968572313240.10160925610247.135194623
#Sta/Elev= 30
       0 3052.67     8.1 3051.08    21.6 3044.26    39.7 3031.58    66.3 3028.85
    80.2 3020.69   134.9  3004.6   156.8 2993.13   174.9  2986.1     201  2983.8
   244.5  2985.9   262.4  2980.8   268.7 2980.06   292.12980.861   307.4 2983.62
   331.6 2984.12   438.1 2983.69   447.7 2981.37     510 2980.83   525.2 2986.85
   534.8 2988.38   543.6  2987.7   557.2 2981.46   604.6 2981.27     615 2983.17
   648.5 2982.09     670 2986.76   722.3  2992.3   757.2 3003.12   789.9 3016.82
#Mann= 7 ,-1,0
       0     .06       0      80      .1       0   262.4    .045       0
   292.1      .1       0  374.94     .08       0  464.94     .06       0
  585.06      .1       0
#XS Ineff= 2 , 0
                          536.34         2997.19
Permanent Ineff=
       F       F
Bank Sta=262.4,292.1
XS Rating Curve= 0 ,0
Exp/Cntr(USF)=0,0
Exp/Cntr=0.3,0.1

Type RM Length L Ch R = 1 ,70250   ,276,276.9,269.2
XS GIS Cut Line= 3
2313696.33997094609622.3363808632313266.80140561609722.578477749
2312874.00611457609815.981936251
#Sta/Elev= 30
       0 3052.27    20.7 3042.58    37.1 3031.18    57.7 3029.55      70 3021.78
    98.2  3011.3   135.7 2993.81   160.4 2985.46   193.2  2985.5     219 2982.93
   242.3 2984.85   316.4 2983.31   443.8 2984.95   493.1 2979.45     526  2981.5
     565 2979.47   583.6 2978.12   590.6 2979.58     600 2984.68   612.4 2987.51
   620.6  2986.8   632.9 2982.04   678.5 2981.62   686.4 2985.25   706.9 3000.39
   723.4 3010.16   764.8 3024.82   780.9 3033.56   805.6 3043.41   844.8 3068.28
#Mann= 7 ,-1,0
       0     .06       0      70      .1       0     380     .08       0
  481.08      .1       0     565    .045       0   590.6     .06       0
  681.08      .1       0
#XS Ineff= 2 , 0
                          612.96         2996.03
Permanent Ineff=
       F       F
Bank Sta=565,590.6
XS Rating Curve= 0 ,0
Exp/Cntr(USF)=0,0
Exp/Cntr=0.3,0.1

Type RM Length L Ch R = 1 ,69973   ,326.6,328.7,328.9
XS GIS Cut Line= 5
 2313660.6856953609539.6135527992313436.91071832609591.256458123
2313318.11784545609547.7548427072313023.10544355 609576.74398394
2312874.00391285609555.443765269
#Sta/Elev= 30
       0 3036.56    16.9 3027.28    33.4 3026.31      58 3009.35    81.8 2996.68
   111.4 2985.07   193.5 2983.44   234.7 2985.09   253.7 2982.34   290.1 2983.49
   315.6 2980.81   358.1 2984.13   406.3 2981.97   414.2 2979.32   419.1 2977.74
   457.92979.274   498.8 2981.24   583.2 2981.06   603.3 2987.44   627.4 2989.78
   643.5  2997.5   659.6 3007.95   671.7 3019.25   732.3 3056.54   746.1 3068.38
   756.6 3072.47   772.7 3083.23   780.8  3089.6   792.9 3104.89   803.2 3110.22
#Mann= 9 ,-1,0
       0     .06       0      40      .1       0  239.66     .08       0
  329.66      .1       0  339.66     .08       0   414.2    .045       0
   457.9      .1       0  546.16     .06       0  636.16      .1       0
#XS Ineff= 2 , 0
          236.62 2996.38
Permanent Ineff=
       F       F
Bank Sta=414.2,457.9
XS Rating Curve= 0 ,0
Exp/Cntr(USF)=0,0
Exp/Cntr=0.3,0.1

Type RM Length L Ch R = 1 ,69644   ,286.8,287.6,287.4
XS GIS Cut Line= 3
 2313617.2498918609214.1606513992313149.35931303609240.645822693
2312983.96052786609173.352654899
#Sta/Elev= 30
       0 3025.67    17.1 3017.64    29.1 3017.57    37.1 3016.03    57.2 3002.83
    85.2 2992.31   137.3 2984.53   189.4  2983.8   201.4 2980.47   237.5 2980.11
   249.5 2982.34   277.5 2978.72   345.6 2980.68   369.7 2978.46   389.7 2978.41
   393.7 2977.16   401.7  2976.4   426.9 2977.15   445.8 2984.55   474.2 2987.37
   482.9 2996.74   513.1 3033.03   526.1 3038.09   543.3 3052.85   556.3 3056.71
   569.2  3067.2   586.5 3078.33   607.3  3089.4     634 3109.42   647.2 3116.84
#Mann= 6 ,-1,0
       0     .06       0      90      .1       0     390     .06       0
   393.7    .045       0   426.9     .06       0  588.64      .1       0
Bank Sta=393.7,426.9
XS Rating Curve= 0 ,0
Exp/Cntr(USF)=0,0
Exp/Cntr=0.3,0.1

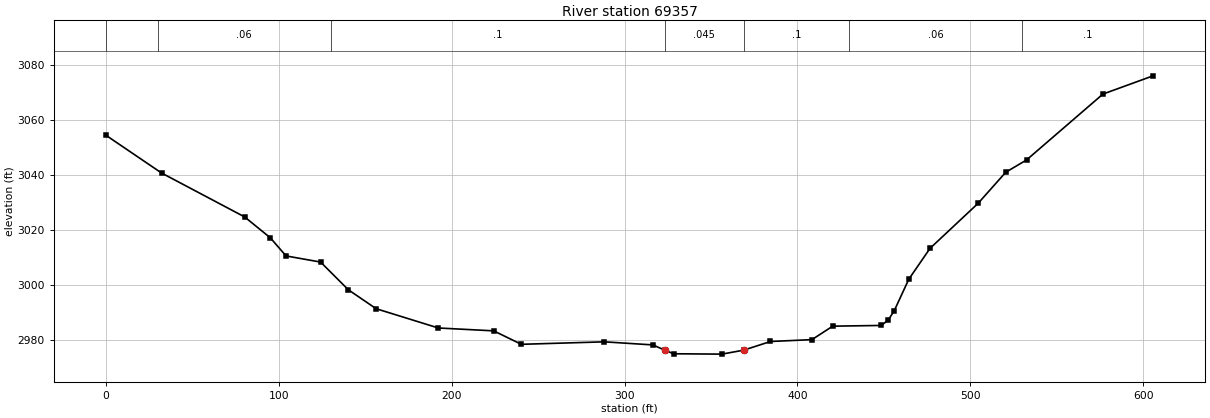
Type RM Length L Ch R = 1 ,69357   ,313.8,301,285.5
XS GIS Cut Line= 2
2313660.33698544608985.6629158342313055.05577155608964.362697163
#Sta/Elev= 30
       0  3054.4    32.2 3040.71    80.2  3024.8    95.1 3017.22   104.2 3010.64
   124.2 3008.41   140.2 2998.38   156.3  2991.5   192.3 2984.51   224.3 2983.47
   240.3 2978.59   288.3 2979.49   316.4 2978.37   323.2 2976.48   328.4 2975.16
   356.3 2975.03   368.9 2976.47   384.4 2979.61   408.4 2980.29   420.4 2985.17
   448.4 2985.43   452.4 2987.29     456 2990.77   464.4 3002.18   476.7 3013.39
   504.5 3029.71   520.5 3040.99   532.5 3045.43   576.7 3069.33   605.7 3075.95
#Mann= 7 ,-1,0
       0      .1       0      30     .06       0     130      .1       0
   323.2    .045       0   368.9      .1       0     430     .06       0
     530      .1       0
Bank Sta=323.2,368.9
XS Rating Curve= 0 ,0
Exp/Cntr(USF)=0,0
Exp/Cntr=0.3,0.1