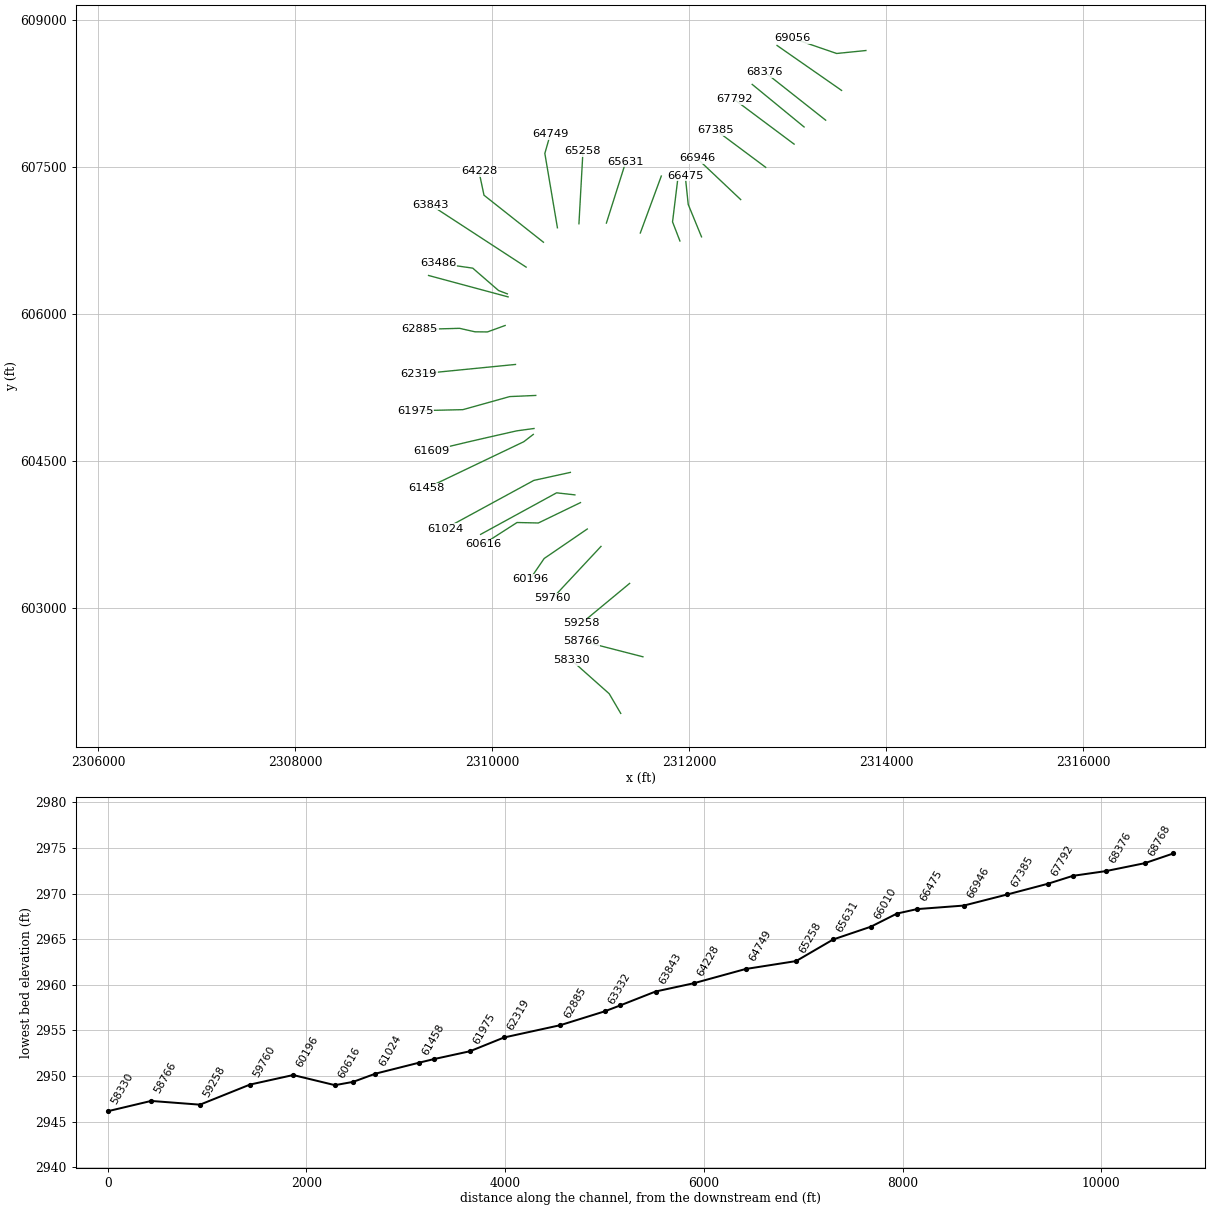
HEC-RAS study WFGRNBRRRV.prj: WFGRNBRRRV

--- WFGRNBRRRV.g01 (geometry) --- (continued)

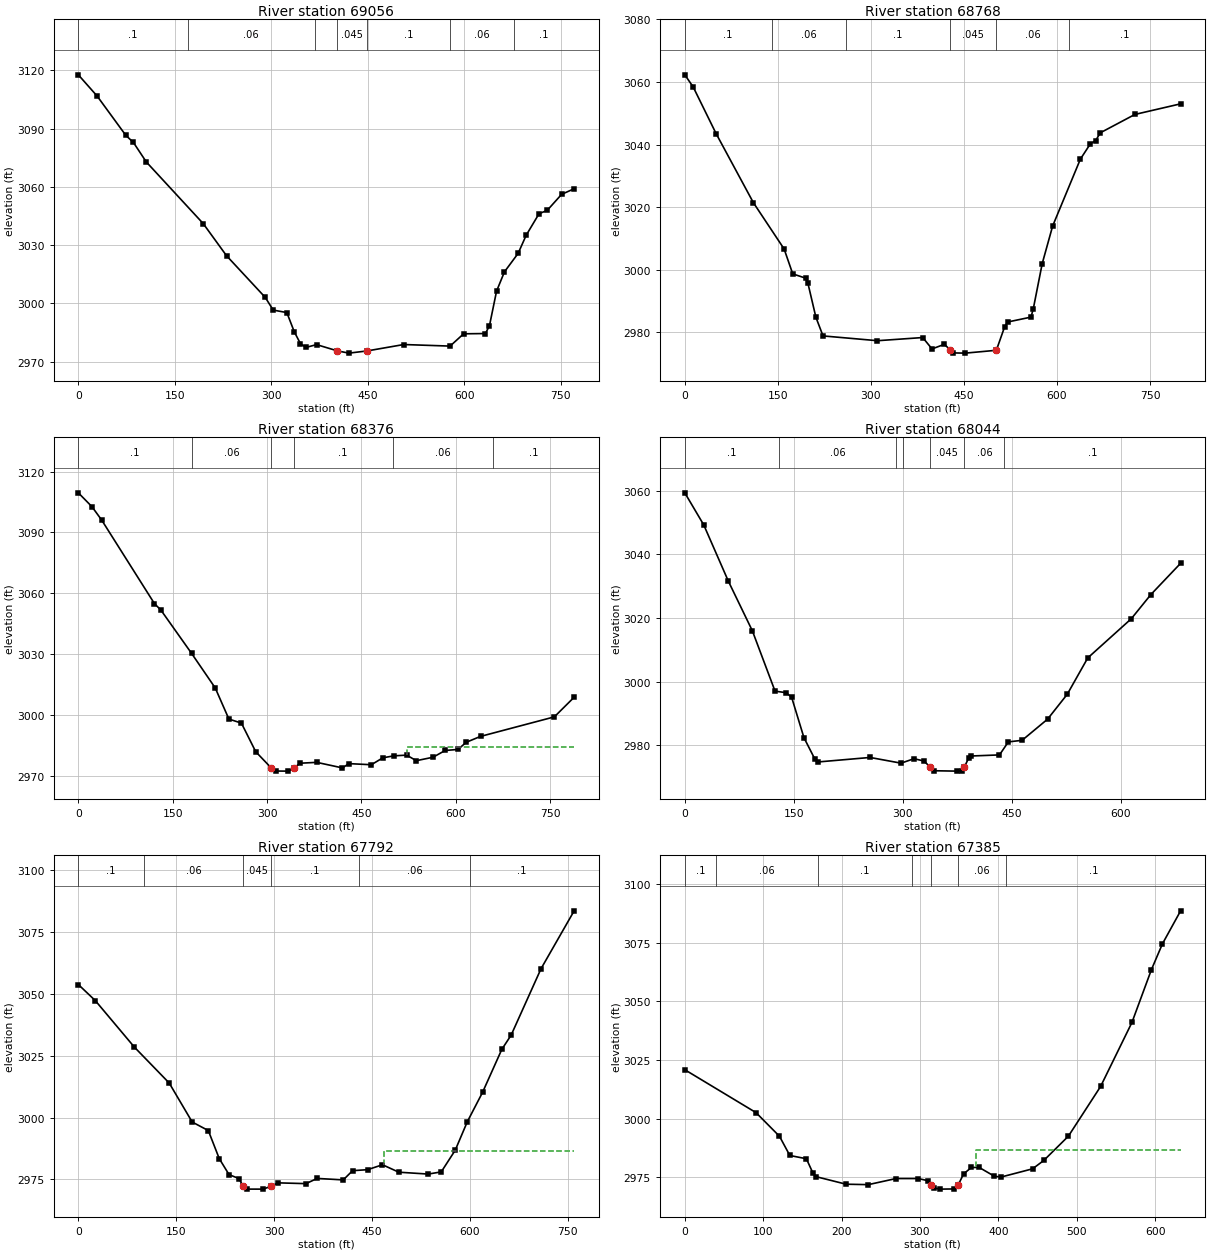
Type RM Length L Ch R = 1 ,69056   ,287.6,288,278.6
XS GIS Cut Line= 3
2313793.46335213608683.9098180012313497.03530896608653.734508218
2313049.73071688608808.161093579
#Sta/Elev= 30
       0 3117.74    29.2 3106.82    73.7 3086.64    85.7 3082.89   105.8 3072.84
   194.3  3041.1   230.5 3024.58   290.8 3003.08   303.1 2996.58   324.3  2995.3
   335.9 2985.37   345.4 2979.34   353.9 2977.34   370.6 2978.79  402.94 2975.57
   420.9 2974.41   448.9 2975.53   506.2 2978.84   578.2 2978.03   599.3 2984.36
   633.2  2984.5   639.5 2988.59   650.5 3006.33   662.8 3016.29     684 3025.76
   696.6 3035.13   716.6 3046.23   729.2  3047.9   751.7 3056.19   771.2 3059.07
#Mann= 7 ,-1,0
       0      .1       0     170     .06       0  367.96      .1       0
  402.94    .045       0   448.9      .1       0  577.96     .06       0
  677.96      .1       0
Bank Sta=402.94,448.9
XS Rating Curve= 0 ,0
Exp/Cntr(USF)=0,0
Exp/Cntr=0.3,0.1

Type RM Length L Ch R = 1 ,68768   ,376.8,391.8,396.5
XS GIS Cut Line= 2
 2313546.7358192608277.4306450392312891.75409508608735.385346455
#Sta/Elev= 30
       0 3062.28    13.5 3058.41    50.5 3043.48   110.5 3021.44   160.1 3006.62
     174 2998.66     195 2997.29   198.4 2995.72   211.3 2984.81   222.8 2978.84
   310.6 2977.31   383.5 2978.32   398.5 2974.68   418.4 2976.16   427.8 2974.37
   432.5 2973.41   452.2 2973.34   502.2 2974.25   515.6 2981.79   520.5 2983.29
     558 2984.85   561.8 2987.59   576.1 3001.95   592.9 3013.95   637.6 3035.33
   653.7 3040.23   662.3 3041.28   669.7 3043.75   725.5 3049.62   799.2 3053.01
#Mann= 6 ,-1,0
       0      .1       0     140     .06       0     260      .1       0
   427.8    .045       0   502.2     .06       0     620      .1       0
Bank Sta=427.8,502.2
XS Rating Curve= 0 ,0
Exp/Cntr(USF)=0,0
Exp/Cntr=0.3,0.1

Type RM Length L Ch R = 1 ,68376   ,316.9,332.2,328.2
XS GIS Cut Line= 2
2313385.20916094607973.902528985 2312767.5028195608463.807558406
#Sta/Elev= 30
       0 3109.52    21.7 3102.68    37.1 3096.12   121.1 3054.93   131.2 3051.82
     180 3030.49   217.7 3013.43   239.4 2998.11   259.3 2996.12   282.1 2982.02
     307 2973.96   314.3 2972.51   333.6 2972.47  342.42    2974   352.9 2976.37
   379.1 2976.79     420 2974.05   430.2 2976.16   465.9 2975.62   484.2 2979.03
   501.6 2979.99   522.1 2980.35   537.4 2977.61     564 2979.31   583.3 2982.64
   603.7 2983.15   616.8 2986.68   639.5 2989.57   756.9 2999.19   788.4 3008.87
#Mann= 6 ,-1,0
       0      .1       0     180     .06       0     307    .045       0
  342.42      .1       0     500     .06       0     660      .1       0
#XS Ineff= 2 , 0
                          522.98         2984.48
Permanent Ineff=
       F       F
Bank Sta=307,342.42
XS Rating Curve= 0 ,0
Exp/Cntr(USF)=0,0
Exp/Cntr=0.3,0.1

Type RM Length L Ch R = 1 ,68044   ,248.9,251.8,255.3
XS GIS Cut Line= 2
2313166.45951707 607904.570565632312639.72064329608338.460553185
#Sta/Elev= 30
       0 3059.32    26.1 3049.24      60 3031.55      93 3015.99   124.2 2997.06
   139.4 2996.58     147 2995.16     164 2982.44   179.2 2975.64   183.9 2974.84
     255 2976.24   297.6 2974.45   315.5 2975.85   329.4 2975.11   337.4 2973.26
     343 2972.07   374.3 2971.95   381.3  2972.1   384.7 2973.19     391 2976.22
   394.2  2976.7   433.1 2977.04   445.3 2981.13   464.2 2981.62   499.3 2988.27
   526.4 2996.09   554.6 3007.49   614.5 3019.79   641.4 3027.37   682.4  3037.2
#Mann= 7 ,-1,0
       0      .1       0     130     .06       0     290      .1       0
     300     .06       0   337.4    .045       0   384.7     .06       0
     440      .1       0
Bank Sta=337.4,384.7
XS Rating Curve= 0 ,0
Exp/Cntr(USF)=0,0
Exp/Cntr=0.3,0.1

Type RM Length L Ch R = 1 ,67792   ,409.7,407.1,406.1
XS GIS Cut Line= 2
2313064.89337819607729.6836377892312457.31614578608185.411507991
#Sta/Elev= 30
       0 3053.85    25.9 3047.37    85.8 3028.54   139.2    3014   174.4 2998.23
   199.1 2994.77   215.9  2983.4   230.9 2976.94   245.9 2975.37   252.5 2972.21
   259.1 2971.09     283 2971.08   295.2 2972.22   305.8 2973.62   348.7  2973.3
   365.9 2975.41   405.8 2974.81   420.1 2978.55     443 2978.94   465.9 2980.94
   490.9 2977.93   535.9 2977.17   555.9 2978.05   577.3 2986.81   595.9 2998.38
   619.1 3010.19   648.7 3027.62     663 3033.39   708.7 3060.22   759.5 3083.66
#Mann= 6 ,-1,0
       0      .1       0     100     .06       0   252.5    .045       0
   295.2      .1       0     430     .06       0     600      .1       0
#XS Ineff= 2 , 0
                          467.83         2986.38
Permanent Ineff=
       F       F
Bank Sta=252.5,295.2
XS Rating Curve= 0 ,0
Exp/Cntr=0.3,0.1

Type RM Length L Ch R = 1 ,67385   ,440.7,438.5,429.4
XS GIS Cut Line= 2
2312776.95134175 607492.912075132312270.46443958607871.851489769
#Sta/Elev= 30
       0 3020.84    90.9 3002.53   120.8 2992.45     134 2984.26   155.1 2982.87
   163.6 2976.68   167.4 2975.23   205.8 2972.01   234.1 2971.82   269.4 2974.42
   297.9 2974.42   310.7 2973.47   314.3 2971.83   317.9 2970.38   325.7 2969.91
   343.7 2969.99   348.8 2971.68   355.7  2976.4   365.6 2979.14   375.6 2979.16
   395.1 2975.38   403.7 2975.08   443.7 2978.57     458 2982.13   489.4 2992.49
   530.5 3013.69   570.5 3041.01   595.4 3063.57   609.4 3074.53   632.6  3088.6
#Mann= 7 ,-1,0
       0      .1       0      40     .06       0     170      .1       0
     290     .06       0   314.3    .045       0   348.8     .06       0
     410      .1       0
#XS Ineff= 2 , 0
                          371.89         2986.73
Permanent Ineff=
       F       F
Bank Sta=314.3,348.8
XS Rating Curve= 0 ,0
Exp/Cntr=0.3,0.1

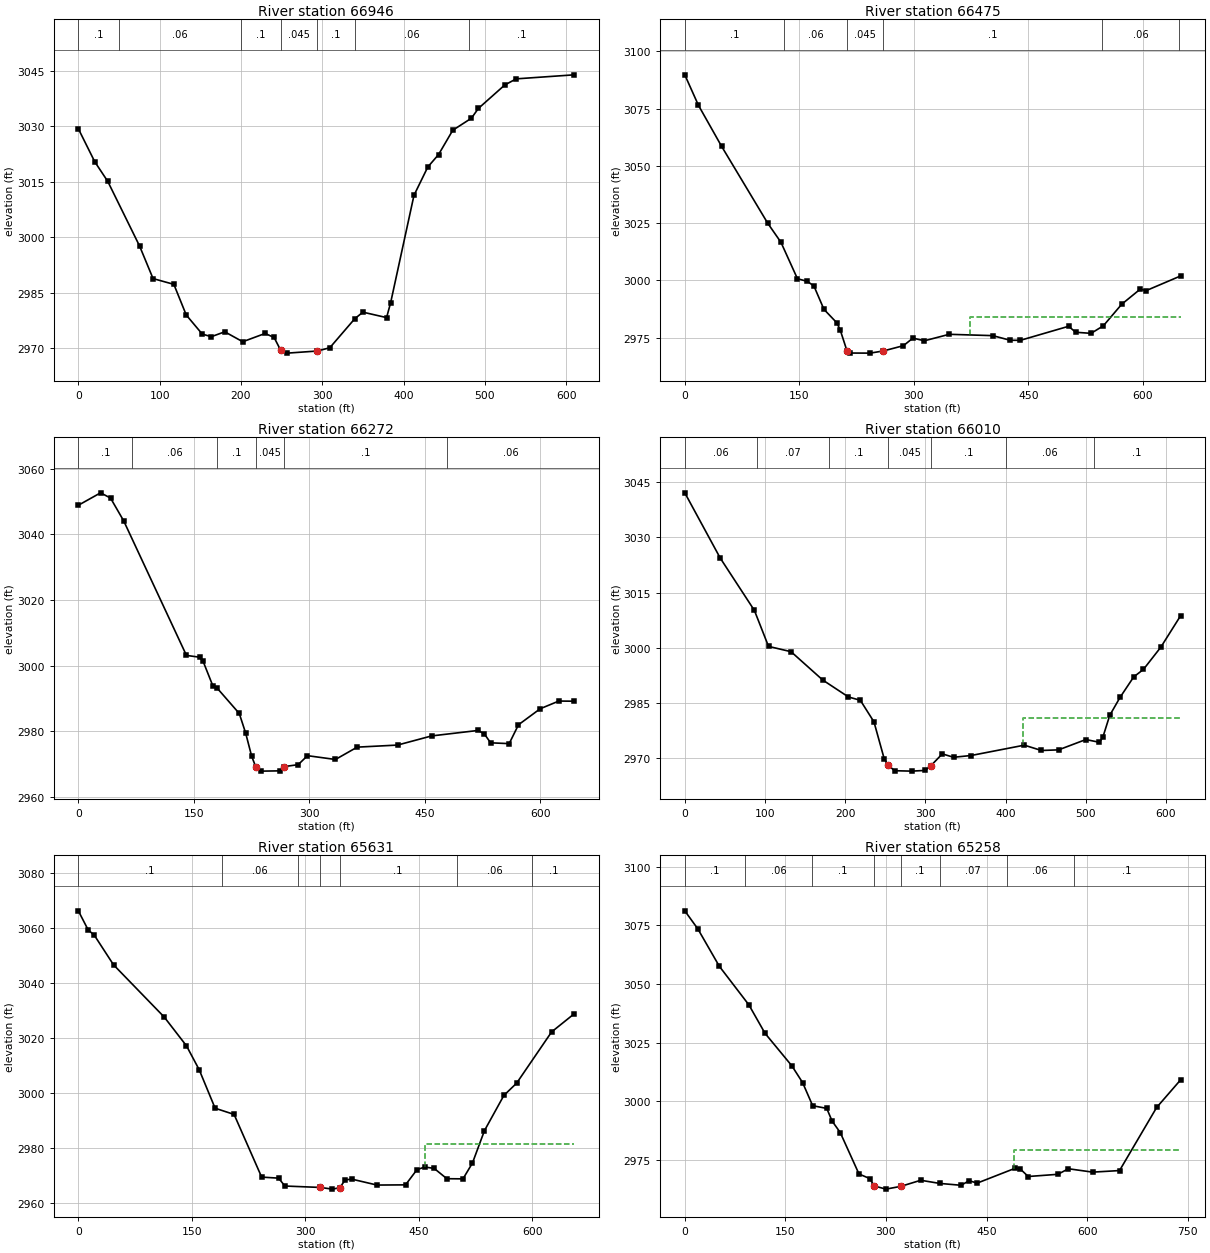
Type RM Length L Ch R = 1 ,66946   ,488.7,471.5,455.6
XS GIS Cut Line= 2
2312522.85350575607164.2864395812312080.43449425607583.970981778
#Sta/Elev= 30
       0 3029.38    20.2 3020.45    36.2 3015.14    75.4 2997.62    91.9 2988.85
   117.5 2987.29   132.7 2979.01   152.4 2973.84   163.6 2973.14   180.1 2974.46
   202.2 2971.77   229.7 2974.01   240.8 2972.92   248.7 2969.52     257 2968.69
     294 2969.26   309.3 2970.15     340    2978     350 2979.77   379.1  2978.3
   384.1 2982.33   412.8 3011.37   429.8 3019.03     443 3022.39   460.5 3028.97
   483.4 3032.22     492 3034.87   524.4  3041.2   538.5 3042.87   609.8 3043.96
#Mann= 7 ,-1,0
       0      .1       0      50     .06       0     200      .1       0
   248.7    .045       0     294      .1       0     340     .06       0
     480      .1       0
Bank Sta=248.7,294
XS Rating Curve= 0 ,0
Exp/Cntr=0.3,0.1

Type RM Length L Ch R = 1 ,66475   ,221.5,202.5,184.6
XS GIS Cut Line= 3
2312124.94622294606784.6403198822311990.04483803607114.793709275
2311959.86952824607405.896697771
#Sta/Elev= 30
       0 3089.71    17.9 3076.39    48.1 3058.56   108.6 3024.97   125.9 3016.66
   147.5 3000.77   160.5  2999.6   169.1 2997.58   182.2 2987.41   199.3 2981.45
   203.7 2978.22   212.3 2969.37   216.6 2968.34   242.6  2968.3   259.8 2969.23
   286.3 2971.55   298.7 2974.85   313.8 2973.69   346.3 2976.51   403.3 2975.93
   426.1 2973.91   439.5 2973.89   502.6 2980.01   511.9  2977.4     532 2976.93
   548.1 2980.22   572.2 2989.64   596.3 2996.18   604.4  2995.6   649.3 3001.97
#Mann= 6 ,-1,0
       0      .1       0     130     .06       0   212.3    .045       0
   259.8      .1       0  546.65     .06       0  646.65      .1       0
#XS Ineff= 2 , 0
                          373.07          2984.1
Permanent Ineff=
       F       F
Bank Sta=212.3,259.8
XS Rating Curve= 0 ,0
Exp/Cntr(USF)=0,0
Exp/Cntr=0.3,0.1

Type RM Length L Ch R = 1 ,66272   ,268.8,262.3,255.4
XS GIS Cut Line= 3
  2311905.857331606742.1739323032311830.86399982606936.799482276
2311883.53710809607368.967739818
#Sta/Elev= 30
       0 3048.84    28.9 3052.63    41.8 3051.04    58.9 3044.09   140.4 3003.08
   157.5 3002.53   161.8 3001.41   174.7 2993.79     180 2993.18     209 2985.38
   217.3  2979.4   225.1 2972.34   230.4 2969.11   237.2 2967.81   261.3 2967.89
   267.6  2969.2   285.5 2969.78   297.6 2972.52   333.9 2971.36   362.1 2975.12
   414.5 2975.75   458.8 2978.54   519.2 2980.21   527.3 2979.14   535.4 2976.44
   559.5 2976.19   571.6 2981.94   599.8 2986.82     624 2989.17   643.9 2989.12
#Mann= 6 ,-1,0
       0      .1       0      70     .06       0     180      .1       0
   230.4    .045       0   267.6      .1       0  478.57     .06       0
Bank Sta=230.4,267.6
XS Rating Curve= 0 ,0
Exp/Cntr(USF)=0,0
Exp/Cntr=0.3,0.1

Type RM Length L Ch R = 1 ,66010   ,378.3,379,378.5
XS GIS Cut Line= 2
2311503.68984505606823.6907207772311716.69203176607404.121679549
#Sta/Elev= 30
       0 3042.15    44.2 3024.38    86.8 3010.12   104.4 3000.34   132.5 2998.89
     172 2991.18   204.1 2986.56   218.9 2985.66   235.9 2979.78   248.7  2969.7
     254 2967.95   261.5 2966.48   282.8 2966.37   299.8 2966.56     307 2967.87
   321.1 2971.07   335.1 2970.14   356.9 2970.62   423.4 2973.44   444.7 2971.99
   466.1 2972.16   500.1 2974.97   517.1 2974.22   521.4 2975.66   529.9 2981.55
   542.7 2986.43   559.8 2992.03   571.9 2994.06   593.6 3000.12   618.3 3008.69
#Mann= 7 ,-1,0
       0     .06       0      90     .07       0     180      .1       0
     254    .045       0     307      .1       0     400     .06       0
     510      .1       0
#XS Ineff= 2 , 0
                          421.58         2980.85
Permanent Ineff=
       F       F
Bank Sta=254,307
XS Rating Curve= 0 ,0
Exp/Cntr(USF)=0,0
Exp/Cntr=0.3,0.1

Type RM Length L Ch R = 1 ,65631   ,365.3,373.2,376.7
XS GIS Cut Line= 2
2311159.33630988606924.8667594622311356.36333258607549.673173797
#Sta/Elev= 30
       0 3066.13    12.9 3059.24    21.3 3057.18    46.5 3046.51   113.6 3027.48
   142.9 3017.05   159.7 3008.36   180.7 2994.38   205.8 2992.12   242.2 2969.34
   264.6 2968.96   272.9  2966.1   319.8 2965.58   335.7 2964.97   345.3 2965.47
   352.6 2968.31     361 2968.62   394.6 2966.45   432.3 2966.52   447.3    2972
   457.5 2973.01   470.1 2972.51   486.9 2968.76   508.2  2968.7   520.7 2974.45
   536.6 2986.24   562.3 2999.05   579.1 3003.49   625.3 3022.11   655.1 3028.69
#Mann= 7 ,-1,0
       0      .1       0     190     .06       0     290      .1       0
   319.8    .045       0   345.3      .1       0     500     .06       0
     600      .1       0
#XS Ineff= 2 , 0
                          458.65         2981.26
Permanent Ineff=
       F       F
Bank Sta=319.8,345.3
XS Rating Curve= 0 ,0
Exp/Cntr(USF)=0,0
Exp/Cntr=0.3,0.1

Type RM Length L Ch R = 1 ,65258   ,494.9,508.7,508
XS GIS Cut Line= 2
2310880.65844894606917.7666865722310921.48386806 607656.17426715
#Sta/Elev= 30
       0 3081.19    19.4 3073.51    51.5 3057.56    95.6 3041.11   119.6 3029.02
   159.7 3015.13   175.7    3008   190.7 2998.15   211.7    2997   219.7  2991.6
   231.8 2986.73   259.8 2969.05   275.8 2967.11   282.4 2963.97   299.9  2962.6
   322.2 2963.78   351.9 2966.38     380 2965.04     412 2964.24   424.1 2966.18
   436.1 2965.17   492.2 2971.44   500.2 2971.22   512.2 2967.98   556.3 2968.91
   572.2 2971.28   608.3 2969.84   648.4 2970.51   703.8 2997.42   739.5 3009.17
#Mann= 8 ,-1,0
       0      .1       0      90     .06       0     190      .1       0
   282.4    .045       0   322.2      .1       0     380     .07       0
     480     .06       0     580      .1       0
#XS Ineff= 2 , 0
                          491.27         2979.17
Permanent Ineff=
       F       F
Bank Sta=282.4,322.2
XS Rating Curve= 0 ,0
Exp/Cntr(USF)=0,0
Exp/Cntr=0.3,0.1

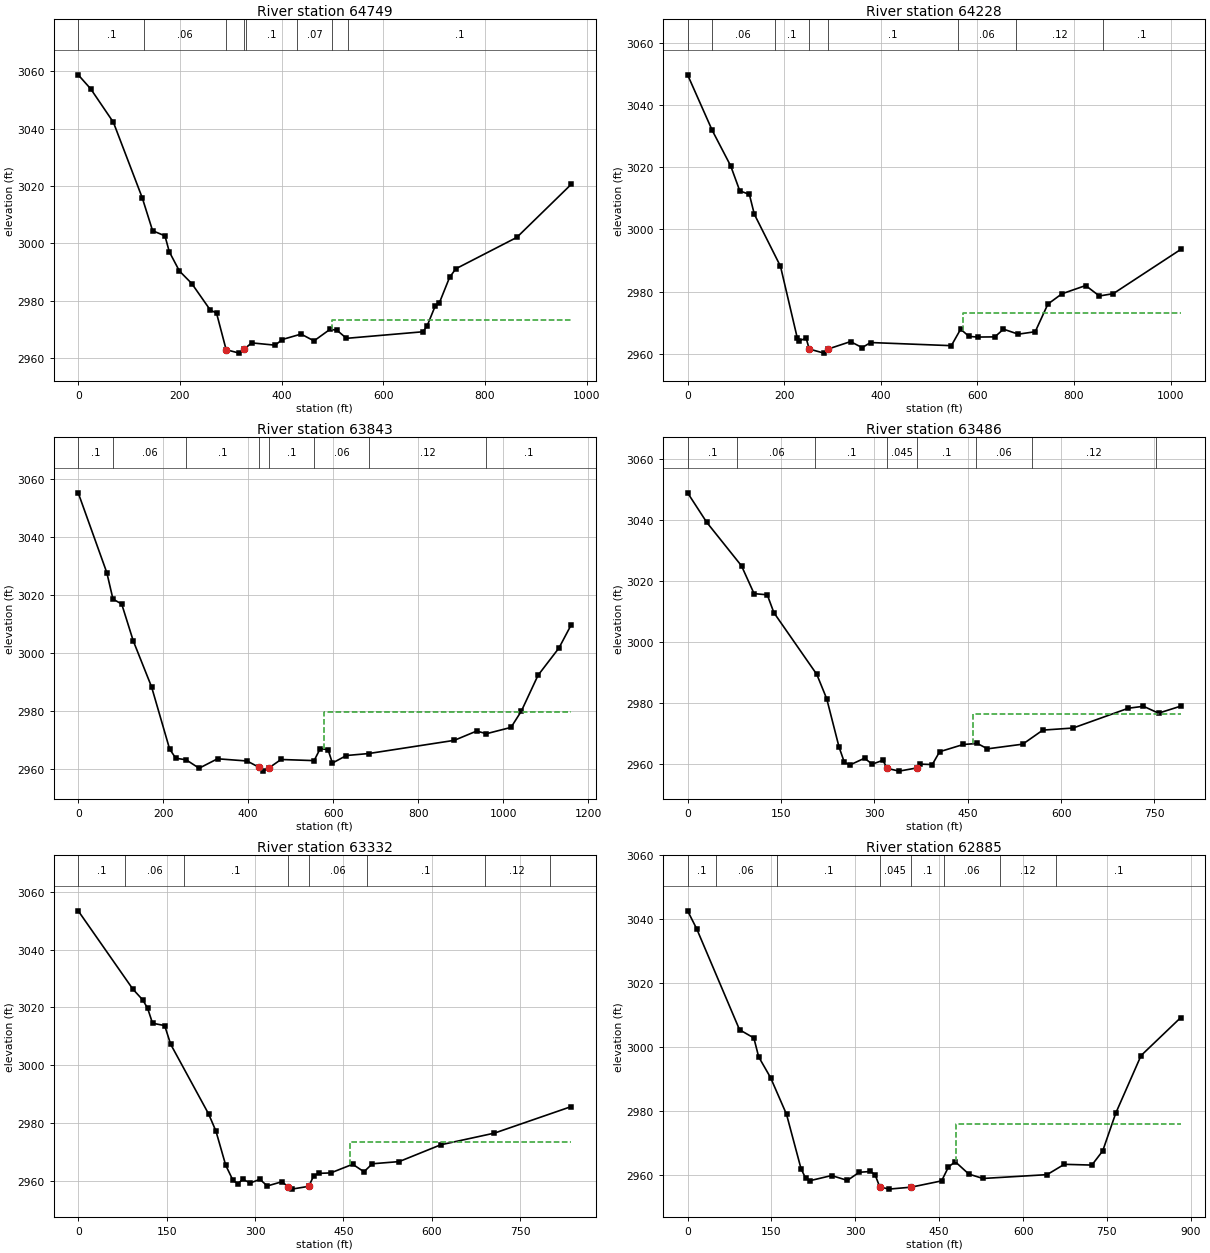
Type RM Length L Ch R = 1 ,64749   ,494.1,520.9,541.9
XS GIS Cut Line= 3
2310662.33120757606876.9412674542310534.52989554607634.874048479
2310589.55546044607828.351034736
#Sta/Elev= 30
       0 3058.81    24.6 3053.91    69.2 3042.25     126 3015.89   146.3 3004.43
   170.6 3002.64   179.1  2997.1     199 2990.38   223.3 2986.01   259.9 2976.72
     272 2975.72  290.91 2962.93   316.6 2961.73  325.79 2963.01     341 2965.31
   387.4  2964.5   401.3 2966.48   438.3 2968.37   463.7    2966   495.3 2970.04
   508.9  2969.7   527.6 2966.89   677.7 2969.18   685.8 2971.07     702 2978.15
   710.2 2979.25   730.4 2988.18   742.6 2991.15   862.6 3002.11   969.8 3020.66
#Mann= 8 ,-1,0
       0      .1       0     130     .06       0  290.91    .045       0
  325.79     .06       0     330      .1       0     430     .07       0
     500     .08       0     530      .1       0
#XS Ineff= 2 , 0
                          499.72         2973.44
Permanent Ineff=
       F       F
Bank Sta=290.91,325.79
XS Rating Curve= 0 ,0
Exp/Cntr(USF)=0,0
Exp/Cntr=0.3,0.1

Type RM Length L Ch R = 1 ,64228   ,383.1,385.3,380.9
XS GIS Cut Line= 3
2310520.32974976606729.614754983 2309916.8235541607208.869675069
2309865.34802564 607453.82218978
#Sta/Elev= 30
       0 3049.73      51 3031.85    89.3 3020.39     108  3012.4   127.9 3011.25
   138.1 3004.89   192.3 2988.11   226.9 2965.16   230.4 2964.07   245.4 2964.99
   251.8 2961.49   282.3 2960.17   291.3 2961.51   337.3 2963.88   361.4 2961.94
   378.8 2963.58     546 2962.57   565.3 2967.88   582.5 2965.55   600.5 2965.34
   636.1  2965.4     654 2967.88   684.6 2966.27   719.7 2967.06   745.9 2975.95
   774.8 2979.25   824.1 2981.92   852.5 2978.56   881.3 2979.31    1021 2993.54
#Mann= 8 ,-1,0
       0      .1       0      50     .06       0     180      .1       0
   251.8    .045       0   291.3      .1       0     560     .06       0
     680     .12       0  860.65      .1       0
#XS Ineff= 2 , 0
                          569.92         2973.19
Permanent Ineff=
       F       F
Bank Sta=251.8,291.3
XS Rating Curve= 0 ,0
Exp/Cntr(USF)=0,0
Exp/Cntr=0.3,0.1

Type RM Length L Ch R = 1 ,63843   ,362.8,357.1,343.8
XS GIS Cut Line= 2
2310344.60294573 606475.78714916  2309373.667978607111.243672829
#Sta/Elev= 30
       0 3055.11    67.4 3027.59    81.8 3018.52   102.4  3016.8   129.6  3004.1
   172.6  2988.3   215.1 2966.87   229.6  2963.7   253.9 2963.17   284.5 2960.26
   327.8 2963.51   397.3 2962.75   425.6 2960.57   434.7 2959.26   449.9 2960.48
   477.3 2963.27   555.1 2962.88   569.4    2967   587.9 2966.67   598.1 2962.04
   631.2 2964.64   683.2 2965.31   884.9 2969.86   937.5 2973.06   960.6 2972.15
  1018.4 2974.32  1042.7 2979.92    1082 2992.27  1131.1 3001.64  1160.4 3009.75
#Mann= 8 ,-1,0
       0      .1       0    81.8     .06       0   253.9      .1       0
   425.6    .045       0   449.9      .1       0   555.1     .06       0
   683.2     .12       0   960.6      .1       0
#XS Ineff= 2 , 0
                          578.03         2979.65
Permanent Ineff=
       F       F
Bank Sta=425.6,449.9
XS Rating Curve= 0 ,0
Exp/Cntr(USF)=0,0
Exp/Cntr=0.3,0.1

Type RM Length L Ch R = 1 ,63486   ,138.6,153.6,170.4
XS GIS Cut Line= 4
2310153.94109334606203.2019902092310064.72990274606237.198270403
2309802.47294689 606465.412829132309456.86367548606515.100021407
#Sta/Elev= 30
       0 3048.99    30.8  3039.3    86.6 3025.05   106.8 3015.93     128 3015.55
   138.6  3009.7   207.6 2989.44   223.5 2981.46   243.3 2965.63   251.8 2960.64
   260.6 2959.73   284.3 2961.97   296.5 2960.01   313.6 2961.27   320.9 2958.63
   339.7 2957.73     368 2958.76   373.7 2960.03   393.1 2959.88   404.9 2964.09
   443.1 2966.48   465.6 2966.79   481.8 2965.04   538.4 2966.57   570.7 2971.18
   619.2 2971.86   708.1 2978.36   732.4 2978.99   756.6 2976.74   792.3 2979.04
#Mann= 8 ,-1,0
       0      .1       0      80     .06       0  205.47      .1       0
   320.9    .045       0     368      .1       0  463.12     .06       0
  553.12     .12       0  753.12      .1       0
#XS Ineff= 2 , 0
                          459.27         2976.33
Permanent Ineff=
       F       F
Bank Sta=320.9,368
XS Rating Curve= 0 ,0
Exp/Cntr(USF)=0,0
Exp/Cntr=0.3,0.1

Type RM Length L Ch R = 1 ,63332   ,448.4,447.6,447.1
XS GIS Cut Line= 2
2310161.77606881606172.2590331052309354.14277755606390.586274477
#Sta/Elev= 30
       0 3053.44    92.8 3026.32   109.4 3022.62   117.7 3019.73   126.1 3014.53
   146.7 3013.71   156.8 3007.27   221.3 2983.09   233.7 2977.15   250.3 2965.32
   262.7 2960.08     271 2958.98   279.3 2960.53   291.7  2959.2   308.3 2960.49
   320.7 2958.18   345.6 2959.65   356.1 2957.91   362.2 2957.09   391.2 2958.06
   399.4 2961.66   407.7 2962.55   428.4  2962.7   465.7  2965.7   484.8 2963.09
   498.9 2965.87   544.5 2966.62   614.9 2972.43   706.1 2976.48   836.6 2985.68
#Mann= 8 ,-1,0
       0      .1       0      80     .06       0     180      .1       0
   356.1    .045       0   391.2     .06       0     490      .1       0
     690     .12       0     800      .1       0
#XS Ineff= 2 , 0
                          461.41         2973.47
Permanent Ineff=
       F       F
Bank Sta=356.1,391.2
XS Rating Curve= 0 ,0
Exp/Cntr(USF)=0,0
Exp/Cntr=0.3,0.1

Type RM Length L Ch R = 1 ,62885   ,540.8,566.4,577.8
XS GIS Cut Line= 5
2310131.45966564 605880.739056542309951.07655552605814.958639004
2309824.71159969605816.4641205372309668.46847521605851.839922306
2309265.18426195605840.735454205
#Sta/Elev= 30
       0 3042.62    16.3 3036.98    92.9 3005.42   118.5 3002.85   127.1 2996.94
   148.3 2990.47   176.9 2978.98   202.9 2961.94   210.9 2959.06   218.9 2958.21
   257.5 2959.82   285.8  2958.3   306.9 2960.84   327.1 2961.09   335.3 2960.07
   343.5 2956.33   359.6 2955.57   399.7 2956.18   454.3 2958.15   466.5 2962.48
   478.6 2964.16   502.9 2960.28   528.2  2958.9   642.9  2960.1   673.7 2963.33
     723 2963.09   742.4 2967.52   765.7 2979.31     811 2997.35     882 3009.23
#Mann= 8 ,-1,0
       0      .1       0      50     .06       0     160      .1       0
   343.5    .045       0   399.7      .1       0  458.38     .06       0
  558.57     .12       0  658.57      .1       0
#XS Ineff= 2 , 0
                          479.44         2975.88
Permanent Ineff=
       F       F
Bank Sta=343.5,399.7
XS Rating Curve= 0 ,0
Exp/Cntr(USF)=0,0
Exp/Cntr=0.3,0.1

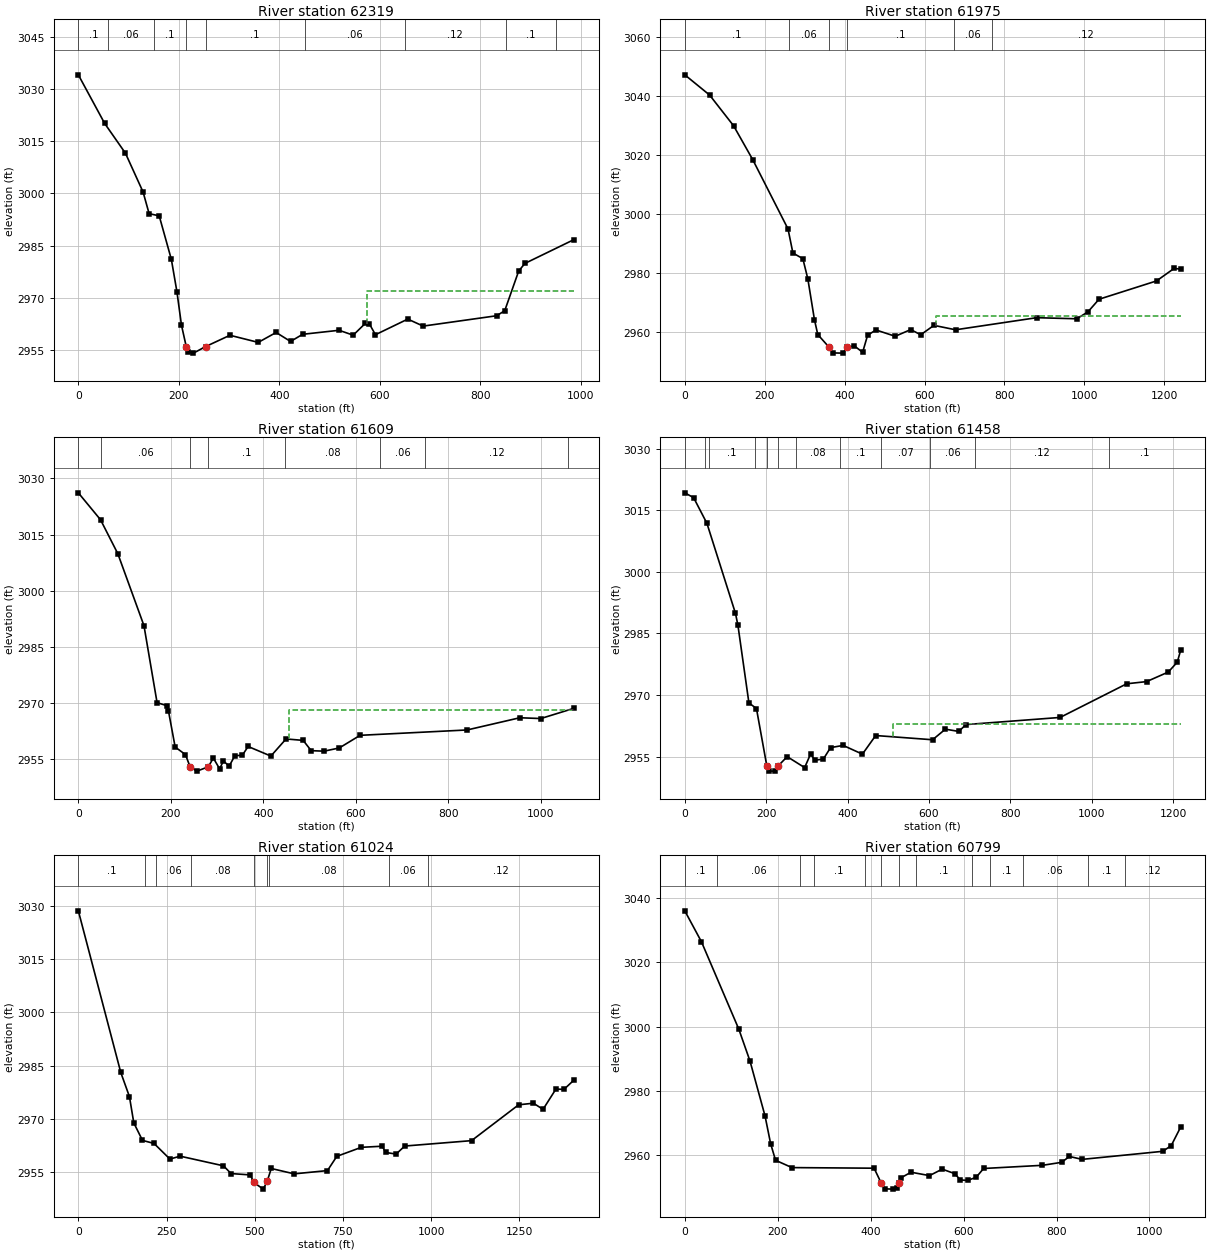
Type RM Length L Ch R = 1 ,62319   ,336.5,343.1,349.7
XS GIS Cut Line= 2
2310236.32683415605483.5519627592309254.74175709605385.925960519
#Sta/Elev= 30
       0 3034.02    52.4 3020.08    93.7 3011.55   128.8 3000.42   140.8 2994.22
   160.9 2993.58   185.1 2981.07   196.1 2971.86   205.2 2962.23  214.84 2955.99
     218 2954.59     229 2954.22   253.4 2956.11   301.6 2959.34   357.9  2957.3
   393.5 2960.14   422.2 2957.57   446.3 2959.62   518.7 2960.77   546.8 2959.37
     571 2962.76     579  2962.6   591.1  2959.5   655.4 2963.98     686 2961.97
   832.3 2964.94   848.3 2966.39   876.1 2977.78   888.5 2979.95   986.4  2986.8
#Mann= 9 ,-1,0
       0      .1       0      60     .06       0     150      .1       0
  214.84    .045       0   253.4      .1       0     450     .06       0
     650     .12       0     850      .1       0     950     .12       0
#XS Ineff= 2 , 0
                          574.65         2971.91
Permanent Ineff=
       F       F
Bank Sta=214.84,253.4
XS Rating Curve= 0 ,0
Exp/Cntr(USF)=0,0
Exp/Cntr=0.3,0.1

Type RM Length L Ch R = 1 ,61975   ,364.8,366.4,361.3
XS GIS Cut Line= 4
2310442.29406104605167.6036380482310177.93809044605155.891664667
2309702.86138251605022.7761135132309219.89574001605011.557801534
#Sta/Elev= 30
       0 3047.03    62.2 3040.16   122.2 3029.75   170.3 3018.22   258.4 2994.78
   270.6 2986.64   295.5 2984.72     308 2977.85   324.6 2963.98   332.9    2959
   361.4 2954.67   370.3 2952.78   395.2 2952.71  406.57 2954.63   424.3 2955.17
   445.1 2952.99   457.5 2958.74   478.3 2960.57   526.7 2958.42   565.5 2960.69
   590.5 2958.93   623.7 2962.12   677.7 2960.62   880.7 2964.72   981.2 2964.35
    1009 2966.68  1036.8 2970.97  1180.8 2977.18  1224.8 2981.42  1241.1 2981.18
#Mann= 6 ,-1,0
       0      .1       0     260     .06       0   361.4    .045       0
  406.57      .1       0  674.62     .06       0  767.99     .12       0
#XS Ineff= 2 , 0
                          627.97         2965.32
Permanent Ineff=
       F       F
Bank Sta=361.4,406.57
XS Rating Curve= 0 ,0
Exp/Cntr(USF)=0,0
Exp/Cntr=0.3,0.1

Type RM Length L Ch R = 1 ,61609   ,143,151,159.1
XS GIS Cut Line= 5
2310424.78125914604830.6920708162310249.16479771 604806.58785062
2309961.63588536604741.1621100872309760.19347372604694.675399708
 2309377.9694106604603.423708964
#Sta/Elev= 30
       0 3026.14      48 3018.95    85.4 3009.88   141.9 2990.67   170.2 2970.12
   190.6 2969.35   194.7 2967.99   209.3 2958.27   231.6 2956.25   241.82952.903
   256.4 2951.84   280.92952.989   291.8 2955.33   305.4 2952.46   313.7 2954.56
     326 2953.16   338.3 2955.94   354.7  2956.1     367 2958.42   416.2 2955.86
     449 2960.43     486 2960.05   503.4  2957.3   531.1 2957.17     564 2958.02
   609.1  2961.4   840.4 2962.83   954.4 2966.09   999.7 2965.88  1071.8 2968.63
#Mann= 8 ,-1,0
       0      .1       0      50     .06       0   241.8    .045       0
   280.9      .1       0  447.26     .08       0  652.14     .06       0
  748.88     .12       0 1058.88      .1       0
#XS Ineff= 2 , 0
                          454.99         2968.09
Permanent Ineff=
       F       F
Bank Sta=241.8,280.9
XS Rating Curve= 0 ,0
Exp/Cntr(USF)=0,0
Exp/Cntr=0.3,0.1

Type RM Length L Ch R = 1 ,61458   ,431,434.1,438
XS GIS Cut Line= 3
2310417.37869285604770.4452263342310320.67726408604695.672347682
2309332.84255888604221.514006531
#Sta/Elev= 30
       0  3019.3    21.7 3018.12    54.4 3011.85   124.5  2989.9   130.5    2987
   157.5 2968.07     176 2966.71   201.5 2952.69   207.1 2951.45   220.4 2951.44
   229.4 2952.72   251.5 2954.97   294.4  2952.3   309.1 2955.64   319.3 2954.13
   340.2 2954.35     358 2957.17     389 2957.71   436.3 2955.58   468.9 2960.12
   608.7 2959.09   640.1 2961.67     673 2961.12   690.7 2962.79   921.9 2964.53
  1085.6 2972.74  1134.4 2973.27  1187.7  2975.6  1209.8 2978.01    1218 2980.89
#Mann= 12 ,-1,0
       0      .1       0      50     .06       0      60      .1       0
  172.24     .06       0   201.5    .045       0   229.4     .06       0
  272.24     .08       0  382.24      .1       0  482.24     .07       0
  602.24     .06       0  712.24     .12       0 1042.24      .1       0
#XS Ineff= 2 , 0
                          510.27         2962.89
Permanent Ineff=
       F       F
Bank Sta=201.5,229.4
XS Rating Curve= 0 ,0
Exp/Cntr(USF)=0,0
Exp/Cntr=0.3,0.1

Type RM Length L Ch R = 1 ,61024   ,225.6,224.9,225.8
XS GIS Cut Line= 3
2310793.68255603604383.0406647832310422.70374752604301.389826546
2309522.76950869603809.709778902
#Sta/Elev= 30
       0  3028.6   120.3 2983.09   144.9 2976.28   157.2  2968.9   181.8 2963.97
   214.5 2963.11   259.6 2958.71   288.4 2959.53   411.4 2956.81   432.9 2954.63
   487.6 2954.25   497.1 2952.15     524 2950.25   535.2 2952.43   546.8 2956.06
   611.8 2954.55   706.1 2955.47   732.6 2959.48   802.1 2962.02   861.3 2962.33
   871.2 2960.57   900.7 2960.12   925.1 2962.38  1114.5  2963.9  1247.9 2973.99
  1289.8 2974.44  1317.1 2972.71  1353.6 2978.42  1376.4 2978.33  1405.3 2981.01
#Mann= 9 ,-1,0
       0      .1       0     190     .07       0     220     .06       0
     320     .08       0   497.1    .045       0   535.2      .1       0
  539.86     .08       0  879.86     .06       0  989.86     .12       0
Bank Sta=497.1,535.2
XS Rating Curve= 0 ,0
Exp/Cntr(USF)=0,0
Exp/Cntr=0.3,0.1

Type RM Length L Ch R = 1 ,60799   ,203.8,182.6,168.6
XS GIS Cut Line= 3
2310839.71819252604154.052175301  2310653.771351604174.712935469
2309882.43630472603751.167352017
#Sta/Elev= 30
       0 3036.06    35.8 3026.43   116.3 2999.17   140.4 2989.22   172.7 2972.14
   184.7 2963.52   195.3 2958.34   230.6 2956.06   407.4 2955.87     423 2951.15
   430.8 2949.44   447.9 2949.35   456.2 2949.77   460.5 2951.39   464.5 2952.82
   486.9 2954.62   526.6 2953.56     554 2955.58   581.2 2954.16     593  2952.2
   608.7 2952.07     627 2953.03   643.1 2955.78   769.7 2956.77     811  2957.7
   827.8 2959.53   855.1 2958.62  1028.6 2961.13  1046.8 2962.89  1067.1 2968.66
#Mann= 13 ,-1,0
       0      .1       0      70     .06       0  247.09     .08       0
  277.09      .1       0  387.09     .08       0     423    .045       0
   460.5     .08       0  497.09      .1       0  617.09     .08       0
  657.09      .1       0  727.09     .06       0  867.09      .1       0
  947.09     .12       0
Bank Sta=423,460.5
XS Rating Curve= 0 ,0
Exp/Cntr(USF)=0,0
Exp/Cntr=0.3,0.1

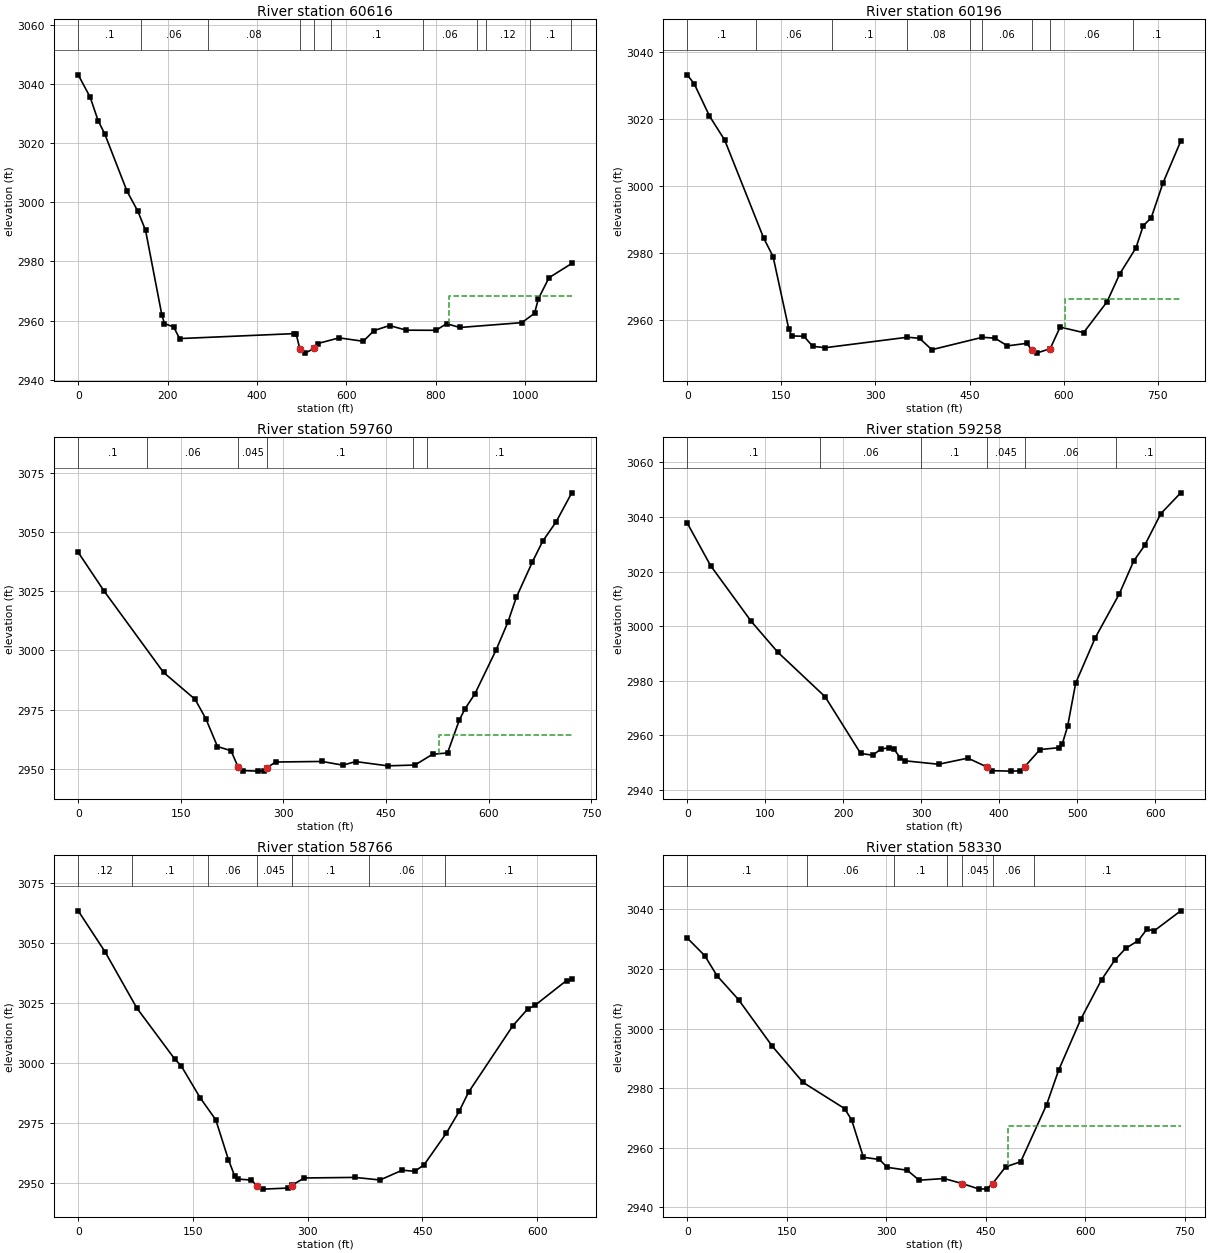
Type RM Length L Ch R = 1 ,60616   ,391.9,420.5,451.6
XS GIS Cut Line= 4
 2310896.2736972604075.0258569752310468.86194553603867.394591097
2310252.39687692603872.2515448442309905.53630496603648.662735793
#Sta/Elev= 30
       0 3043.11    26.8 3035.52    44.6 3027.57    59.2 3023.19   109.2 3003.75
   133.5 2996.96   150.7 2990.52     187 2962.01     193 2958.99   213.6 2957.84
   226.9 2953.91   483.9 2955.59   487.9 2955.35   495.9 2950.45   507.9 2948.99
   527.9  2950.6   535.9 2952.23   583.9 2954.15   637.8    2953   662.3 2956.64
   696.7 2958.31   734.3 2956.75   800.7 2956.71   824.3 2958.96   853.8 2957.66
   992.7  2959.3  1021.1 2962.45  1029.8 2967.41  1053.6  2974.5  1104.4 2979.31
#Mann= 11 ,-1,0
       0      .1       0     140     .06       0     290     .08       0
   495.9    .045       0   527.9     .08       0  565.18      .1       0
  771.69     .06       0  891.69      .1       0  911.69     .12       0
 1011.69      .1       0 1101.69     .12       0
#XS Ineff= 2 , 0
                           830.2         2968.19
Permanent Ineff=
       F       F
Bank Sta=495.9,527.9
XS Rating Curve= 0 ,0
Exp/Cntr(USF)=0,0
Exp/Cntr=0.3,0.1

Type RM Length L Ch R = 1 ,60196   ,447.3,435.7,428.5
XS GIS Cut Line= 3
2310965.41930127603806.0870713342310527.76708394603505.430244254
2310383.95919828603294.364985656
#Sta/Elev= 30
       0 3033.13    11.2 3030.44    35.5 3020.83    59.7 3013.67   121.7 2984.48
   136.8 2978.91   161.7 2957.43   166.5 2955.24   185.9 2955.12     200 2952.13
   219.9 2951.72   350.9 2954.84   370.3 2954.53   389.7 2951.12   470.5 2954.83
   490.6 2954.55   510.2 2952.26     541 2953.02   548.7 2951.14   556.8  2950.1
   578.42951.441   594.2 2957.88   631.6 2956.21     669 2965.42   689.2 2973.74
     715 2981.49   726.6 2988.08   739.4  2990.5   758.3 3000.96   786.4 3013.34
#Mann= 9 ,-1,0
       0      .1       0     110     .06       0     230      .1       0
     350     .08       0     450     .07       0     470     .06       0
   548.7    .045       0   578.4     .06       0  710.97      .1       0
#XS Ineff= 2 , 0
                          602.59         2966.38
Permanent Ineff=
       F       F
Bank Sta=548.7,578.4
XS Rating Curve= 0 ,0
Exp/Cntr(USF)=0,0
Exp/Cntr=0.3,0.1

Type RM Length L Ch R = 1 ,59760   ,506.1,502.4,499.6
XS GIS Cut Line= 2
 2311104.5442913603628.5061413912310612.96596579603100.193958018
#Sta/Elev= 30
       0 3041.41    37.3 3025.29   124.7 2990.73   170.8 2979.39   186.6 2971.18
   203.6 2959.43   223.4 2957.68     234 2950.62   240.4 2949.27     263 2949.05
   271.5 2949.16   276.5 2950.55   288.5  2952.9   356.4 2953.13     387 2951.57
   405.7 2953.08   452.6 2951.28   492.3 2951.62   518.1 2956.17     540 2956.73
   557.3 2970.67   565.8 2975.47     580 2981.66   611.1 3000.27   628.1 3011.82
   640.6 3022.43   664.1 3037.37     679 3046.05   698.9 3054.34   721.6 3066.53
#Mann= 6 ,-1,0
       0      .1       0     100     .06       0     234    .045       0
   276.5      .1       0     490     .06       0     510      .1       0
#XS Ineff= 2 , 0
                          526.87         2964.45
Permanent Ineff=
       F       F
Bank Sta=234,276.5
XS Rating Curve= 0 ,0
Exp/Cntr=0.3,0.1

Type RM Length L Ch R = 1 ,59258   ,525.9,491.7,454.1
XS GIS Cut Line= 2
2311395.19552621603251.3197266622310908.60055116602846.660619566
#Sta/Elev= 30
       0  3037.8    29.9 3022.21      82 3001.78     116 2990.49   176.9  2974.1
   222.4 2953.34     238 2952.67   248.4 2954.96   258.8  2955.4     265    2955
   273.5 2951.57   279.7 2950.62   322.4 2949.37   359.9 2951.61     385  2948.3
   391.2 2947.01   414.9 2946.85   426.9 2946.95   432.6  2948.4   452.4 2954.76
   477.4 2955.46   480.8 2956.65   487.8 2963.24   498.2 2979.15   523.4  2995.8
   553.9 3011.69   572.6 3023.87   586.6 3029.57   607.4 3041.24   632.9 3048.86
#Mann= 6 ,-1,0
       0      .1       0     170     .06       0     300      .1       0
     385    .045       0   432.6     .06       0     550      .1       0
Bank Sta=385,432.6
XS Rating Curve= 0 ,0
Exp/Cntr=0.3,0.1

Type RM Length L Ch R = 1 ,58766   ,451.9,436.3,416.2
XS GIS Cut Line= 2
2311530.31511839602503.2963671112310905.50870405602664.823025362
#Sta/Elev= 30
       0 3063.38    35.3 3046.17    76.6 3022.84   126.2 3001.53   134.6 2998.73
   159.2 2985.49   179.9 2976.16   196.4 2959.55   204.7 2952.63   208.8 2951.46
   226.5 2951.04   233.6 2948.65   241.8 2947.26   274.9 2947.71     279 2948.77
     279 2948.78   295.5 2951.91   361.7 2952.15   394.7 2951.08   423.6 2955.16
   440.2 2954.69   452.5 2957.52   481.5  2970.7     498 2979.65   510.4 2987.72
   568.2 3015.39   587.6 3022.38   597.1 3023.91   638.5  3034.3   645.3 3034.95
#Mann= 8 ,-1,0
       0     .12       0      70      .1       0     170     .06       0
   233.6    .045       0     279     .06       0     280      .1       0
     380     .06       0     480      .1       0
Bank Sta=233.6,279
XS Rating Curve= 0 ,0
Exp/Cntr(USF)=0,0
Exp/Cntr=0.3,0.1

Type RM Length L Ch R = 1 ,58330   ,423.2,423.9,424.5
XS GIS Cut Line= 3
2311304.88780413601926.4154447852311187.73660144602126.992503932
2310806.10768359 602467.79600266
#Sta/Elev= 30
       0 3030.39    26.4 3024.46    44.9 3017.73    77.3 3009.71   128.3 2994.05
   174.6 2981.93   237.1 2973.17   247.8 2969.38   265.6 2956.81   289.6 2956.09
   301.5 2953.44   331.6 2952.47   349.7 2949.12   387.2 2949.69   414.8 2947.97
   440.3 2946.13   451.8 2946.26   460.2 2947.96     480 2953.61   502.7 2955.32
   541.8 2974.49   559.8 2986.01   593.3 3003.17   624.5 3016.37   644.3  3022.9
   660.7 3026.87     680 3029.53   692.9 3033.33   703.8 3032.78   743.9  3039.5
#Mann= 7 ,-1,0
       0      .1       0     180     .06       0  312.28      .1       0
  392.28     .06       0   414.8    .045       0   460.2     .06       0
  522.28      .1       0
#XS Ineff= 2 , 0
                          483.72         2967.42
Permanent Ineff=
       F       F
Bank Sta=414.8,460.2
XS Rating Curve= 0 ,0
Exp/Cntr(USF)=0,0
Exp/Cntr=0.3,0.1