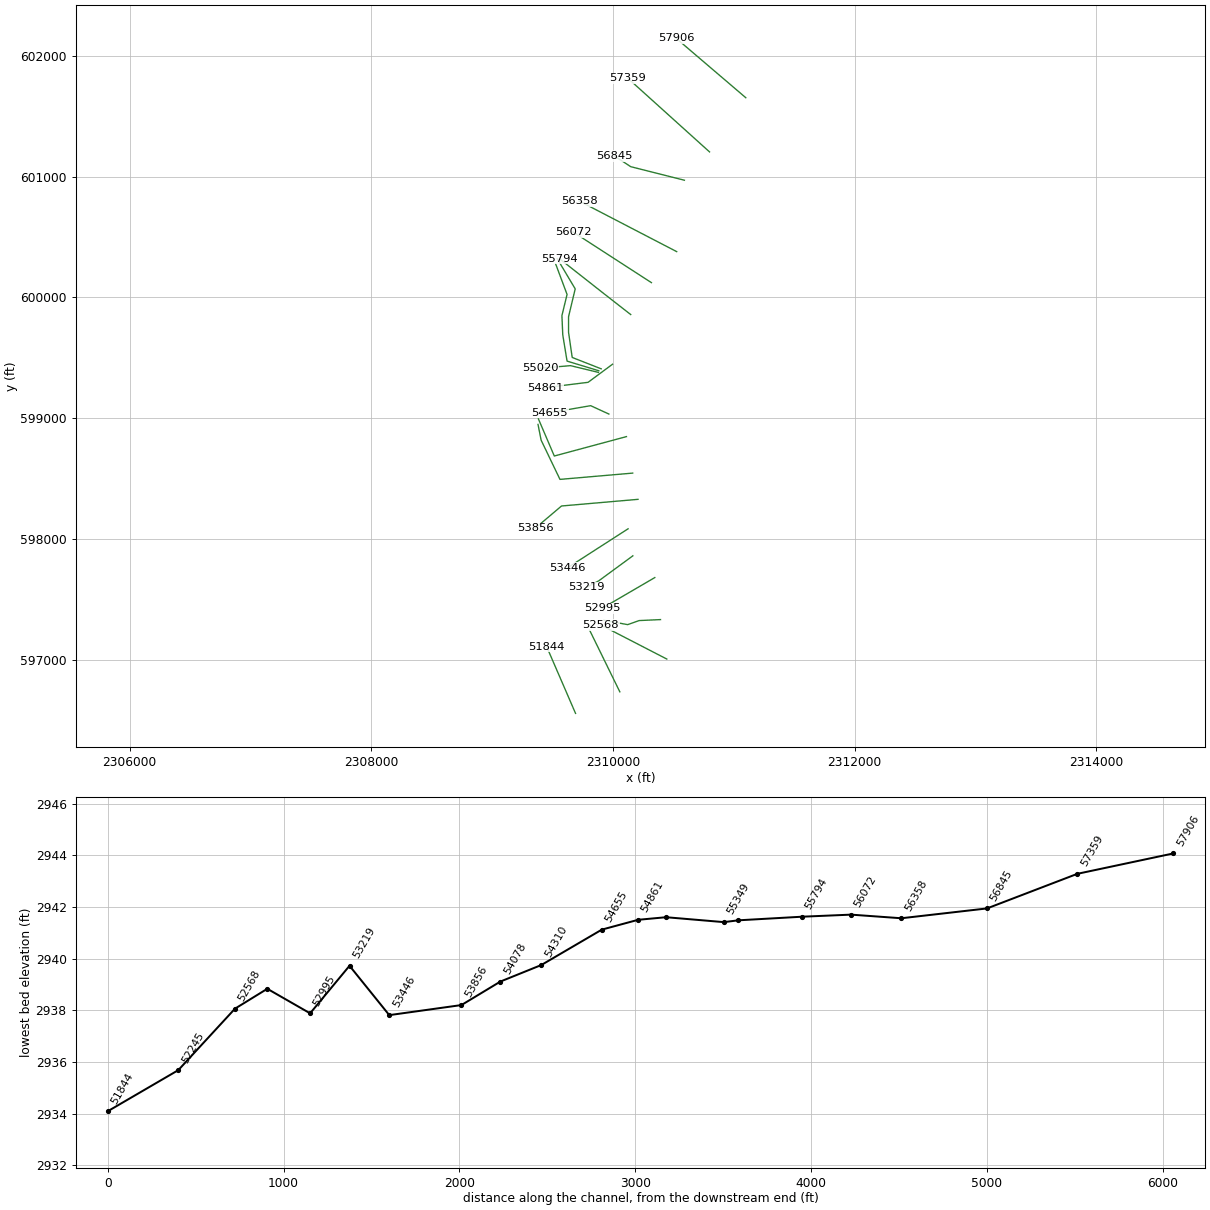
HEC-RAS study WFGRNBRRRV.prj: WFGRNBRRRV

--- WFGRNBRRRV.g01 (geometry) --- (continued)

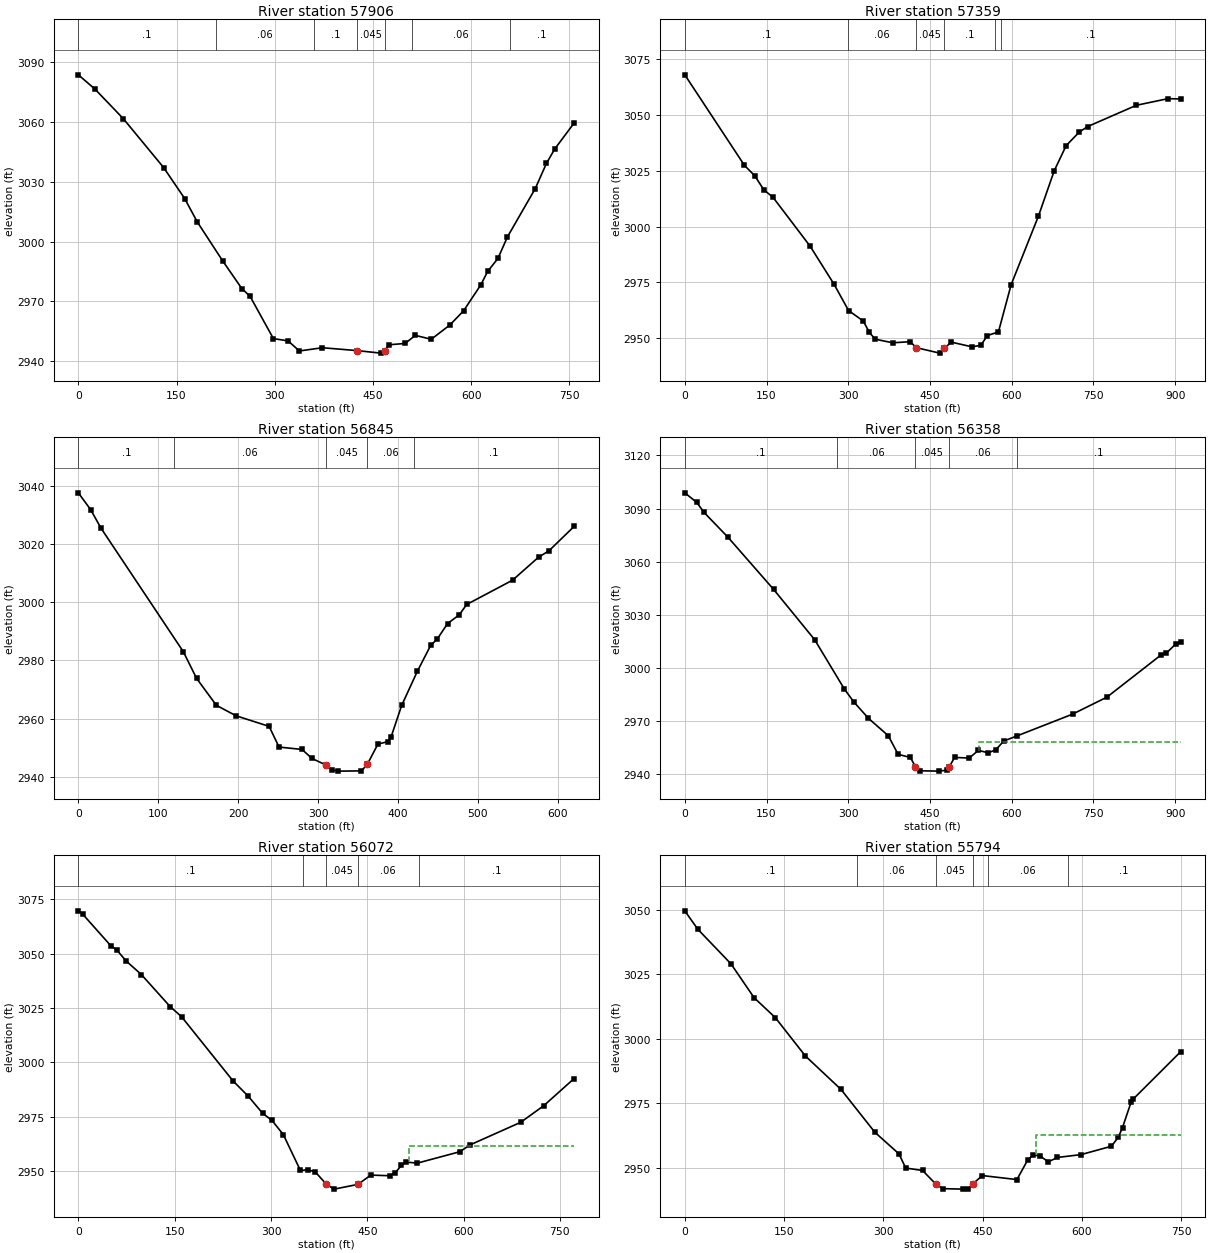
Type RM Length L Ch R = 1 ,57906   ,545.9,546.6,544.2
XS GIS Cut Line= 2
2311099.71719821 601652.528070652310523.70816848602144.428892905
#Sta/Elev= 30
       0 3083.74    25.6 3076.51    68.8  3061.7   130.4 3037.17   162.5 3021.64
   181.7 3009.92   220.3 2990.48   249.8 2976.46   262.4 2972.56     298 2951.36
   320.3 2950.23   337.8 2945.16   372.9 2946.78     426 2945.33   462.3 2944.07
   469.1 2945.38   473.9 2948.24   499.1 2948.92   514.9 2952.97   539.2 2951.03
   567.6 2958.19   588.5 2965.28   614.8 2978.28   625.3 2985.04   641.1 2991.63
   655.5 3002.36   698.1 3026.67   715.1 3039.25   727.8 3046.51   757.5 3059.59
#Mann= 7 ,-1,0
       0      .1       0     210     .06       0     360      .1       0
     426    .045       0   469.1      .1       0     510     .06       0
     660      .1       0
Bank Sta=426,469.1
XS Rating Curve= 0 ,0
Exp/Cntr=0.3,0.1

Type RM Length L Ch R = 1 ,57359   ,491.9,514,531.8
XS GIS Cut Line= 2
     2310799.455      601203.882     2310123.927      601813.606
#Sta/Elev= 30
       0 3068.04   109.4 3027.48   128.4 3022.78   145.2 3016.44   161.8 3013.16
   229.8 2991.29   273.8 2974.21   300.6 2962.36   327.7 2957.65   338.5 2952.64
   349.3 2949.54   381.6 2947.91   413.9 2948.41   424.7 2945.74   467.8 2943.28
   476.2 2945.49   489.4  2948.2   527.2 2946.09   543.3 2946.81   555.5 2951.18
   575.6 2952.77   598.9 2973.93     649 3004.67     678 3025.02   699.9  3036.3
   724.3 3042.46   739.6 3044.87   828.8 3054.39   886.9 3057.36     910 3057.22
#Mann= 6 ,-1,0
       0      .1       0     300     .06       0   424.7    .045       0
   476.2      .1       0     570     .06       0     580      .1       0
Bank Sta=424.7,476.2
XS Rating Curve= 0 ,0
Exp/Cntr=0.3,0.1

Type RM Length L Ch R = 1 ,56845   ,497.7,487.1,476.8
XS GIS Cut Line= 3
2310591.59372442600969.4048359972310147.57592303601081.506770855
2310011.76896803601170.490255116
#Sta/Elev= 30
       0 3037.52    15.4 3031.75    28.3 3025.41   131.4 2982.93   147.9 2973.81
   172.7 2964.54   197.4 2960.94   238.7 2957.31   251.1 2950.21   279.9 2949.38
   292.3 2946.28   309.5 2944.09   317.1 2942.38   325.1 2941.94   354.2 2942.02
   361.7 2944.36   374.8 2951.22   387.2 2952.06   391.3 2953.71   404.5 2964.51
   424.2 2976.26   440.8 2985.12   449.1 2987.34     462 2992.64   476.4 2995.58
   485.9 2999.18   543.3 3007.53   575.7  3015.4   588.7 3017.59   620.3    3026
#Mann= 5 ,-1,0
       0      .1       0     120     .06       0   309.5    .045       0
   361.7     .06       0     420      .1       0
Bank Sta=309.5,361.7
XS Rating Curve= 0 ,0
Exp/Cntr=0.3,0.1

Type RM Length L Ch R = 1 ,56358   ,290.6,286.1,282
XS GIS Cut Line= 2
     2310527.603      600378.098     2309720.081      600797.638
#Sta/Elev= 30
       0 3098.87    21.9 3093.46    35.4 3087.77      79 3073.84   162.9 3044.32
   238.3 3015.86     293 2987.89   310.3 2980.64   337.1  2971.4   373.5 2961.56
   391.5 2951.06   414.1 2949.27   423.1 2944.15   432.1 2941.75   466.5 2941.56
   481.7  2942.1   485.4 2944.03   495.2  2949.3   522.2 2948.97   538.8 2953.31
   556.6 2951.92   570.6 2953.55   585.3 2958.57     610  2961.5   711.6 2973.76
   774.7 2983.37   873.8 3007.17     883 3008.05   900.7  3013.3     910 3014.47
#Mann= 5 ,-1,0
       0      .1       0     280     .06       0   423.1    .045       0
   485.4     .06       0     610      .1       0
#XS Ineff= 2 , 0
                          540.24         2957.91
Permanent Ineff=
       F       F
Bank Sta=423.1,485.4
XS Rating Curve= 0 ,0
Exp/Cntr=0.3,0.1

Type RM Length L Ch R = 1 ,56072   ,282.7,277.9,274.7
XS GIS Cut Line= 2
2310318.49848764600121.3341222012309670.34183957600540.939665722
#Sta/Elev= 30
       0 3069.73     7.1  3068.1    50.4 3053.72    59.9  3051.7    74.2 3046.73
    98.1 3040.43   143.3 3025.57   160.7 3021.03     241 2991.44   264.8 2984.38
   286.8 2976.64   301.5 2973.32   319.2 2966.79   345.8  2950.3   357.3 2950.59
   368.9 2949.64   386.3 2943.92   398.3  2941.7   435.4 2943.88   455.4 2948.15
   484.6 2947.87   493.6  2949.3   503.1 2952.58   510.6 2954.13     528 2953.67
   593.6 2958.87   610.6 2962.12   688.9 2972.45   724.7 2980.07   772.1 2992.59
#Mann= 5 ,-1,0
       0      .1       0     350     .06       0   386.3    .045       0
   435.4     .06       0     530      .1       0
#XS Ineff= 2 , 0
                          514.25         2961.46
Permanent Ineff=
       F       F
Bank Sta=386.3,435.4
XS Rating Curve= 0 ,0
Exp/Cntr(USF)=0,0
Exp/Cntr=0.3,0.1

Type RM Length L Ch R = 1 ,55794   ,430.9,363.5,271.4
BEGIN DESCRIPTION:
xs 4
END DESCRIPTION:
XS GIS Cut Line= 3
2310147.08515923599857.0719075592309927.46183219600028.485235975
2309557.85184279600319.530783183
#Sta/Elev= 30
       0 3049.63    19.7 3042.46    69.7 3029.07   104.7 3015.91   136.7 3008.19
   182.2 2993.28   235.8 2980.36   287.1 2963.69   323.5 2955.31   333.7 2949.81
   359.2 2948.85   379.5 2943.49   389.6 2941.81   420.2 2941.62   428.4 2941.78
   434.9 2943.63   449.5 2946.88   501.7 2945.33   517.8 2952.84   526.4 2954.97
   537.3 2954.37   549.2  2952.2   562.8 2953.91   598.4 2955.01   644.3 2958.25
   654.7 2961.66   661.2 2965.52   674.1 2975.31   677.4 2976.58     749 2994.93
#Mann= 6 ,-1,0
       0      .1       0     260     .06       0   379.5    .045       0
   434.9      .1       0   458.6     .06       0   578.6      .1       0
#XS Ineff= 2 , 0
                          530.03         2962.46
Permanent Ineff=
       F       F
Bank Sta=379.5,434.9
XS Rating Curve= 0 ,0
Exp/Cntr(USF)=0,0
Exp/Cntr=0.5,0.3

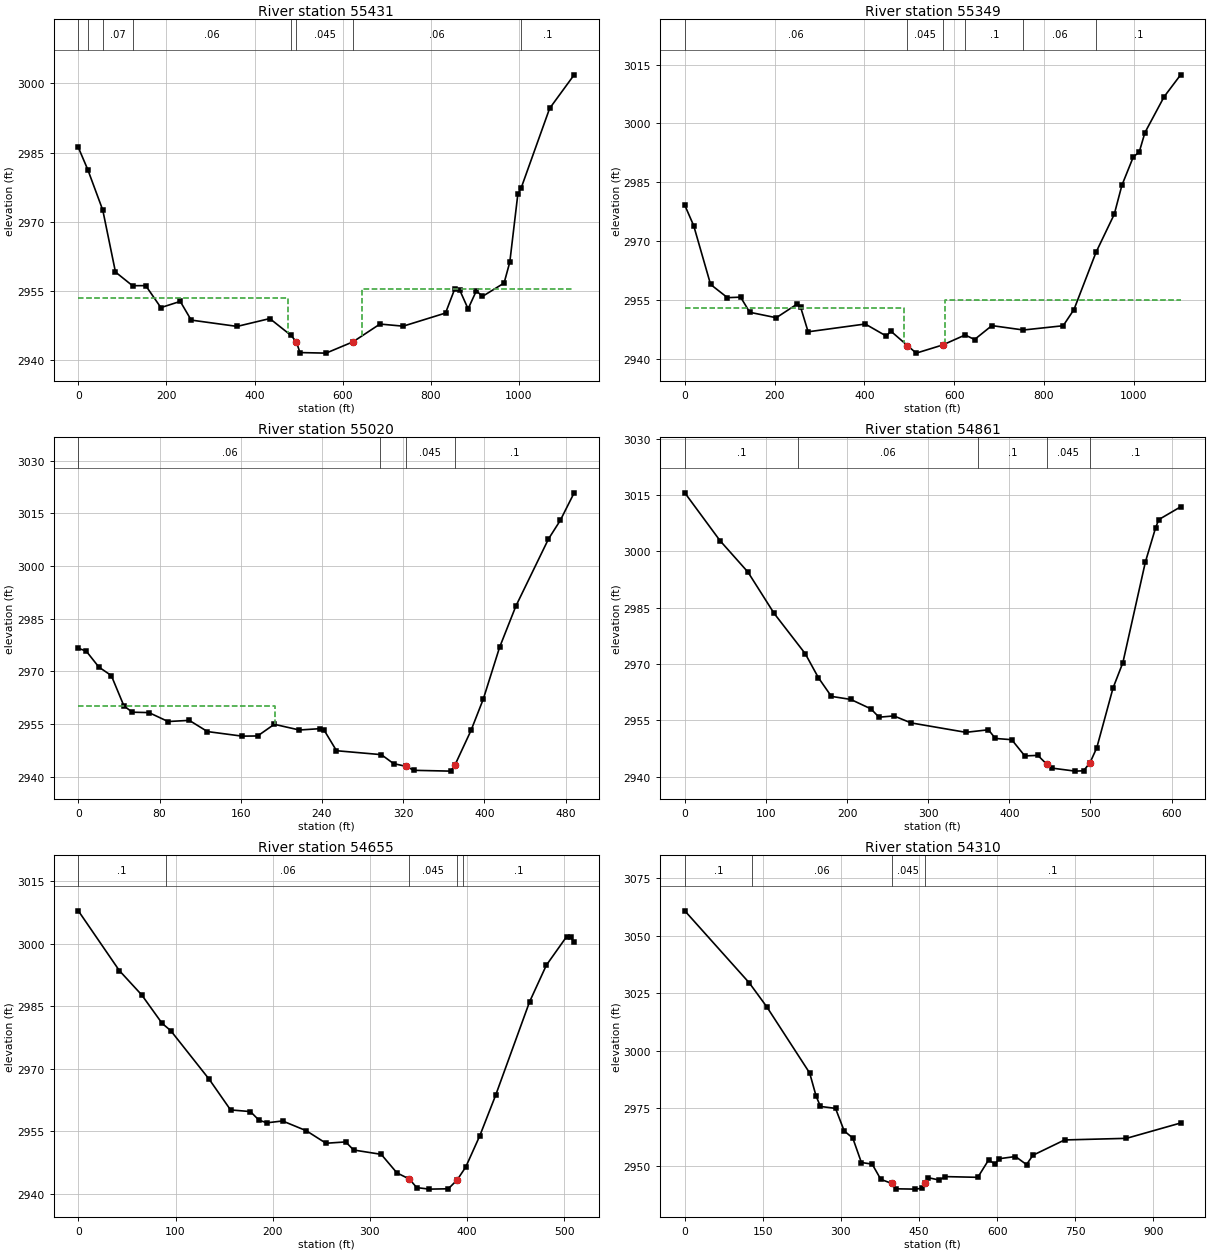
Type RM Length L Ch R = 1 ,55431   ,66.7,81.8,126.5
BEGIN DESCRIPTION:
xs 3
END DESCRIPTION:
XS GIS Cut Line= 6
2309902.62340832599407.6645869982309662.99594827599501.740552793
2309632.82063849 599709.417684832309632.82063849599838.994015076
2309687.84620339600069.746384006 2309538.7446727600320.023953385
#Sta/Elev= 30
       0 2986.12    21.6 2981.27    55.5 2972.51    84.3 2959.08     123 2956.11
     153 2956.13   187.4 2951.36   231.4 2952.71   256.2 2948.65   360.5 2947.28
   434.7 2948.98   483.1 2945.31   495.1 2943.91   503.1  2941.6   562.4 2941.48
   623.6 2943.93   684.8 2947.79   737.5 2947.33   833.7 2950.18   854.1  2955.3
   866.3 2955.08   884.9 2951.09   903.7 2955.01   917.5 2953.79   966.6 2956.69
   979.6 2961.24   997.8 2975.96  1005.6 2977.38    1070 2994.59  1125.7 3001.88
#Mann= 8 ,-1,0
       0      .1       0    21.6     .06       0    55.5     .07       0
     123     .06       0   483.1      .1       0   495.1    .045       0
   623.6     .06       0  1005.6      .1       0
#XS Ineff= 2 , 0
             475 2953.51     643          2955.4
Permanent Ineff=
       F       F
Bank Sta=495.1,623.6
XS Rating Curve= 0 ,0
Exp/Cntr(USF)=0,0
Exp/Cntr=0.5,0.3

Type RM Length L Ch R = 1 ,55349   ,244.6,328.9,404
BEGIN DESCRIPTION:
xs 2
END DESCRIPTION:
XS GIS Cut Line= 6
2309883.09820787599391.6894229952309620.39551093 599471.56524301
2309584.89514648 599688.117466162309577.79507359599847.869106189
2309620.39551093 600023.595910222309526.31954514600275.648497821
#Sta/Elev= 30
       0 2979.14    19.8 2973.93    57.4 2958.94      95 2955.56   124.3 2955.69
   144.6 2951.83   203.7 2950.44   249.7  2953.9   258.1 2953.06   274.6 2946.85
   401.9 2948.84     449 2945.74   458.6 2947.04   495.7 2943.35   515.3 2941.41
     574 2943.48   624.3 2946.04   645.2 2944.88   683.8 2948.43   754.1 2947.31
   842.6  2948.4   866.6 2952.53   915.7 2967.13   956.3 2976.83   973.3 2984.22
   998.9 2991.52  1011.8 2992.66  1024.6 2997.67  1067.3 3006.81  1104.1 3012.41
#Mann= 6 ,-1,0
       0     .06       0   495.7    .045       0     574     .06       0
   624.3      .1       0   754.1     .06       0   915.7      .1       0
#XS Ineff= 2 , 0
             489    2953     580            2955
Permanent Ineff=
       F       F
Bank Sta=495.7,574
XS Rating Curve= 0 ,0
Exp/Cntr(USF)=0,0
Exp/Cntr=0.5,0.3

Type RM Length L Ch R = 1 ,55020   ,158.7,159,161.2
BEGIN DESCRIPTION:
xs 1
END DESCRIPTION:
XS GIS Cut Line= 3
2309879.80219466599378.1128572882309648.91517351599433.895253029
2309398.93740291599412.468586977
#Sta/Elev= 30
       0 2976.58     7.8 2975.76    20.2 2971.23    32.5  2968.8    44.9 2960.17
    53.1 2958.38    69.6 2958.26    88.4 2955.72   109.3 2956.05   127.2 2952.86
   161.3 2951.56   176.6 2951.61     193 2954.93   217.7 2953.31   238.3 2953.69
   242.3 2953.17   254.3 2947.41   298.5 2946.29   310.5 2943.74   322.6 2942.97
   330.6 2941.83   366.7  2941.6   370.8 2943.22   386.9 2953.25   398.9 2962.12
   414.9 2976.81     431 2988.59   463.1 3007.69   474.7 3012.96   488.4 3020.83
#Mann= 4 ,-1,0
       0     .06       0  297.53      .1       0   322.6    .045       0
   370.8      .1       0
#XS Ineff= 2 , 0
           193.8 2960.23
Permanent Ineff=
       F       F
Bank Sta=322.6,370.8
XS Rating Curve= 0 ,0
Exp/Cntr(USF)=0,0
Exp/Cntr=0.3,0.1

Type RM Length L Ch R = 1 ,54861   ,203.8,206.5,208
XS GIS Cut Line= 3
2309996.56674488599445.5763302452309794.34729674599295.838438978
2309437.56863401599251.462983414
#Sta/Elev= 30
       0  3015.6    43.5 3002.84    77.8 2994.51     110 2983.53   148.5 2972.76
   164.7 2966.37   180.7  2961.4   204.6 2960.59   229.4 2958.08   239.4 2955.86
   257.8  2956.2   278.7 2954.35   346.5 2951.83   374.3 2952.51   382.8  2950.2
     403 2949.87   419.1 2945.55   435.2 2945.69     446 2943.38   453.1 2942.29
   481.2  2941.5   491.6 2941.59   499.6 2943.79   507.8 2947.69   527.9 2963.64
     540 2970.38   567.8 2997.22   580.3 3006.26   584.3 3008.48   611.2 3011.87
#Mann= 5 ,-1,0
       0      .1       0     140     .06       0  361.62      .1       0
     446    .045       0   499.6      .1       0
Bank Sta=446,499.6
XS Rating Curve= 0 ,0
Exp/Cntr=0.3,0.1

Type RM Length L Ch R = 1 ,54655   ,339.5,344.1,347.4
XS GIS Cut Line= 3
2309966.52406433599033.1357420422309815.64751541599102.361452721
2309476.61903491599043.785851377
#Sta/Elev= 30
       0 3007.91    42.2 2993.56    65.2 2987.73    86.2  2980.9      95 2979.17
   134.8 2967.43   156.6 2960.13     177 2959.73   185.8 2957.68   193.9 2957.03
   210.1 2957.48   234.5 2955.14   254.8 2952.13   275.1 2952.45   283.2 2950.51
   311.6 2949.47   327.8 2945.01   340.6 2943.54   348.1 2941.49   360.9 2941.12
   380.6  2941.2   389.6 2943.29   398.5 2946.39   413.1 2953.97   429.3 2963.64
   464.2 2986.06   481.5 2994.86   502.3  3001.7   506.4 3001.55   510.1 3000.44
#Mann= 5 ,-1,0
       0      .1       0      90     .06       0   340.6    .045       0
   389.6     .06       0     396      .1       0
Bank Sta=340.6,389.6
XS Rating Curve= 0 ,0
Exp/Cntr(USF)=0,0
Exp/Cntr=0.3,0.1

Type RM Length L Ch R = 1 ,54310   ,240.1,232.8,225.9
XS GIS Cut Line= 3
2310111.84298178598846.2294351012309514.76617422598685.522755972
2309383.25232334598992.953103757
#Sta/Elev= 30
       0 3060.91   123.9 3029.54   157.3 3019.19   239.9 2990.32   252.3 2980.25
   260.6 2975.75   289.6 2974.91   306.2 2965.12   322.8 2961.96   339.3 2951.33
     360 2950.65   376.6 2944.01   397.42942.247   405.6 2939.89   442.9 2939.75
   455.3 2940.11     4612942.484   467.7 2944.74   488.5 2943.72   500.9  2945.2
     563 2944.89   583.7 2952.42   596.2 2950.69   604.4    2953   635.4 2953.94
   656.6 2950.44   668.8 2954.48   729.7 2961.16   848.6 2961.86   952.7 2968.54
#Mann= 4 ,-1,0
       0      .1       0     130     .06       0   397.4    .045       0
     461      .1       0
Bank Sta=397.4,461
XS Rating Curve= 0 ,0
Exp/Cntr=0.3,0.1

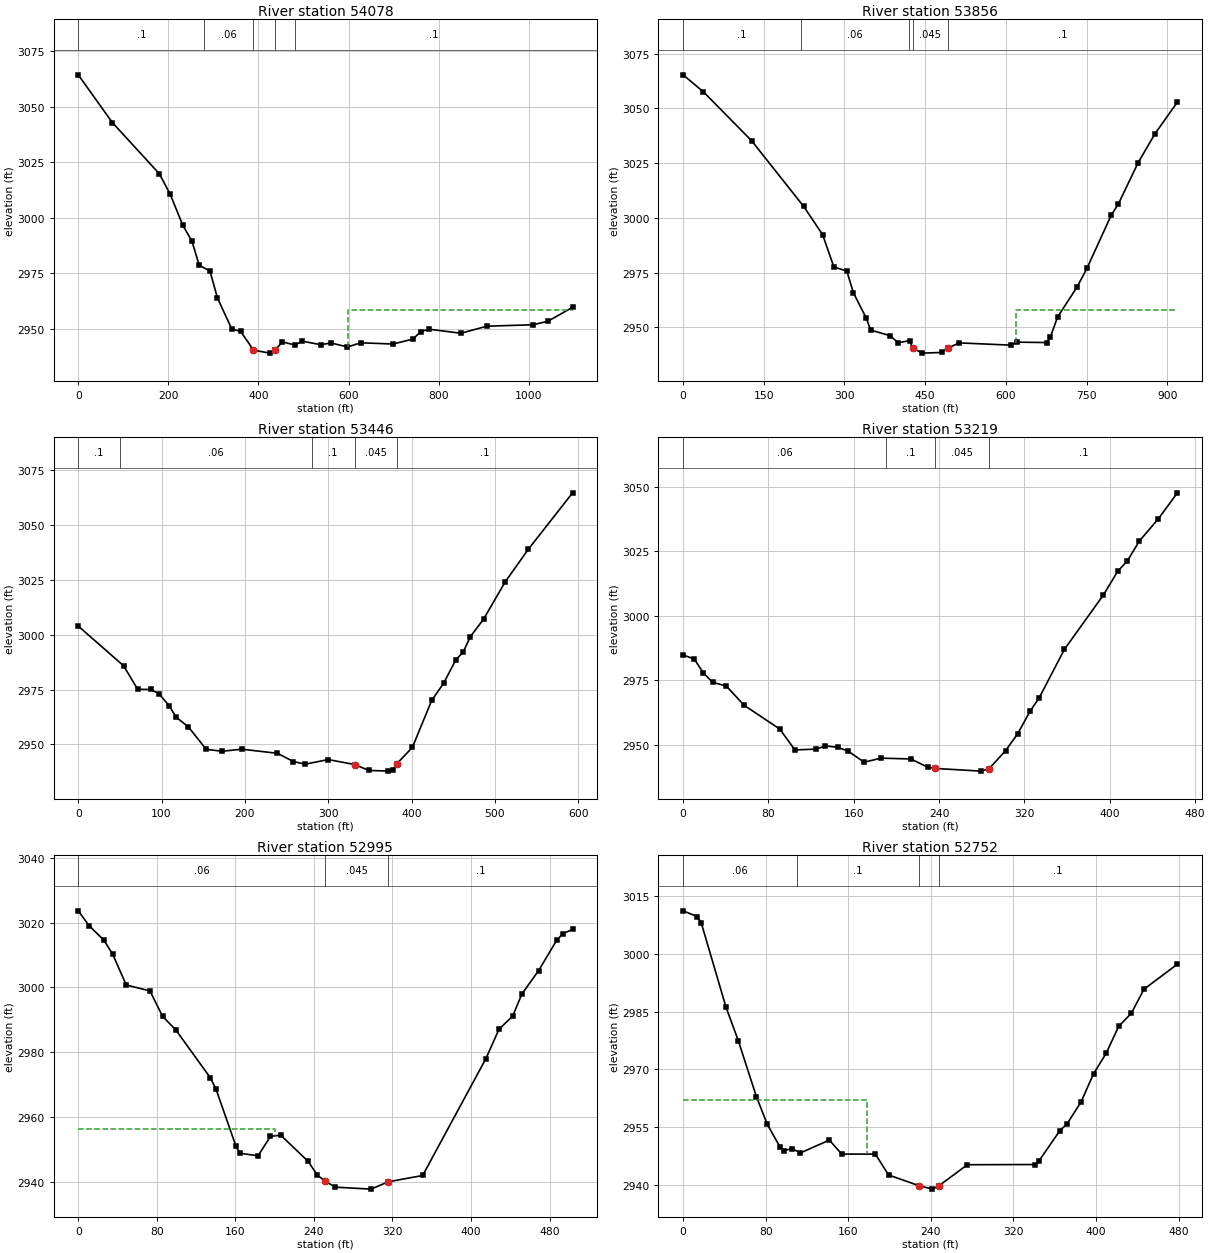
Type RM Length L Ch R = 1 ,54078   ,221.1,221.6,223.1
XS GIS Cut Line= 4
2310163.52859283598544.0047162942309561.70895346598491.995611657
2309405.56885759598817.2556976272309380.14880892598947.104695996
#Sta/Elev= 30
       0 3064.49    75.6 3043.01     180  3019.9   204.1 3010.68   232.2 2996.61
   252.3 2989.62   268.4 2978.69   292.4 2976.08   308.7  2964.1   340.6 2950.04
   360.7 2948.87   388.8 2940.48   424.9 2939.11     437 2940.47     453 2944.17
   481.1 2942.76   497.2  2944.5   537.9 2942.91   561.4 2943.68   597.6 2941.88
   627.1 2943.77   698.6 2943.21   742.9 2945.45   760.7 2948.85   778.4 2949.88
   849.4 2948.07   907.1 2951.25  1009.6 2951.89  1042.2 2953.45  1097.2 2959.75
#Mann= 5 ,-1,0
       0      .1       0     280     .06       0   388.8    .045       0
     437     .06       0     480      .1       0
#XS Ineff= 2 , 0
                          599.17         2958.76
Permanent Ineff=
       F       F
Bank Sta=388.8,437
XS Rating Curve= 0 ,0
Exp/Cntr(USF)=0,0
Exp/Cntr=0.3,0.1

Type RM Length L Ch R = 1 ,53856   ,390.1,410.5,430.2
XS GIS Cut Line= 3
     2310207.466       598326.782309574.52087221598271.688877223
2309358.32639216598088.380490396
#Sta/Elev= 30
       0 3065.36    37.8  3057.6   127.8 3035.13   224.1 3005.25   259.4 2992.34
   280.3 2977.57   304.4 2975.69   316.5 2965.84   340.6 2954.13   348.6 2948.75
     385 2946.15   399.7 2942.95   420.9 2943.88   427.42940.381     445  2938.2
   481.1 2938.51     4922940.438   513.2 2942.88   609.6 2941.84   621.6 2943.21
   675.7 2943.03   682.5  2945.4   696.1 2954.71     732 2968.26   750.6  2976.9
   795.7 3001.14   809.1 3006.34     846 3025.29   877.2 3038.44   918.8 3052.91
#Mann= 5 ,-1,0
       0      .1       0     220     .06       0     420      .1       0
   427.4    .045       0     492      .1       0
#XS Ineff= 2 , 0
                          618.18         2958.03
Permanent Ineff=
       F       F
Bank Sta=427.4,492
XS Rating Curve= 0 ,0
Exp/Cntr=0.3,0.1

Type RM Length L Ch R = 1 ,53446   ,223.7,226.2,228.5
XS GIS Cut Line= 2
 2310125.2607062 598082.63814578 2309626.4842938 597761.30415026
#Sta/Elev= 30
       0    3004    54.4 2985.88    71.3 2975.15    86.9 2975.06    96.5 2973.23
   108.9 2967.75   117.6 2962.39   132.1 2958.02   153.6 2947.75   172.6 2946.88
   196.4 2947.81   239.1 2945.94   258.2 2942.18   272.5 2940.98   299.9 2943.08
   331.7 2940.83   348.6 2938.15   372.3 2937.81   377.2 2938.34     382 2941.03
     401 2948.63   424.3 2970.14   438.5 2977.89   453.3 2988.69     462  2992.1
   470.6 2999.17   486.6 3007.24   512.3 3024.09   540.1 3038.99   593.3  3064.8
#Mann= 5 ,-1,0
       0      .1       0      50     .06       0     280      .1       0
   331.7    .045       0     382      .1       0
Bank Sta=331.7,382
XS Rating Curve= 0 ,0
Exp/Cntr=0.3,0.1

Type RM Length L Ch R = 1 ,53219   ,229.9,224.1,218.6
XS GIS Cut Line= 3
2310164.94071427597859.0352981992309882.82294458597651.910859696
2309782.83183634597598.344194565
#Sta/Elev= 30
       0 2984.83    10.5 2983.25      19 2977.85    27.6 2974.26    40.6 2972.73
    57.2  2965.3    90.6 2956.07   104.9 2947.95   124.8 2948.27   133.5 2949.51
   144.9 2948.97   154.8 2947.48   169.7 2943.18   185.6 2944.76   213.6 2944.44
   229.2 2941.26   236.5 2940.76   279.4 2939.72     287 2940.69   302.3 2947.66
   313.8 2954.27   325.2 2962.93   333.8 2968.14   357.5 2987.01   393.8 3007.96
   407.4 3017.26   416.5 3021.37   427.8 3029.08   445.6 3037.71   463.4 3047.78
#Mann= 4 ,-1,0
       0     .06       0     190      .1       0   236.5    .045       0
     287      .1       0
Bank Sta=236.5,287
XS Rating Curve= 0 ,0
Exp/Cntr(USF)=0,0
Exp/Cntr=0.3,0.1

Type RM Length L Ch R = 1 ,52995   ,255.8,243.5,231.7
XS GIS Cut Line= 2
2310346.37796395597678.7968382432309911.49849943597424.969232419
#Sta/Elev= 30
       0 3023.61    11.1 3019.02    26.2 3014.53      35 3010.28    48.9 3000.77
      73 2998.94    85.9  2991.1    99.3 2986.95   134.4 2972.24   140.2 2968.77
   160.7 2951.05   164.7 2948.93   183.2 2948.15   195.8 2954.16   206.3 2954.48
   234.1 2946.44   243.4 2942.25   251.4 2940.32   261.9 2938.49   298.2 2937.88
   315.7 2940.13   350.8 2942.08   415.2 2978.07   428.6 2987.16   442.5 2991.17
   451.8 2997.96   468.9 3005.19   487.2 3014.48   493.5 3016.54   503.5  3017.9
#Mann= 3 ,0,0
       0     .06       0   251.4    .045       0   315.7      .1       0
#XS Ineff= 2 , 0
           200.7  2956.5
Permanent Ineff=
       F       F
Bank Sta=251.4,315.7
XS Rating Curve= 0 ,0
Exp/Cntr(USF)=0,0
Exp/Cntr=0.3,0.1

Type RM Length L Ch R = 1 ,52752   ,211,183.9,151.4
XS GIS Cut Line= 4
2310393.73061945597330.9581609232310216.46738021597322.751529477
2310122.09111858597289.1043405482309924.31130073597326.034182056
#Sta/Elev= 30
       0 3011.24    13.6 3009.76    17.6 3008.11    41.6 2986.17    53.6 2977.38
    71.1 2962.84    81.6 2955.66    93.7 2949.91    97.7 2948.88   105.7 2949.34
   113.7 2948.27   141.7 2951.58   153.7 2947.94   186.3 2947.94     199 2942.52
   228.1 2939.76   241.5 2938.83   247.8  2939.7   275.4 2945.18   340.6 2945.23
   344.5 2946.09     365 2954.06   371.9 2955.79   385.4 2961.48   397.6 2968.85
   409.7 2974.13     422  2981.2   434.2 2984.58   446.4 2990.83   478.8 2997.36
#Mann= 4 ,-1,0
       0     .06       0     110      .1       0   228.1    .045       0
   247.8      .1       0
#XS Ineff= 2 , 0
          178.57 2961.92
Permanent Ineff=
       F       F
Bank Sta=228.1,247.8
XS Rating Curve= 0 ,0
Exp/Cntr(USF)=0,0
Exp/Cntr=0.3,0.1

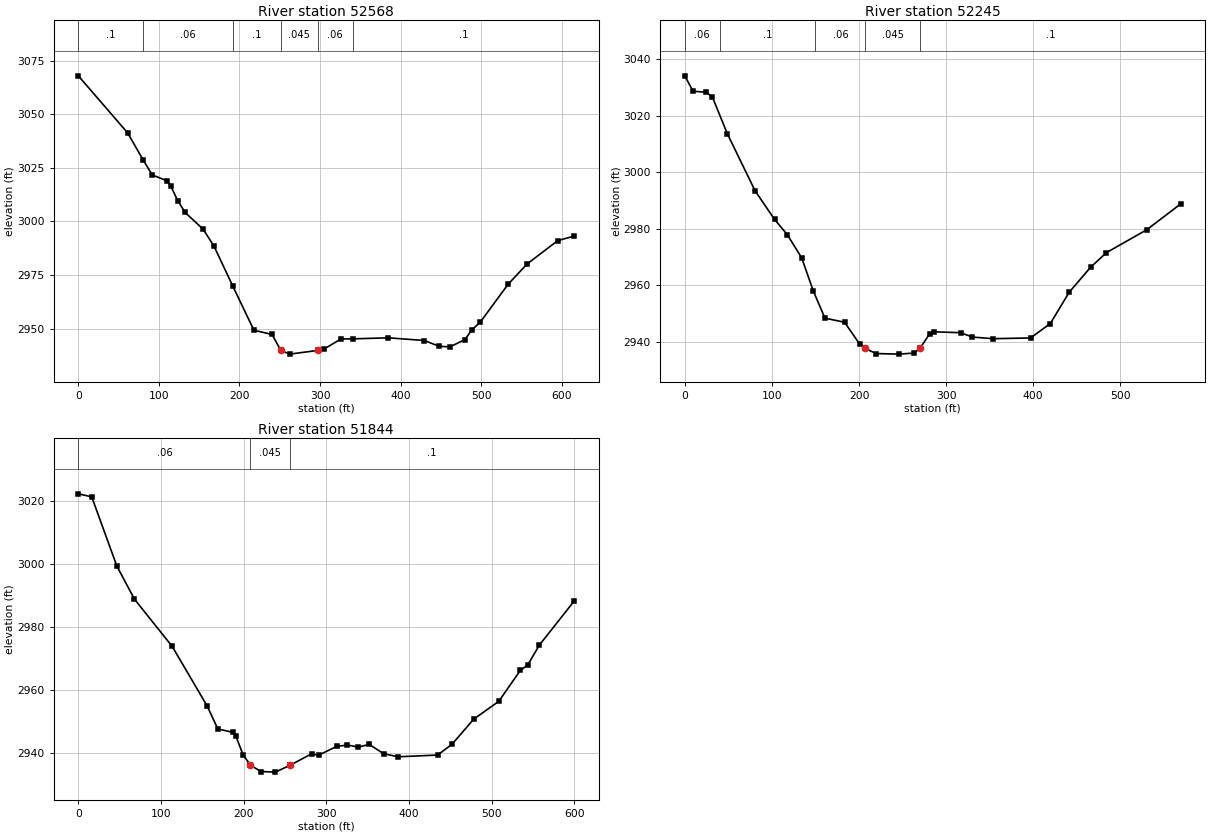
Type RM Length L Ch R = 1 ,52568   ,345.1,322.5,294.3
XS GIS Cut Line= 2
2310445.77898442597004.2899136772309899.07337187597286.517811061
#Sta/Elev= 30
       0 3067.87    61.2 3041.25    80.4 3028.65    91.8 3021.62   109.8 3018.95
   114.7 3016.51   123.3 3009.69   132.5 3004.13   154.9 2996.33   168.4 2988.39
   191.9 2969.61   217.9  2949.2   240.4 2947.24   251.2 2939.81   262.2 2938.06
  297.19 2939.79   304.7 2940.38   325.9 2945.12   340.3 2945.18   384.8 2945.67
   429.4 2944.41   447.5 2941.75     461 2941.41   479.8 2944.86     488 2949.22
     499 2953.07   533.3 2970.64     557 2980.14   594.9    2991   615.3 2993.11
#Mann= 6 ,-1,0
       0      .1       0    80.4     .06       0   191.9      .1       0
   251.2    .045       0  297.19     .06       0   340.3      .1       0
Bank Sta=251.2,297.19
XS Rating Curve= 0 ,0
Exp/Cntr(USF)=0,0
Exp/Cntr=0.3,0.1

Type RM Length L Ch R = 1 ,52245   ,402.2,401.1,399.1
XS GIS Cut Line= 2
2310057.04999368596732.712125628 2309806.7724243 597243.91737372
#Sta/Elev= 30
       0 3034.09     9.4 3028.66    24.9 3028.27    31.7 3026.57    48.8 3013.63
    80.7 2993.42     103 2983.33   117.6 2977.96   134.1 2969.78   147.5 2958.03
   160.9  2948.4   183.4 2946.95   200.9 2939.17   207.3 2937.68   219.3 2935.89
   245.5 2935.68   263.3 2936.05   270.1 2937.75   281.1 2942.88   285.6 2943.57
   316.7 2943.26   330.1 2941.71   353.8 2941.14   396.9  2941.4   419.6 2946.49
   441.4 2957.62   465.9 2966.41   484.1 2971.59   530.5 2979.69   569.2 2988.79
#Mann= 5 ,-1,0
       0     .06       0      40      .1       0     150     .06       0
   207.3    .045       0   270.1      .1       0
Bank Sta=207.3,270.1
XS Rating Curve= 0 ,0
Exp/Cntr(USF)=0,0
Exp/Cntr=0.3,0.1

Type RM Length L Ch R = 1 ,51844   ,260.3,259.5,258.6
XS GIS Cut Line= 2
2309690.59107065596554.2901320372309452.53318223597104.803143541
#Sta/Elev= 30
       0  3022.3    16.2 3021.34    46.6  2999.4    67.9 2988.91   113.6 2973.91
   155.7 2955.11   168.8 2947.76   186.6 2946.74   190.5 2945.55   199.3 2939.58
   208.2 2936.29     221 2934.28   238.3 2934.09   255.9 2936.23   282.1 2939.89
   290.8 2939.47   312.6 2942.26   325.6 2942.67   338.7 2942.03   351.8 2942.87
   369.2 2939.96   386.6 2938.95   434.6  2939.5     452 2942.91   478.2 2950.86
   508.7 2956.55   534.8 2966.39   543.5 2967.98   557.7 2974.35   599.8 2988.31
#Mann= 3 ,-1,0
       0     .06       0   208.2    .045       0   255.9      .1       0
Bank Sta=208.2,255.9
XS Rating Curve= 0 ,0
Exp/Cntr=0.3,0.1