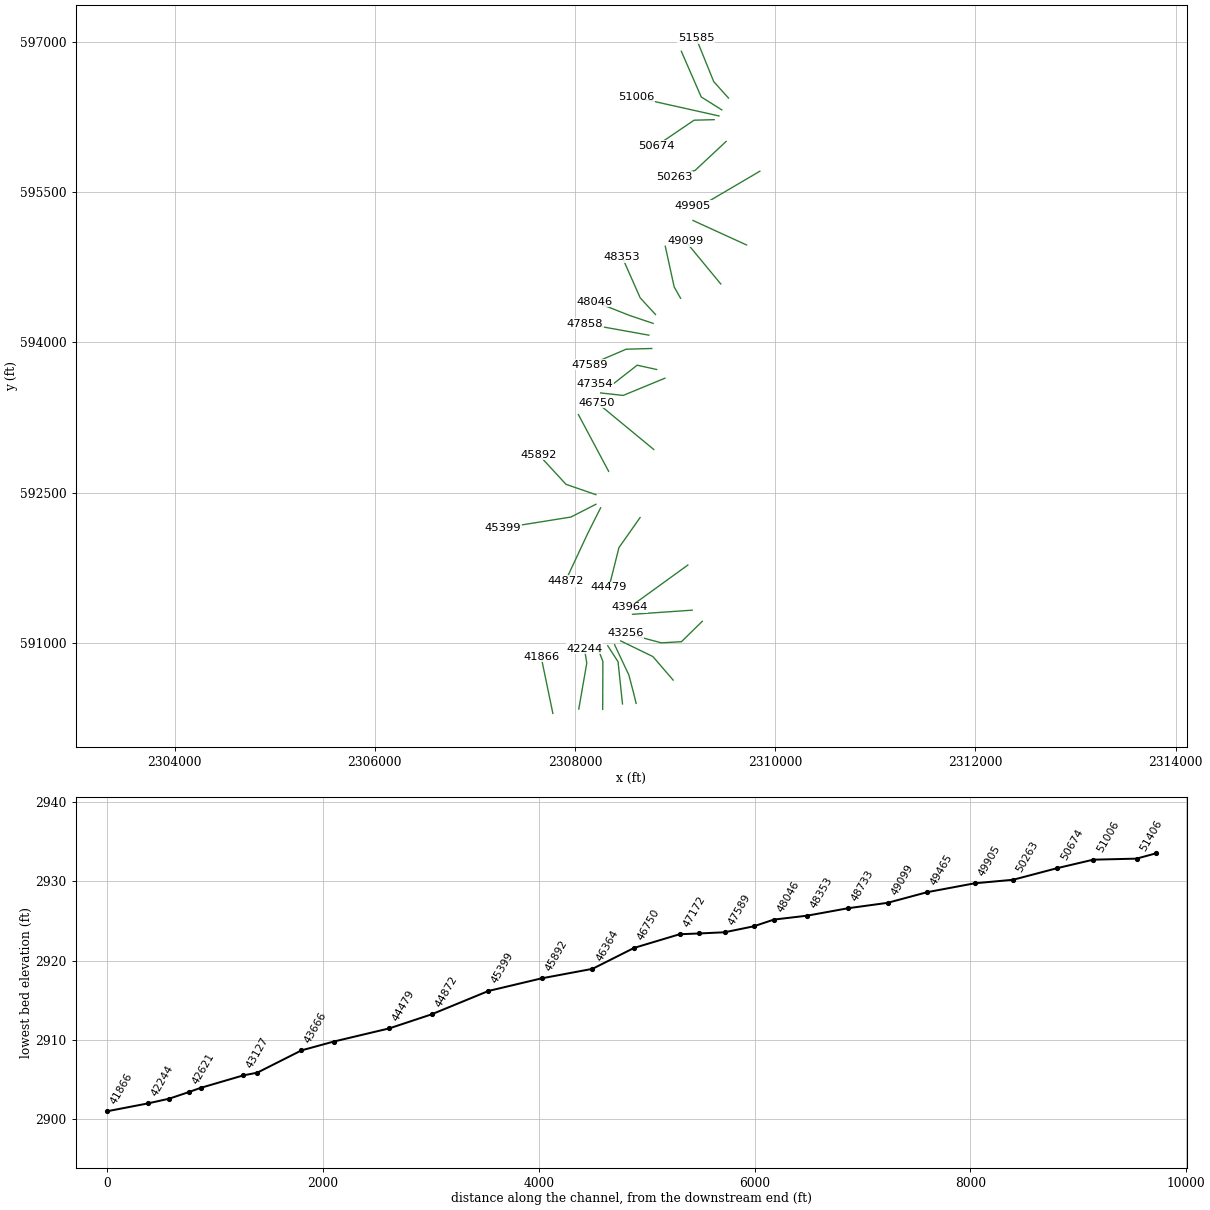
HEC-RAS study WFGRNBRRRV.prj: WFGRNBRRRV

--- WFGRNBRRRV.g01 (geometry) --- (continued)

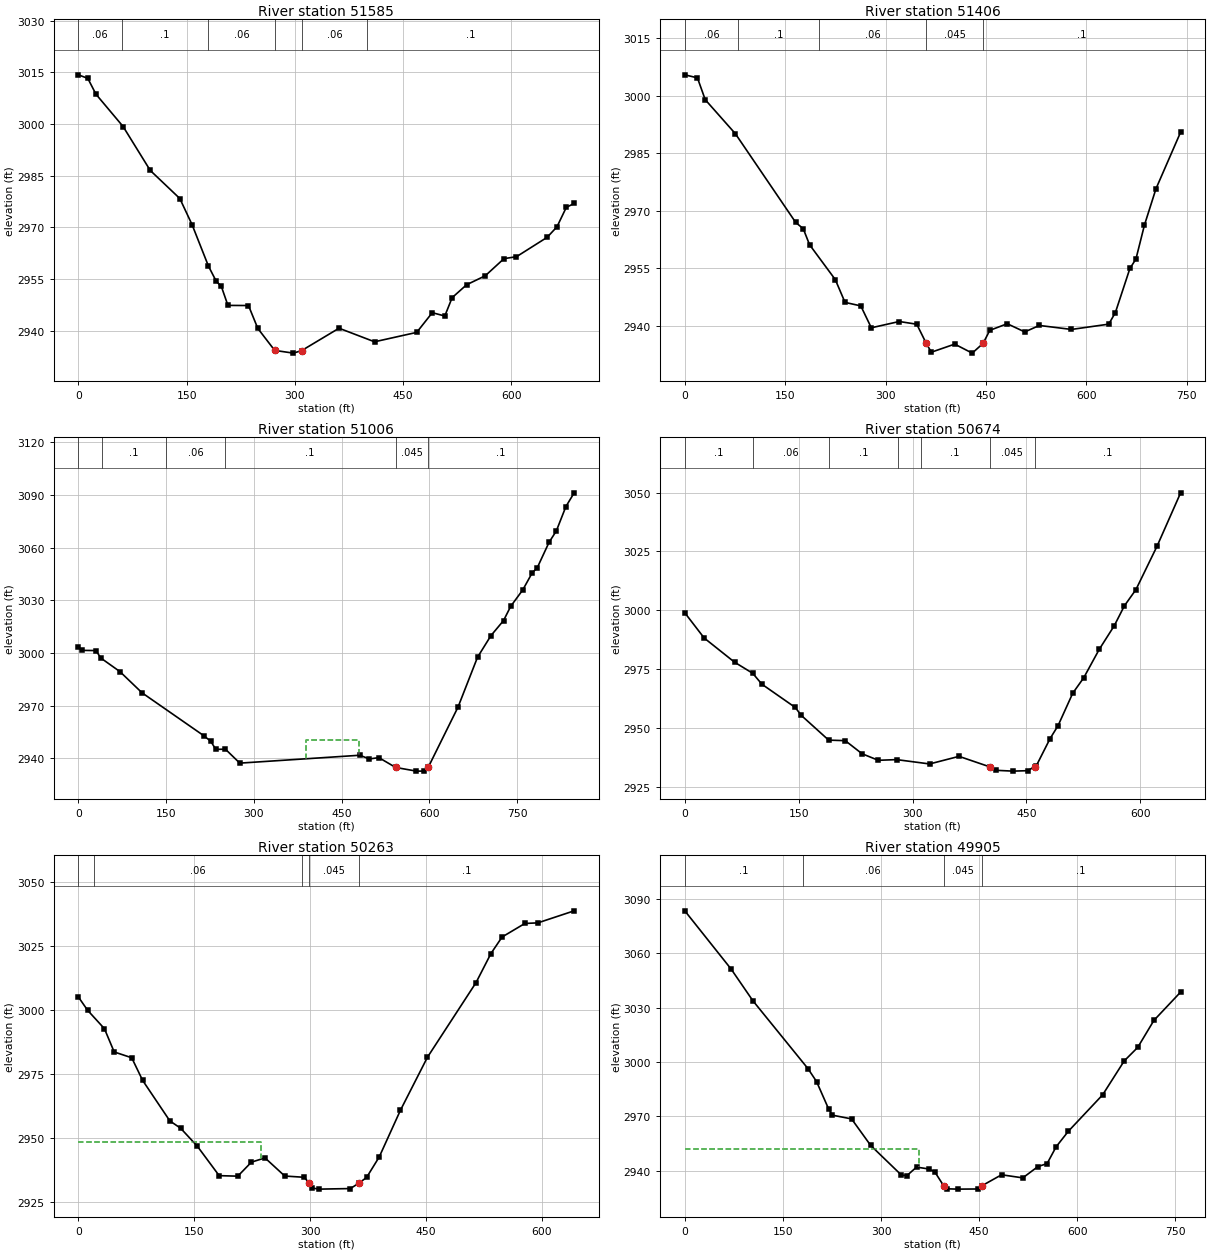
Type RM Length L Ch R = 1 ,51585   ,178.7,178.2,180.2
XS GIS Cut Line= 3
2309532.56630534596439.0543979542309385.24747974596603.050826453
2309210.13264931597035.278701563
#Sta/Elev= 30
       0 3014.29    13.1 3013.27    24.4 3008.67      62 2999.29    99.6 2986.55
   140.6 2978.39   157.6 2970.78   180.3 2958.75     191 2954.39   198.1 2952.88
   207.2 2947.38   235.7 2947.34   248.6  2940.7     272 2934.32   297.9 2933.53
   309.4 2934.27   361.1 2940.76   410.3 2936.82   468.7 2939.55   490.3 2945.27
   507.6  2944.3   517.8 2949.63   537.8 2953.37   563.7 2955.98   589.6 2960.95
   606.9 2961.51   649.4 2967.14     663 2970.19   675.9 2975.82   686.8 2976.97
#Mann= 6 ,-1,0
       0     .06       0      60      .1       0     180     .06       0
     272    .045       0   309.4     .06       0  400.45      .1       0
Bank Sta=272,309.4
XS Rating Curve= 0 ,0
Exp/Cntr(USF)=0,0
Exp/Cntr=0.3,0.1

Type RM Length L Ch R = 1 ,51406   ,348.9,400.3,434.6
XS GIS Cut Line= 3
2309465.96892557596320.9078979982309260.06681176596450.484228244
2309061.26477083596906.663911437
#Sta/Elev= 30
       0 3005.48    18.9 3004.69    30.5    2999    75.6 2990.11   165.7 2966.97
     177 2965.33   186.4 2961.16   224.9 2952.05   239.4 2946.11     263 2945.19
   278.7 2939.48   320.4 2941.12   346.6 2940.41   360.7 2935.45   368.4 2933.11
   403.3 2935.22   429.5 2932.87   445.8 2935.43   455.7 2938.81   481.8 2940.54
     508  2938.4   529.8 2940.09   577.8 2939.05   633.5 2940.43   643.4 2943.45
   665.1 2954.96   674.1 2957.41   686.9 2966.32   704.1 2975.77   740.9 2990.53
#Mann= 5 ,-1,0
       0     .06       0      80      .1       0     200     .06       0
   360.7    .045       0   445.8      .1       0
Bank Sta=360.7,445.8
XS Rating Curve= 0 ,0
Exp/Cntr(USF)=0,0
Exp/Cntr=0.3,0.1

Type RM Length L Ch R = 1 ,51006   ,292.2,332.7,363.1
XS GIS Cut Line= 2
2309437.56863401596260.5572784322308610.41014231596445.159173576
#Sta/Elev= 30
       0 3003.24     5.5 3001.48    30.1 3001.36    38.5  2997.1    71.1 2989.39
   108.9 2977.32   214.5 2952.89   226.2 2949.77     235 2945.13   251.4 2945.23
     276 2937.29   481.1 2941.78   497.3 2939.67   513.7 2940.42   542.4 2934.83
     578 2932.74   591.6 2932.75   598.1 2934.92     649  2969.2   682.3 2997.55
   705.3 3009.89   726.8 3018.44   739.1 3026.58   759.6 3035.86     776 3045.73
   784.2 3048.34   804.7 3063.06     817 3069.44   833.4 3083.34   847.5 3091.15
#Mann= 6 ,-1,0
       0     .06       0      40      .1       0     150     .06       0
     250      .1       0   542.4    .045       0   598.1      .1       0
#XS Ineff= 1 ,-1
  388.71  480.312950.394
Permanent Ineff=
       F
Bank Sta=542.4,598.1
XS Rating Curve= 0 ,0
Exp/Cntr(USF)=0,0
Exp/Cntr=0.3,0.1

Type RM Length L Ch R = 1 ,50674   ,402.8,410,416.8
XS GIS Cut Line= 3
  2309389.643142596223.2818957582309189.06608286596217.956841091
 2308814.5372379595964.129235267
#Sta/Elev= 30
       0 2998.95    25.5 2988.24    65.5 2977.97    89.5 2973.24   101.5 2968.62
   145.5 2958.73   153.5 2955.34   189.5 2944.85   211.4 2944.62   233.5 2939.06
   254.9 2936.28     279 2936.57   322.5 2934.73   361.2 2937.96   401.7  2933.5
   409.5 2932.03   432.3 2931.68   451.6 2931.87   461.1  2933.6   462.7 2933.75
   481.2 2945.54   491.6 2950.96     511 2964.79   525.5 2971.36   545.9 2983.42
   565.7 2993.47   579.1 3001.95   594.2 3008.78   622.1 3027.28   653.1 3049.92
#Mann= 7 ,-1,0
       0      .1       0      90     .06       0     190      .1       0
  280.65     .06       0  310.65      .1       0   401.7    .045       0
   461.1      .1       0
Bank Sta=401.7,461.1
XS Rating Curve= 0 ,0
Exp/Cntr(USF)=0,0
Exp/Cntr=0.3,0.1

Type RM Length L Ch R = 1 ,50263   ,368.2,358.3,348.1
XS GIS Cut Line= 3
2309508.91176087596006.0594533242309199.71619219595717.401702334
2308991.42633025 595650.52907513
#Sta/Elev= 30
       0 3005.25      12 3000.03    33.8 2992.83    46.4 2983.76    69.1 2981.49
    83.2 2972.67   118.5 2956.83   132.3 2954.01     154 2946.98   182.3 2935.47
   206.4 2935.27     224 2940.73   241.6 2942.41   267.2 2935.32   292.6 2934.83
   298.3 2932.68     302 2930.65     312 2930.21   352.1 2930.43   363.4 2932.59
   373.1 2934.76   389.5 2942.78   416.9 2960.98   451.9  2981.7   514.8 3010.84
   534.1 3022.19   548.5 3028.63     578 3033.92   594.8 3034.15   641.8 3038.85
#Mann= 5 ,-1,0
       0      .1       0      20     .06       0     290      .1       0
   298.3    .045       0   363.4      .1       0
#XS Ineff= 2 , 0
          235.83 2948.49
Permanent Ineff=
       F       F
Bank Sta=298.3,363.4
XS Rating Curve= 0 ,0
Exp/Cntr=0.3,0.1

Type RM Length L Ch R = 1 ,49905   ,479.4,440,393.2
XS GIS Cut Line= 3
 2309845.8228252595708.5266112212309316.86739488595397.898422276
 2309176.6409553595362.398057826
#Sta/Elev= 30
       0 3083.51    70.9  3051.3     104 3033.88   188.3 2996.34   201.4 2989.22
   219.9 2974.06   225.8 2970.61     255 2968.55   284.2 2953.91   331.3 2937.48
   339.7 2937.24   354.3 2941.93     373  2940.9   382.3 2939.23   396.2  2931.4
   400.8 2929.93   417.4 2929.76   447.9 2929.84   453.7  2931.5   484.3 2937.69
   516.8 2935.98     540 2942.25   553.9 2943.84   567.8 2953.17   586.4 2961.72
   638.9 2981.87   671.9 3000.61   692.5 3008.06   717.3    3023   758.1 3038.62
#Mann= 4 ,-1,0
       0      .1       0     180     .06       0   396.2    .045       0
   453.7      .1       0
#XS Ineff= 2 , 0
          357.86 2951.88
Permanent Ineff=
       F       F
Bank Sta=396.2,453.7
XS Rating Curve= 0 ,0
Exp/Cntr(USF)=0,0
Exp/Cntr=0.3,0.1

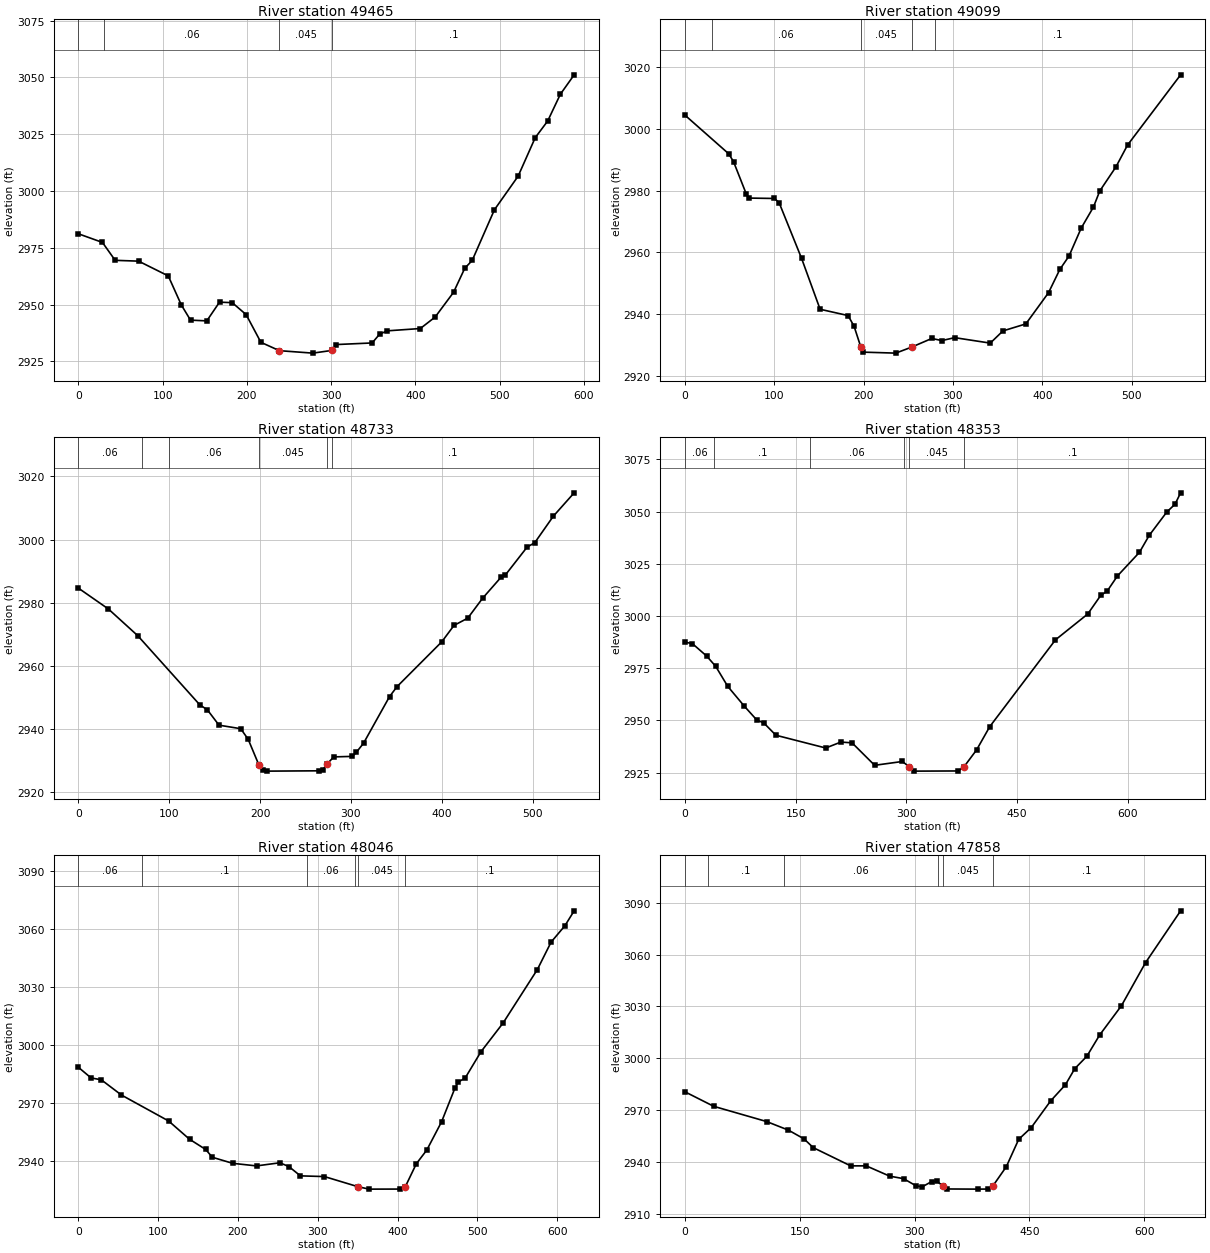
Type RM Length L Ch R = 1 ,49465   ,383.7,366.2,344.7
XS GIS Cut Line= 2
2309713.21359686594972.2775853612309178.14274936595216.840164003
#Sta/Elev= 30
       0 2981.17    28.6 2977.36    43.7 2969.48    71.5 2969.12   106.7 2962.63
   122.2 2949.84   133.1 2943.16   152.4 2942.83   167.5 2951.07   182.6 2950.85
   199.1 2945.59   216.6  2933.4   238.6 2929.72   278.2 2928.64   301.42929.859
   306.3 2932.42   348.6 2933.12   357.6 2937.03   366.7 2938.45   405.8 2939.47
   423.4 2944.54   445.2 2955.41   458.5 2965.98   467.3 2969.42   493.7 2991.74
   521.8 3006.51   542.1 3023.45   556.9  3030.8   571.9 3042.56   588.3 3051.12
#Mann= 4 ,-1,0
       0      .1       0      30     .06       0   238.6    .045       0
   301.4      .1       0
Bank Sta=238.6,301.4
XS Rating Curve= 0 ,0
Exp/Cntr=0.3,0.1

Type RM Length L Ch R = 1 ,49099   ,384.3,365.6,342.5
XS GIS Cut Line= 2
2309455.31881624594583.1650581292309102.09018995595010.944449762
#Sta/Elev= 30
       0 3004.56    49.1 2991.99    54.5 2989.45      69 2978.79    71.9 2977.61
   100.3 2977.48   105.5 2976.14   130.6  2958.1   151.4 2941.53   182.7 2939.49
   189.4 2936.02   196.9 2929.33   199.7 2927.62     236  2927.3   253.7 2929.24
   276.4 2932.06   287.6 2931.37     302 2932.32   341.8 2930.55     356 2934.51
   381.6 2936.78     407 2946.91   419.6 2954.44   429.9 2958.79   443.5 2967.84
   457.3 2974.73   464.3  2979.9   482.4 2987.72   495.4 2994.81   554.8  3017.6
#Mann= 5 ,-1,0
       0      .1       0      30     .06       0   196.9    .045       0
   253.7     .06       0     280      .1       0
Bank Sta=196.9,253.7
XS Rating Curve= 0 ,0
Exp/Cntr(USF)=0,0
Exp/Cntr=0.3,0.1

Type RM Length L Ch R = 1 ,48733   ,369.9,380.4,390.8
XS GIS Cut Line= 3
2309053.95101598594440.3442049282308990.26404193594552.989748346
2308901.09792711594959.568469307
#Sta/Elev= 30
       0 2984.61    33.1 2977.98    65.3 2969.55   133.7 2947.61   141.9 2946.07
   154.8 2941.18   178.7 2940.06   186.9  2936.7   198.5 2928.71   203.3 2926.91
   207.4 2926.62   264.7 2926.72   268.8    2927   273.8 2928.91   281.1 2931.13
   301.6 2931.29     306 2932.61   313.9 2935.49   342.5 2950.26   350.7 2953.39
   399.9 2967.58   413.4 2972.79   428.5 2975.08   444.9 2981.41   465.4 2988.13
   469.5 2988.61   493.9 2997.62   502.2 2998.97   522.7 3007.39   545.6 3014.79
#Mann= 6 ,-1,0
       0     .06       0      70      .1       0     100     .06       0
   198.5    .045       0   273.8     .06       0   279.4      .1       0
Bank Sta=198.5,273.8
XS Rating Curve= 0 ,0
Exp/Cntr=0.3,0.1

Type RM Length L Ch R = 1 ,48353   ,266.3,307.1,343.8
XS GIS Cut Line= 3
2308803.03879731 594278.389148022308650.11741912594444.907888425
2308470.44560134594852.101943093
#Sta/Elev= 30
       0 2987.47    10.1 2986.83    29.5 2980.84    41.8 2975.91    58.1 2966.31
    80.4 2956.87    97.4  2950.2     107 2948.75   123.3 2942.88   190.8 2936.76
   211.2  2939.6   226.4 2939.24     257 2928.47   294.5  2930.3   303.6 2927.83
   310.2 2925.68   370.3 2925.76   378.12927.839     395 2935.85   412.8 2946.99
   501.8  2988.6   545.5 3000.98     563 3009.86   571.8 3011.96   585.7 3019.21
   615.5 3030.54   628.6  3038.6   652.5 3049.84   663.6 3053.57   671.2 3059.03
#Mann= 6 ,-1,0
       0     .06       0      40      .1       0     170     .06       0
  296.08      .1       0   303.6    .045       0   378.1      .1       0
Bank Sta=303.6,378.1
XS Rating Curve= 0 ,0
Exp/Cntr=0.3,0.1

Type RM Length L Ch R = 1 ,48046   ,177.5,187.8,195.7
XS GIS Cut Line= 3
 2308779.3496429594189.7187367762308545.44187183594268.283178967
2308197.25854848594405.770952801
#Sta/Elev= 30
       0 2988.38      16 2982.83    28.7 2981.89      54 2973.97   113.1 2960.52
   139.3 2951.05   159.5 2945.76   167.9  2941.7   193.2 2938.58   223.2 2937.23
   252.4 2938.85   263.8 2936.88   278.2 2932.07   308.3  2931.7   350.2 2926.46
   364.2 2925.19   402.9 2925.22  409.58 2926.44   423.4 2938.35   436.5 2945.45
     455 2960.08   471.7 2977.51     476 2980.73   484.6 2982.81   504.3 2996.38
   532.1 3011.33     575 3039.03   592.2 3053.25   609.4 3061.68   621.1 3069.47
#Mann= 6 ,-1,0
       0     .06       0      80      .1       0  286.75     .06       0
  346.75      .1       0   350.2    .045       0  409.58      .1       0
Bank Sta=350.2,409.58
XS Rating Curve= 0 ,0
Exp/Cntr(USF)=0,0
Exp/Cntr=0.3,0.1

Type RM Length L Ch R = 1 ,47858   ,240.3,269.3,292.8
XS GIS Cut Line= 2
2308737.33185198594071.8042551162308100.17780403594186.274708439
#Sta/Elev= 30
       0 2980.67    37.8 2972.23   106.8 2963.43   135.3 2958.46   155.6 2953.42
   167.8 2948.32   216.6 2937.79   236.9  2937.8   267.5 2931.85   285.7 2930.39
   301.9 2926.25     310 2925.67   322.2 2928.69   329.5 2928.82   336.6 2926.26
   342.6 2924.43   383.2 2924.34   395.4 2924.38   401.8 2925.88   419.8 2937.32
     436 2953.16   452.3  2959.9   477.6 2975.32     497 2984.72   509.2 2994.02
   524.9 3001.15   541.7 3013.49   570.1 3030.41   601.6 3055.33   647.4  3085.3
#Mann= 6 ,-1,0
       0     .06       0      30      .1       0     130     .06       0
     330      .1       0   336.6    .045       0   401.8      .1       0
Bank Sta=336.6,401.8
XS Rating Curve= 0 ,0
Exp/Cntr=0.3,0.1

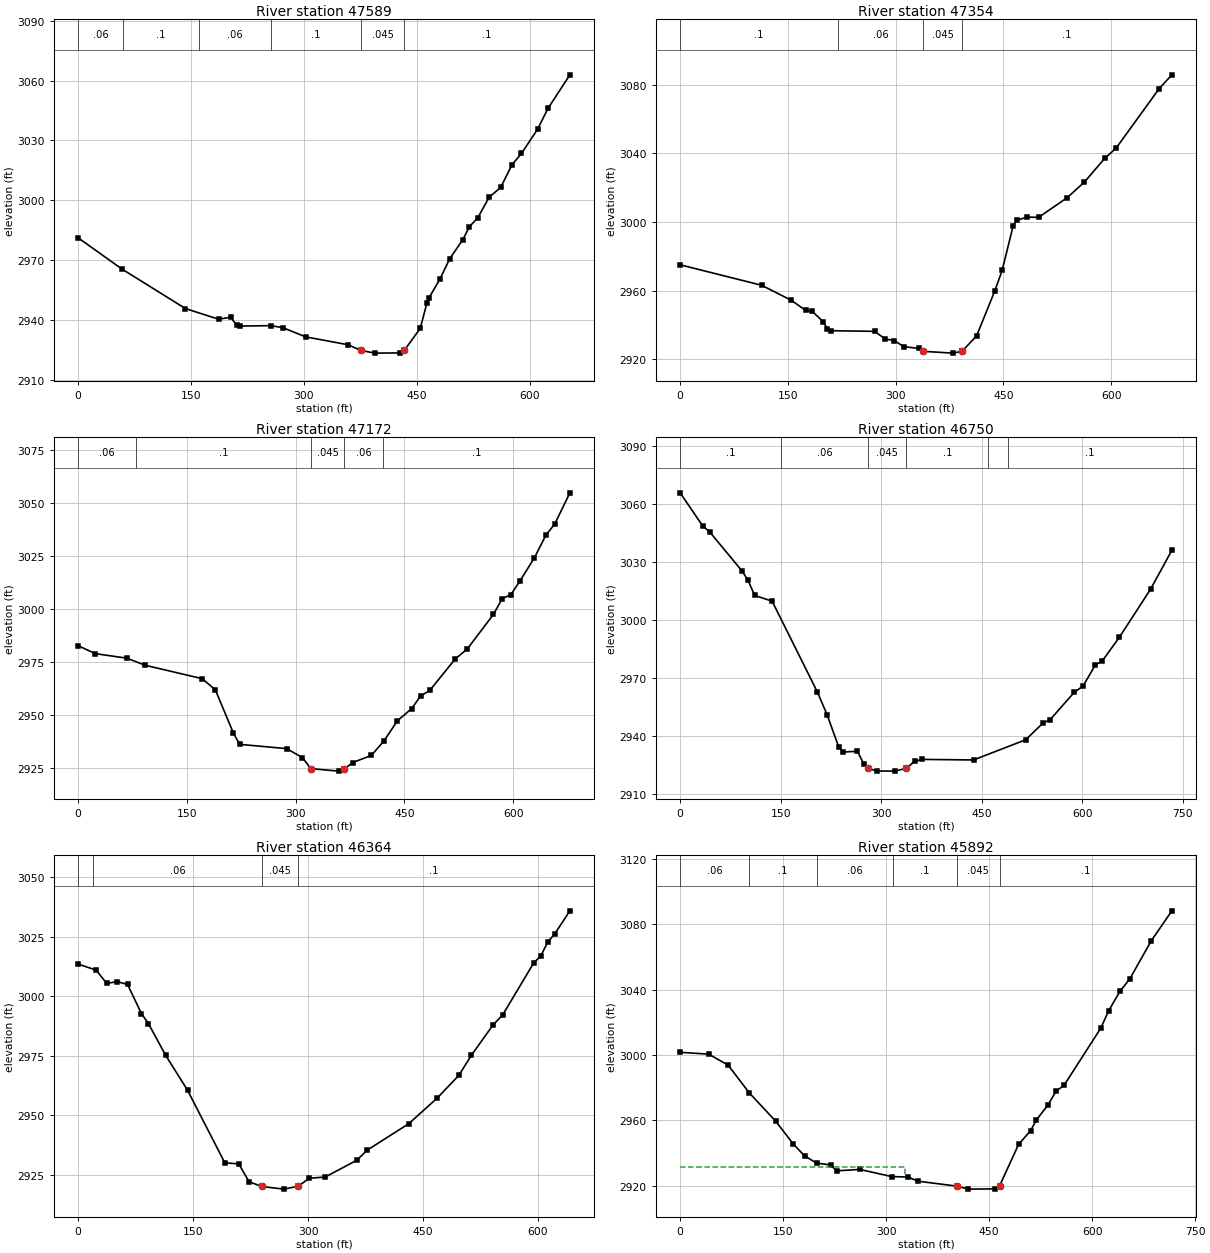
Type RM Length L Ch R = 1 ,47589   ,223.2,234.5,245.5
XS GIS Cut Line= 3
2308766.61174589593938.8334433472308511.00912184593931.733370457
  2308145.355368593775.531766873
#Sta/Elev= 30
       0 2981.29    58.5 2965.59   142.5  2945.9   186.5 2940.57   202.5 2941.53
   210.5  2937.7   214.5 2937.13   255.7 2937.33   271.8 2936.37   302.3 2931.72
   358.8 2927.77   375.6 2924.93   394.6 2923.59   427.4  2923.7   433.5 2925.05
   454.5 2935.98   463.2 2948.46   465.8 2951.08   480.6 2960.56   493.7 2970.88
   511.1 2980.38   519.8 2986.84   531.1 2991.41   545.9 3001.51   561.5 3006.57
   576.3 3017.81     589  3023.5   610.3  3035.6   624.2 3046.03   653.3 3062.84
#Mann= 6 ,-1,0
       0     .06       0      60      .1       0     160     .06       0
   255.7      .1       0   375.6    .045       0   433.5      .1       0
Bank Sta=375.6,433.5
XS Rating Curve= 0 ,0
Exp/Cntr(USF)=0,0
Exp/Cntr=0.3,0.1

Type RM Length L Ch R = 1 ,47354   ,193.7,182.7,172
XS GIS Cut Line= 4
2308814.96369602593728.9769403232308620.40820443593772.020190674
2308384.53119251593587.7950791722308198.58435099 593582.62988913
#Sta/Elev= 30
       0 2975.01   113.5 2963.06   154.4 2954.37   174.9 2948.37   183.1 2948.09
   199.3 2941.74   204.6 2937.78   209.7 2936.53   270.6 2936.16   285.8 2931.66
   298.3 2930.78   311.2 2927.21   332.5 2926.19   338.2  2924.5   379.3 2923.44
   392.4  2924.5   392.4 2924.51   412.7 2933.47     438 2959.72   448.3 2971.76
   463.6 2997.76   468.6 3001.01   483.3  3002.9   498.9 3002.66   538.9 3014.21
   562.9 3023.34   590.9 3037.07     607 3043.15     667 3077.92   684.6 3085.92
#Mann= 4 ,-1,0
       0      .1       0  219.26     .06       0   338.2    .045       0
   392.4      .1       0
Bank Sta=338.2,392.4
XS Rating Curve= 0 ,0
Exp/Cntr(USF)=0,0
Exp/Cntr=0.3,0.1

Type RM Length L Ch R = 1 ,47172   ,469.1,421.9,380.7
XS GIS Cut Line= 3
2308897.96309436593642.4054001832308480.83381206593470.228632596
 2308255.4064978593495.078887712
#Sta/Elev= 30
       0 2982.55    23.6 2978.79    66.8 2976.68    92.8 2973.28     171 2966.99
   189.2 2961.73     214 2941.38   222.6 2935.98   287.5 2933.96   309.2 2929.76
   320.9  2924.5   359.7 2923.34   366.8 2924.27   378.4 2927.36   404.4 2930.76
   421.7  2937.6   440.3 2947.13     460 2952.86   472.1 2958.78   484.9 2961.44
   520.3 2976.41   536.4  2980.9   572.7 2997.33   584.7 3004.72   596.8 3006.69
   608.9  3012.9     629 3023.95   645.1 3034.76   657.2 3039.99   678.1  3054.7
#Mann= 5 ,-1,0
       0     .06       0      80      .1       0   320.9    .045       0
   366.8     .06       0     420      .1       0
Bank Sta=320.9,366.8
XS Rating Curve= 0 ,0
Exp/Cntr(USF)=0,0
Exp/Cntr=0.3,0.1

Type RM Length L Ch R = 1 ,46750   ,404.2,385.9,369.9
XS GIS Cut Line= 2
2308786.13694634592930.6230929432308219.90613335593397.452885472
#Sta/Elev= 30
       0 3065.61    33.6 3048.54      44 3045.44    92.1 3025.31     101 3020.57
   111.2 3012.53   137.3 3009.55     205 2962.44   219.2  2950.9   236.7 2934.11
     243  2931.5   264.6 2931.89   274.4 2925.13   280.7 2923.08   293.3 2921.71
   320.5 2921.62   337.3 2923.09   349.9 2926.63   361.2 2927.68   437.9  2927.4
   515.8 2937.86   541.7 2946.55   552.1 2948.21   588.4 2962.49   601.4 2965.66
   619.8 2976.66   629.8 2978.54   655.7 2990.96   702.4 3015.93   733.9 3035.93
#Mann= 6 ,-1,0
       0      .1       0     150     .06       0   280.7    .045       0
   337.3      .1       0     460     .06       0     490      .1       0
Bank Sta=280.7,337.3
XS Rating Curve= 0 ,0
Exp/Cntr(USF)=0,0
Exp/Cntr=0.3,0.1

Type RM Length L Ch R = 1 ,46364   ,461.2,472.1,482.9
XS GIS Cut Line= 2
2308335.28231781592712.2958515712308033.52921998593278.526664561
#Sta/Elev= 30
       0 3013.42    23.6 3010.88    37.3 3005.29    50.9 3006.07    64.5 3004.89
    82.6 2992.63    91.7 2988.47   114.3 2975.07   142.7 2960.51   191.4 2930.01
   209.5 2929.59   223.1 2922.06   239.5  2920.1   268.4 2918.98   287.3 2920.23
   301.6 2923.54   322.3 2924.05   363.4 2931.07   377.2 2935.35   431.3 2946.43
   467.9 2957.02   496.7 2966.72   513.2 2975.22   541.1 2987.78     554 2992.14
   594.3 3013.86   603.8 3016.96   612.9 3022.78     622 3026.19   641.6 3035.78
#Mann= 4 ,-1,0
       0      .1       0      20     .06       0   239.5    .045       0
   287.3      .1       0
Bank Sta=239.5,287.3
XS Rating Curve= 0 ,0
Exp/Cntr(USF)=0,0
Exp/Cntr=0.3,0.1

Type RM Length L Ch R = 1 ,45892   ,443.8,492.6,535.5
XS GIS Cut Line= 3
2308207.48100579592479.768464418 2307909.2779444592582.719521325
2307637.70015635592877.372546267
#Sta/Elev= 30
       0 3001.59    41.6 3000.46    69.8 2993.78   100.8  2976.7   139.2 2959.37
   164.6  2945.5   181.2 2938.18   198.7 2933.72   219.3  2932.6   227.8 2928.99
   261.7 2929.84   308.2 2925.46   332.1 2925.19     346 2922.67   402.9 2919.61
   419.9 2917.78   458.8 2917.93   465.2 2919.74   492.9 2945.16   510.5 2953.63
     519 2960.26     536 2969.49   547.3 2977.72   559.1 2981.33   612.6 3016.37
     624 3026.96   640.7 3039.01   654.9  3046.6   686.3 3070.01   716.2 3088.26
#Mann= 6 ,-1,0
       0     .06       0     100      .1       0     200     .06       0
     310      .1       0   402.9    .045       0   465.2      .1       0
#XS Ineff= 2 , 0
          327.54 2931.33
Permanent Ineff=
       F       F
Bank Sta=402.9,465.2
XS Rating Curve= 0 ,0
Exp/Cntr(USF)=0,0
Exp/Cntr=0.3,0.1

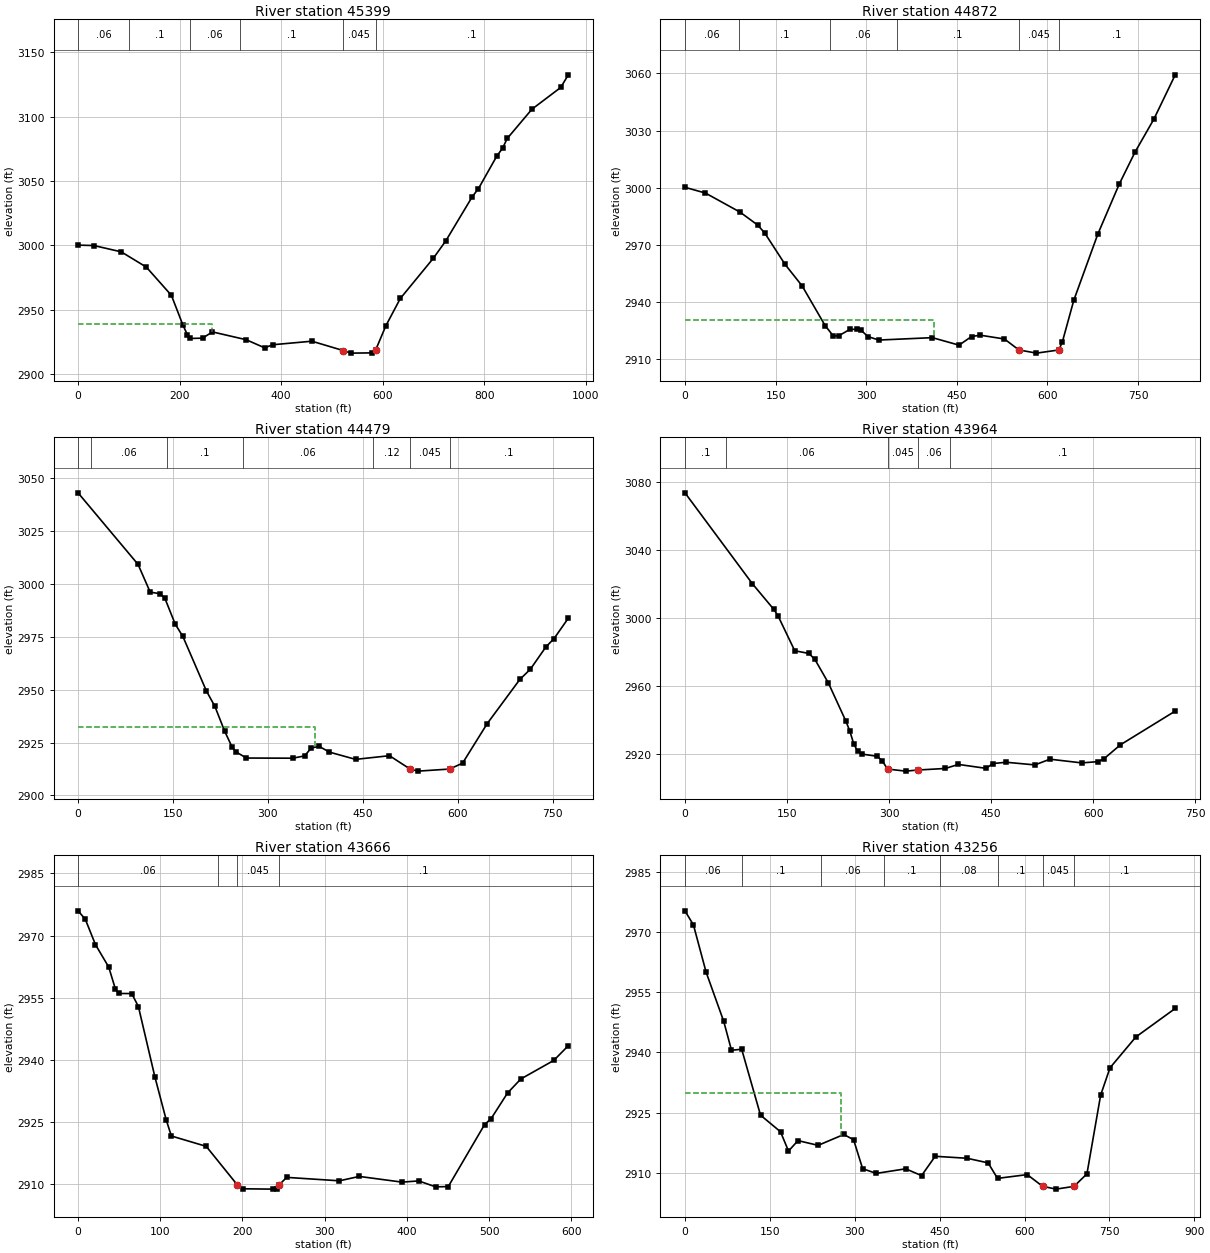
Type RM Length L Ch R = 1 ,45399   ,487,527.5,578.7
XS GIS Cut Line= 3
2308207.94459686592383.4044555642307958.97845463592256.116168377
2307281.37998178592147.596473786
#Sta/Elev= 30
       0 3000.14    31.2 2999.82    85.1 2994.91   134.5 2983.07   183.9 2961.11
   206.4 2938.21   215.5 2930.36   221.5  2927.6   245.2 2927.83   264.8 2932.68
   331.1 2926.63   367.5 2920.34   383.7 2922.71   460.7 2925.46   522.1 2918.23
   537.7 2916.19   578.2 2916.38   586.3 2918.59   606.5 2937.51   634.9 2958.67
   699.7  2989.8   724.6  3003.5   776.7  3037.8   788.8 3044.05   825.3 3069.55
   836.3 3075.44   845.5 3083.03   894.2 3105.79   950.9 3122.69   965.9 3132.52
#Mann= 6 ,-1,0
       0     .06       0     100      .1       0     220     .06       0
  319.62      .1       0   522.1    .045       0   586.3      .1       0
#XS Ineff= 2 , 0
          264.12 2939.02
Permanent Ineff=
       F       F
Bank Sta=522.1,586.3
XS Rating Curve= 0 ,0
Exp/Cntr=0.3,0.1

Type RM Length L Ch R = 1 ,44872   ,386.9,392.6,405.7
XS GIS Cut Line= 3
 2308255.4064978 592348.41711595  2308129.380204592098.139546571
2307903.95288973591617.109608262
#Sta/Elev= 30
       0 3000.25    33.9 2997.23    91.2 2987.22   120.1  2980.5   131.7 2976.42
   165.7 2959.79     194 2948.47     232 2927.67   245.5 2922.26   254.4 2922.31
   272.9 2925.71   284.9 2925.76   290.9 2925.39   302.9 2921.91   320.9  2920.1
   409.4 2921.36   453.6 2917.43   474.3 2921.96   488.9 2922.64   528.7 2920.66
   552.6 2914.92   581.7 2913.24   618.7 2914.89   624.7 2919.25   643.5 2940.95
   683.3 2975.71   718.6 3001.85   745.1 3018.87     776 3035.99   811.4 3059.27
#Mann= 6 ,-1,0
       0     .06       0      90      .1       0     240     .06       0
  350.22      .1       0   552.6    .045       0   618.7      .1       0
#XS Ineff= 2 , 0
          411.96 2930.44
Permanent Ineff=
       F       F
Bank Sta=552.6,618.7
XS Rating Curve= 0 ,0
Exp/Cntr(USF)=0,0
Exp/Cntr=0.3,0.1

Type RM Length L Ch R = 1 ,44479   ,542.1,514.6,488.7
XS GIS Cut Line= 3
 2308649.4605432 592250.791113712308438.23337472  591950.8130341
2308338.83235426591554.983970473
#Sta/Elev= 30
       0 3043.13    94.9 3009.25     114 2996.16   129.2 2995.41     137 2993.42
   153.6 2981.02   165.7 2975.17     203 2949.32   216.3 2942.11   231.7 2930.38
   243.2 2923.04   249.4 2920.63   266.1 2917.66   339.5 2917.59   358.1 2918.67
   368.6  2922.4   380.9 2923.21   397.4 2920.46   438.7 2917.03   492.3 2918.77
   525.3 2912.37   537.7 2911.47   587.2 2912.45   607.8 2915.23   646.8 2933.96
   698.5  2954.9     715 2959.68   739.7 2970.29   752.3 2974.11     775 2983.84
#Mann= 7 ,-1,0
       0      .1       0      20     .06       0     140      .1       0
     260     .06       0  466.88     .12       0   525.3    .045       0
   587.2      .1       0
#XS Ineff= 2 , 0
          374.99 2932.36
Permanent Ineff=
       F       F
Bank Sta=525.3,587.2
XS Rating Curve= 0 ,0
Exp/Cntr(USF)=0,0
Exp/Cntr=0.3,0.1

Type RM Length L Ch R = 1 ,43964   ,319,298.4,276.2
XS GIS Cut Line= 2
2309126.94044507591776.8612482912308542.95944985591354.406911326
#Sta/Elev= 30
       0 3073.51    99.2 3019.99   130.7 3004.92   136.7 3001.24   161.4 2980.61
   182.2 2979.04   190.8 2975.67   210.9 2961.62   236.7 2939.11   242.4 2933.33
   248.1 2925.88   253.8 2921.54   259.6 2919.88   282.5 2918.54   289.8 2916.02
  297.85 2911.03   324.3 2909.81   342.6 2910.46   382.7 2911.38   402.1 2913.75
   442.8 2911.44   452.7 2914.28   472.4 2915.02   514.5 2913.47   536.6 2916.83
   583.3 2914.65   606.8 2915.37   615.6 2916.93   640.3 2925.31   720.8 2945.13
#Mann= 5 ,-1,0
       0      .1       0      60     .06       0  297.85    .045       0
   342.6     .06       0     390      .1       0
Bank Sta=297.85,342.6
XS Rating Curve= 0 ,0
Exp/Cntr(USF)=0,0
Exp/Cntr=0.3,0.1

Type RM Length L Ch R = 1 ,43666   ,414.7,409.6,389.5
XS GIS Cut Line= 2
2309169.37023029591326.2323534732308574.52327245591285.280829151
#Sta/Elev= 30
       0 2975.97     8.8 2973.94    21.2 2967.79    37.3 2962.38    45.3 2957.14
    49.3 2955.99    65.3 2955.97    73.4 2952.82    93.4 2935.87   107.1 2925.52
   113.5 2921.54   155.9 2919.04   193.9 2909.68   200.9 2908.78     237  2908.7
   241.8  2908.7  244.51 2909.74   253.8 2911.54   317.9 2910.71     342 2911.77
   394.1 2910.39   414.2 2910.69     435 2909.25   450.3 2909.32   494.4 2924.29
   502.4 2925.74   522.4 2931.94   538.5 2935.32   578.6 2939.81   596.3 2943.37
#Mann= 4 ,-1,0
       0     .06       0     170      .1       0   193.9    .045       0
  244.51      .1       0
Bank Sta=193.9,244.51
XS Rating Curve= 0 ,0
Exp/Cntr(USF)=0,0
Exp/Cntr=0.3,0.1

Type RM Length L Ch R = 1 ,43256   ,138,129.3,121.2
XS GIS Cut Line= 4
2309270.92251188591215.2400261822309062.66094568591011.481412774
2308861.15380867591000.2240308182308500.91758607591097.037515641
#Sta/Elev= 30
       0 2975.31      15 2971.78    37.3 2960.03    68.5 2947.73    82.2 2940.53
   100.2 2940.78   133.5 2924.34   168.8  2920.2   182.9 2915.39   199.7 2917.99
   235.3 2916.81   280.6 2919.52   297.9 2918.22   313.9 2910.99   337.9 2909.81
     390 2910.96     418 2909.26   442.1 2914.08   498.3 2913.59   535.6 2912.44
   552.2 2908.57   604.7 2909.51   631.9 2906.59   655.7 2905.89   687.4 2906.58
   710.2  2909.7   734.4 2929.33     751 2936.16   796.6 2943.84   866.2 2950.96
#Mann= 8 ,-1,0
       0     .06       0     100      .1       0     240     .06       0
  351.36      .1       0  451.36     .08       0  553.18      .1       0
   631.9    .045       0   687.4      .1       0
#XS Ineff= 2 , 0
          275.75 2929.86
Permanent Ineff=
       F       F
Bank Sta=631.9,687.4
XS Rating Curve= 0 ,0
Exp/Cntr(USF)=0,0
Exp/Cntr=0.3,0.1

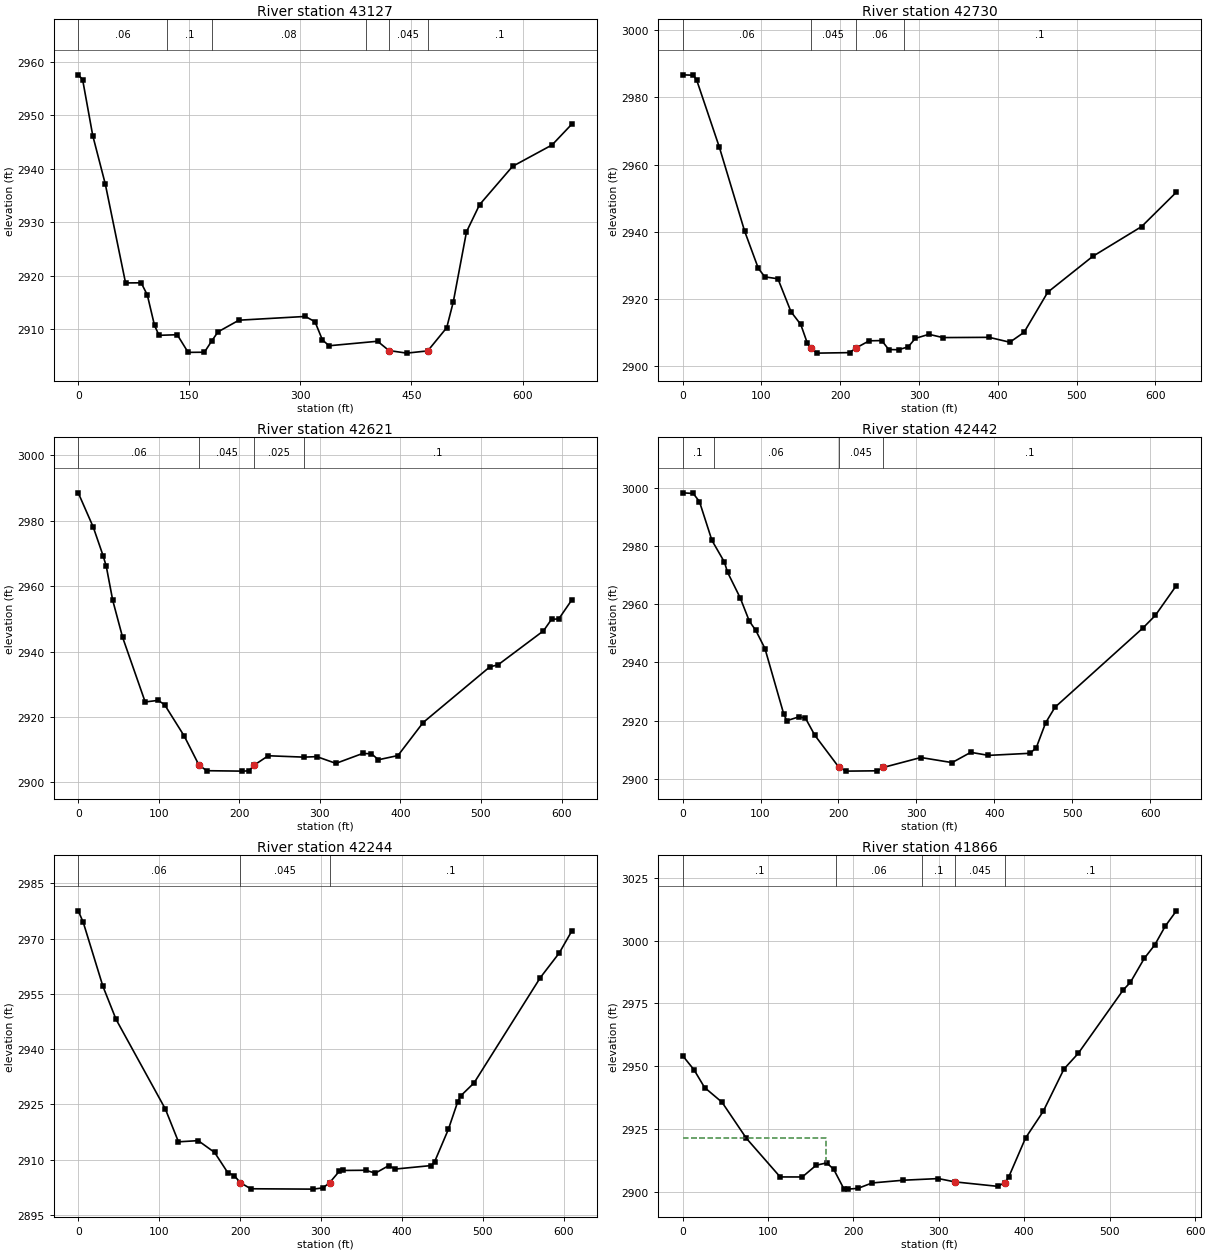
Type RM Length L Ch R = 1 ,43127   ,429,396.9,352.5
XS GIS Cut Line= 3
2308979.35631921590628.7304262612308777.84918219590862.883970951
2308455.88805824591019.361580143
#Sta/Elev= 30
       0  2957.6     5.9 2956.72    19.6 2946.24    36.6 2937.14    63.9 2918.68
      85  2918.7    93.3 2916.42     103 2910.73   109.1 2908.88   133.7 2908.99
   148.4 2905.69   170.4 2905.72     180 2907.77   188.8 2909.53     217 2911.71
   306.7 2912.41   319.7 2911.42   329.8    2908   338.8 2906.93   404.2 2907.77
   419.6 2906.03   443.6 2905.55     472 2905.97   497.6 2910.31   506.5 2915.15
   524.3 2928.24     542 2933.32   586.5 2940.48   639.9 2944.49   666.9 2948.43
#Mann= 6 ,-1,0
       0     .06       0     120      .1       0     180     .08       0
  388.92      .1       0   419.6    .045       0     472      .1       0
Bank Sta=419.6,472
XS Rating Curve= 0 ,0
Exp/Cntr(USF)=0,0
Exp/Cntr=0.3,0.1

Type RM Length L Ch R = 1 ,42730   ,115.7,109.6,103.1
XS GIS Cut Line= 4
2308610.07782435590395.7076331532308585.97360415590493.846243953
2308537.76516376590678.0713554542308394.86157259590981.095837925
#Sta/Elev= 30
       0 2986.65    13.9 2986.53      18 2985.06    46.8 2965.08    78.8 2940.19
    96.2 2929.12   104.5 2926.62     121 2926.06   137.6 2916.26     150 2912.48
   158.3 2906.95   162.4 2905.47   170.7 2903.97     212 2904.12     220 2905.49
   236.8 2907.63   252.7  2907.7   261.6 2905.04     274 2904.97   286.4 2905.85
   295.2 2908.34   312.6 2909.56   330.3 2908.59     389 2908.66   415.2 2907.21
   433.3 2910.16   463.3 2922.07   520.3  2932.7   582.4 2941.57   626.5 2951.79
#Mann= 4 ,-1,0
       0     .06       0   162.4    .045       0     220     .06       0
  281.06      .1       0
Bank Sta=162.4,220
XS Rating Curve= 0 ,0
Exp/Cntr(USF)=0,0
Exp/Cntr=0.3,0.1

Type RM Length L Ch R = 1 ,42621   ,183,178.8,173
XS GIS Cut Line= 3
2308473.73373917590390.5720164862308429.35828361590811.251335228
 2308326.4072267590971.002975257
#Sta/Elev= 30
       0 2988.53    18.7 2978.01    30.8 2969.35    34.8 2966.07    42.8 2955.68
    55.1 2944.34    83.1 2924.59    99.2 2925.07   107.2 2923.76   131.6 2914.16
  149.77 2905.33   159.5 2903.57   203.5 2903.44   211.8 2903.52   218.5 2905.29
   235.9 2908.14     280 2907.72   296.2 2907.87   319.9 2905.81   353.1 2908.84
     364 2908.75   372.7 2906.92   396.9  2908.2   428.2  2918.3     511 2935.32
   521.2 2935.94   577.6 2946.34   587.6 2949.85   596.6 2949.99   613.1 2955.91
#Mann= 4 ,-1,0
       0     .06       0  149.77    .045       0   218.5    .025       0
     280      .1       0
Bank Sta=149.77,218.5
XS Rating Curve= 0 ,0
Exp/Cntr(USF)=0,0
Exp/Cntr=0.3,0.1

Type RM Length L Ch R = 1 ,42442   ,208,197.9,191.7
XS GIS Cut Line= 3
2308276.06220162590335.4470826622308277.78393164590814.088026563
2308222.68857119590958.713347742
#Sta/Elev= 30
       0 2998.25    13.7 2998.03    21.7 2995.24    37.7 2981.91    53.7 2974.46
    57.7 2970.98    73.9  2962.2    85.7 2954.14      94 2950.96   105.7 2944.75
   129.7 2922.33   133.7 2919.94   149.3 2921.28   157.7 2920.79   169.7 2914.93
  200.35 2904.01   209.7 2902.62   249.7 2902.73   257.7  2903.9   305.7  2907.3
   345.7 2905.55   369.7 2909.08   392.4 2908.03   445.7 2908.75   453.7 2910.68
   465.7 2919.22   477.7 2924.57   590.8 2951.88   606.3  2956.1   633.4  2966.4
#Mann= 4 ,-1,0
       0      .1       0      40     .06       0  200.35    .045       0
   257.7      .1       0
Bank Sta=200.35,257.7
XS Rating Curve= 0 ,0
Exp/Cntr(USF)=0,0
Exp/Cntr=0.3,0.1

Type RM Length L Ch R = 1 ,42244   ,362.3,378.2,396.9
XS GIS Cut Line= 3
2308037.07925642590339.0964880322308116.95507644590798.826207671
2308093.87983955590940.827665474
#Sta/Elev= 30
       0 2977.56     6.2 2974.43    30.5 2957.08    46.8 2948.08   107.7 2923.76
   123.9 2914.86   148.3 2915.18   168.6 2911.97   184.8 2906.51   192.9  2905.7
   200.2  2903.8   213.2 2902.12   290.4 2902.02   302.5 2902.36   310.7 2903.75
   322.8 2906.89   326.9 2907.09   355.3 2907.14   367.3 2906.36   383.7 2908.38
     392 2907.47   436.5 2908.42   440.6 2909.48   457.6 2918.27     469 2925.66
   472.8 2927.33   489.3 2930.85   571.2 2959.42   594.6 2966.11   610.5 2972.22
#Mann= 3 ,-1,0
       0     .06       0   200.2    .045       0   310.7      .1       0
Bank Sta=200.2,310.7
XS Rating Curve= 0 ,0
Exp/Cntr(USF)=0,0
Exp/Cntr=0.3,0.1

Type RM Length L Ch R = 1 ,41866   ,244,251.1,261.7
XS GIS Cut Line= 2
 2307778.0606534590295.9453241532307660.63583061590861.955076866
#Sta/Elev= 30
       0 2954.22    13.5 2948.51    25.8 2941.49    46.2 2935.63    74.8 2921.23
   114.3 2905.88   140.2 2905.87   156.5 2910.56   168.8 2911.47   176.9 2908.96
   188.7 2901.25   193.3 2901.03   205.3 2901.33   221.9 2903.49   258.6 2904.58
   299.5 2905.23   318.7 2903.92   368.9 2902.14   377.1  2903.6   381.6 2905.67
   401.6 2921.43   422.2 2931.98   446.5 2948.85   463.1 2955.03     516 2980.38
   524.2 2983.32   540.5 2992.89   552.8 2998.26     565 3005.69   578.1 3011.83
#Mann= 5 ,-1,0
       0      .1       0     180     .06       0     280      .1       0
   318.7    .045       0   377.1      .1       0
#XS Ineff= 2 , 0
          168.34 2921.41
Permanent Ineff=
       F       F
Bank Sta=318.7,377.1
XS Rating Curve= 0 ,0
Exp/Cntr=0.3,0.1