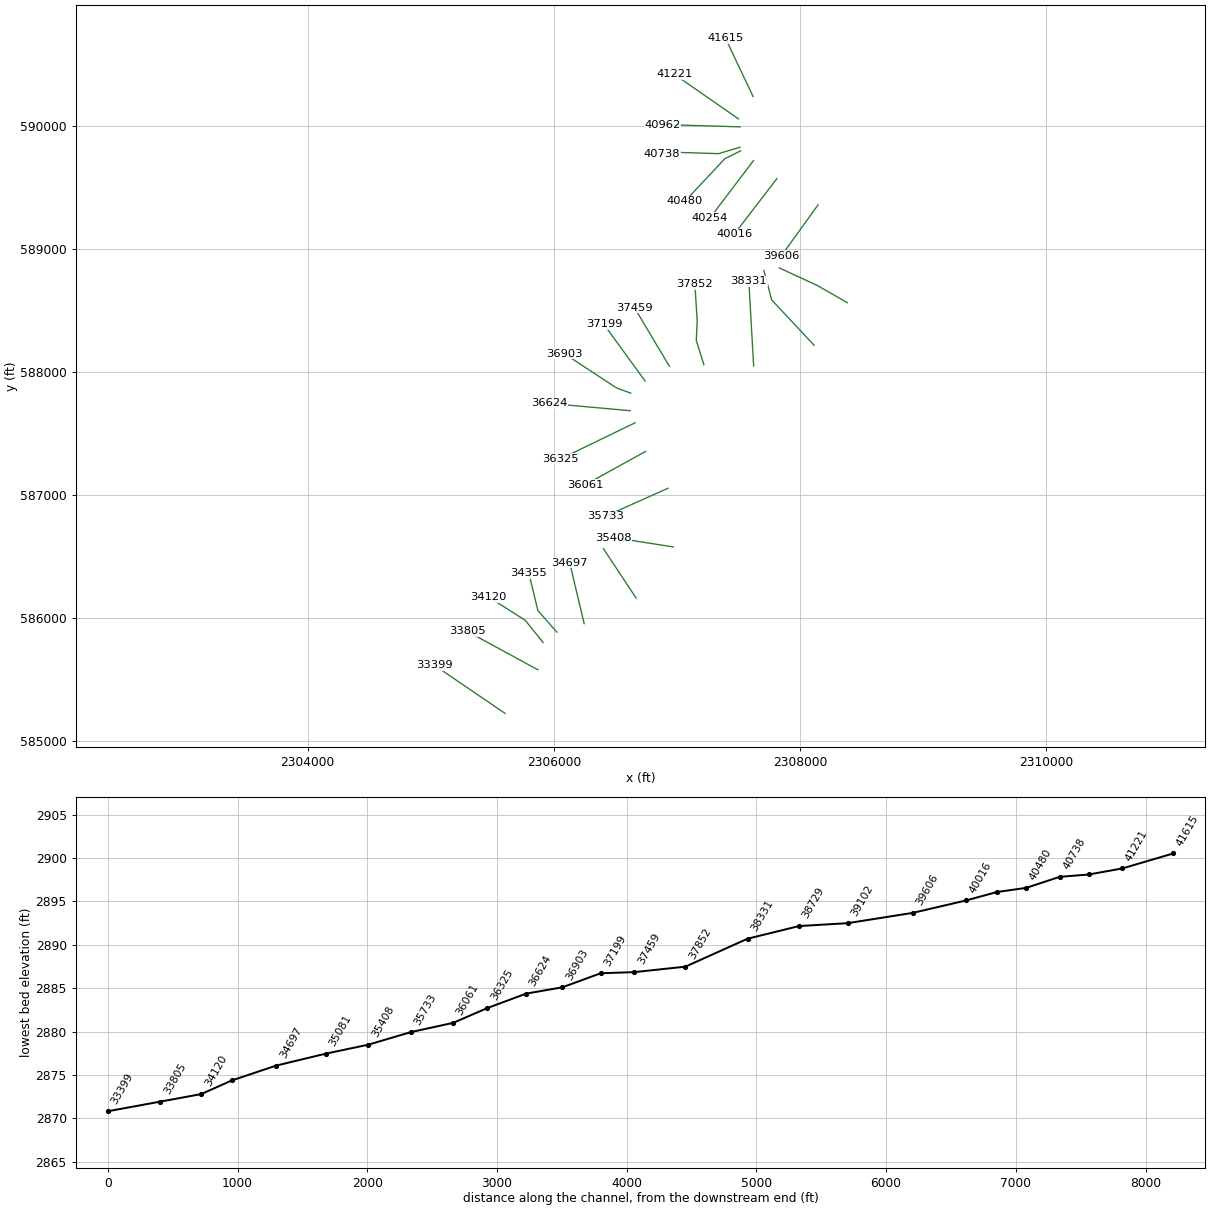
HEC-RAS study WFGRNBRRRV.prj: WFGRNBRRRV

--- WFGRNBRRRV.g01 (geometry) --- (continued)

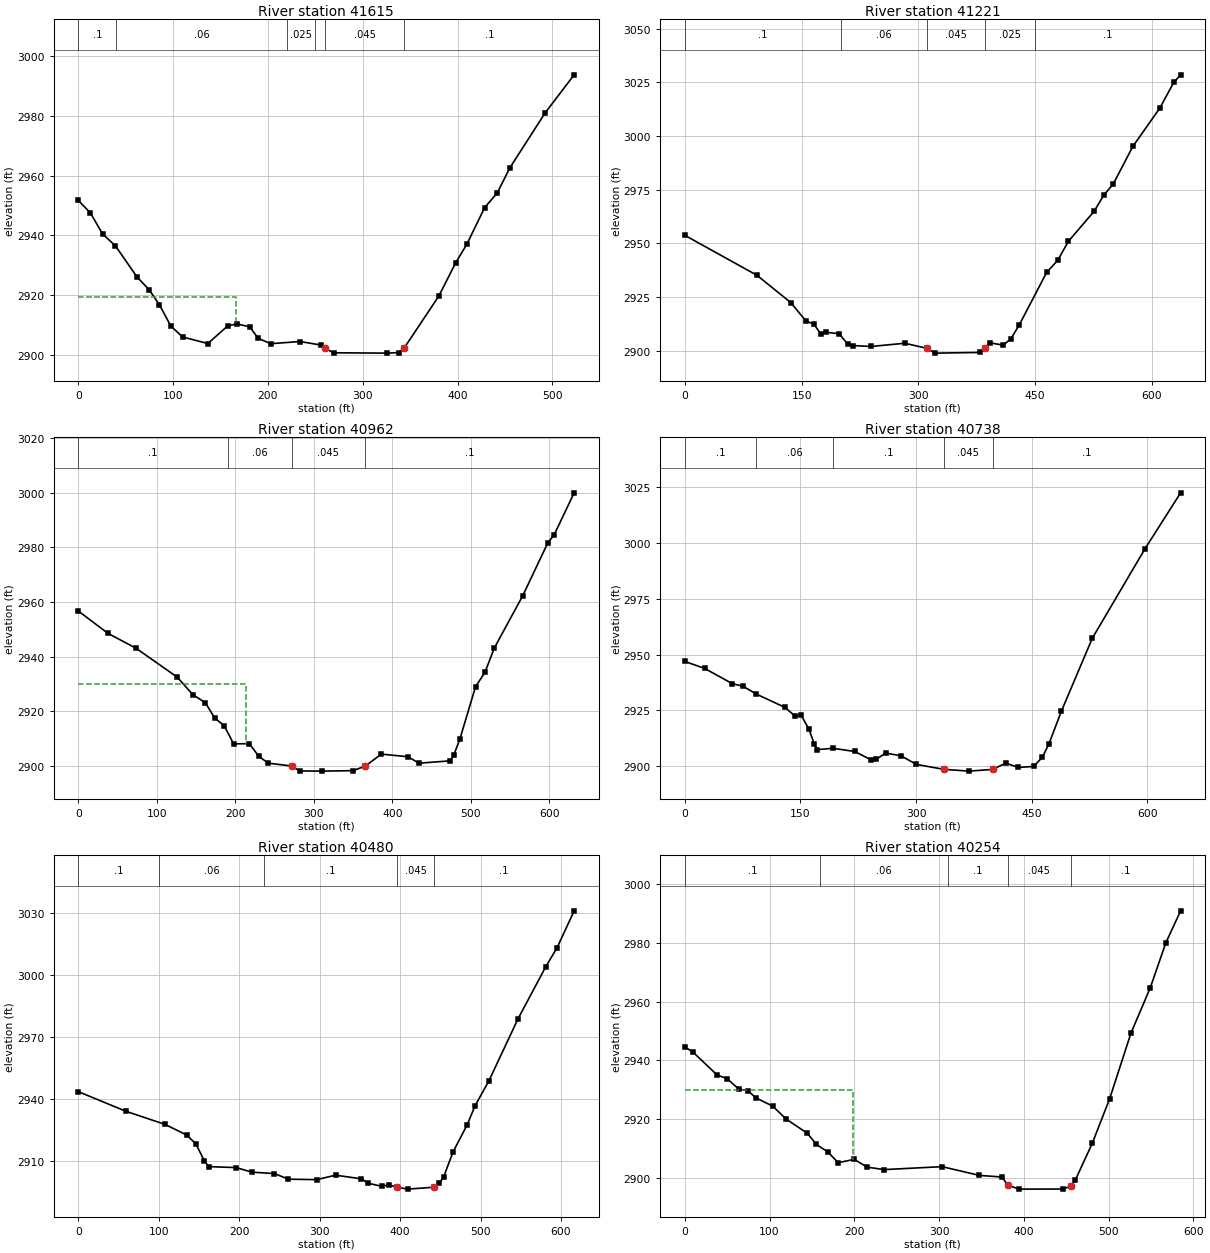
Type RM Length L Ch R = 1 ,41615   ,355.6,393.7,414.8
XS GIS Cut Line= 2
2307618.70178131590241.715970813 2307395.1006058590714.539289871
#Sta/Elev= 30
       0 2951.67    12.7 2947.52    25.5  2940.5    39.2 2936.43      62    2926
    74.6 2921.83    85.6 2916.69    97.6 2909.59     110 2905.95   136.6 2903.75
   157.7  2909.7   167.5 2910.32   180.8 2909.33   189.7 2905.51   202.9  2903.7
   233.9 2904.43     256 2903.24   259.8 2902.17   269.3 2900.65   325.9 2900.54
     338 2900.75     344 2902.38   380.2 2919.64     398 2930.75     410 2937.15
   428.6 2949.29   441.9 2954.21   455.1 2962.56   492.4 2981.01     523 2993.75
#Mann= 6 ,-1,0
       0      .1       0      40     .06       0     220    .025       0
     250      .1       0   259.8    .045       0     344      .1       0
#XS Ineff= 2 , 0
          165.97 2919.22
Permanent Ineff=
       F       F
Bank Sta=259.8,344
XS Rating Curve= 0 ,0
Exp/Cntr(USF)=0,0
Exp/Cntr=0.3,0.1

Type RM Length L Ch R = 1 ,41221   ,227.7,259.1,288.7
XS GIS Cut Line= 2
2307499.91365682590060.0400157072306977.01299116590423.391925919
#Sta/Elev= 30
       0  2953.7    92.6 2935.09   136.1 2922.36   155.8 2913.69   165.3 2912.46
     175 2907.66   181.7  2908.5   198.3 2907.85   209.1 2902.98   216.2 2902.33
   239.2 2901.91   282.4 2903.41   310.4  2901.1   321.2 2898.81   379.6 2899.13
   385.7 2901.11   391.5 2903.61   408.7 2902.57   418.6 2905.39   429.6 2912.03
   464.6 2936.38   478.7 2941.99   492.7 2950.95   525.7 2964.92     538 2972.41
   550.1 2977.55   575.4 2995.14   609.9 3012.91     628 3025.02   636.7 3028.47
#Mann= 5 ,-1,0
       0      .1       0     200     .06       0   310.4    .045       0
   385.7    .025       0     450      .1       0
Bank Sta=310.4,385.7
XS Rating Curve= 0 ,0
Exp/Cntr(USF)=0,0
Exp/Cntr=0.3,0.1

Type RM Length L Ch R = 1 ,40962   ,229.3,224.3,223.7
XS GIS Cut Line= 2
2307513.88873029589994.8230061812306882.68124524590013.456437474
#Sta/Elev= 30
       0 2956.69    37.7 2948.53    73.7 2943.03   125.8 2932.53   145.8 2926.11
   161.8 2923.12   173.8 2917.49   185.8 2914.72   197.8 2908.08   217.8 2908.16
   229.8 2903.54   241.8 2901.04   271.5 2899.98   281.8 2898.19   309.8 2898.11
   349.9 2898.28   365.4 2899.94   385.9 2904.34   419.9 2903.37   433.9 2901.01
   473.9 2901.88   478.2 2903.96   485.9  2909.8   505.9    2929   517.9 2934.26
   529.9 2943.21     566 2962.28     598 2981.67     606 2984.58   631.5 2999.94
#Mann= 4 ,-1,0
       0      .1       0     190     .06       0   271.5    .045       0
   365.4      .1       0
#XS Ineff= 2 , 0
          213.95 2930.05
Permanent Ineff=
       F       F
Bank Sta=271.5,365.4
XS Rating Curve= 0 ,0
Exp/Cntr(USF)=0,0
Exp/Cntr=0.3,0.1

Type RM Length L Ch R = 1 ,40738   ,225.6,258,293
XS GIS Cut Line= 4
2307512.72414083589829.4513034562307339.20031192589777.044777945
2307006.12772756589787.5260830472306878.02288742589777.044777945
#Sta/Elev= 30
       0 2946.93    25.6 2943.85    61.6    2937    75.8 2935.81    92.5 2932.37
   130.1 2926.34   142.6 2922.55     151  2922.8   161.1 2916.58   167.7 2910.18
   171.9 2907.46   192.1 2908.07   220.3 2906.63   242.1 2902.82   248.3 2903.11
   260.3 2905.94   280.3 2904.71   300.3 2900.85   335.6 2898.66   368.4 2897.84
   399.1  2898.6   416.4 2901.42   432.4  2899.5   452.4 2899.93   463.7 2904.05
   472.4 2910.18   488.4  2924.7   528.5 2957.35   596.7 2997.33     643 3022.43
#Mann= 5 ,-1,0
       0      .1       0    92.5     .06       0   192.1      .1       0
   335.6    .045       0   399.1      .1       0
Bank Sta=335.6,399.1
XS Rating Curve= 0 ,0
Exp/Cntr(USF)=0,0
Exp/Cntr=0.3,0.1

Type RM Length L Ch R = 1 ,40480   ,220.9,225.4,230.2
XS GIS Cut Line= 3
2307516.96190133589799.0377515972307390.18746052589736.543308945
2307065.21635873589390.145541103
#Sta/Elev= 30
       0 2943.73    58.9 2934.27   107.9 2927.86   134.7 2922.73     146  2918.5
   156.5 2910.41   161.8 2907.46   196.1 2906.99   215.9 2904.77   243.7  2904.1
   261.2 2901.37   296.3 2901.16   319.7 2903.31   351.7 2901.57   360.6  2899.4
   377.2 2897.92   385.7 2898.65   395.7 2897.58   409.2 2896.57   442.4  2897.5
   448.3 2899.34   454.1  2902.5   465.8  2914.6   483.4 2927.73   493.2 2936.98
   510.2 2948.85   546.3 2978.79   580.9 3004.08   595.1 3013.38   616.3  3031.2
#Mann= 5 ,-1,0
       0      .1       0     100     .06       0  231.34      .1       0
   395.7    .045       0   442.4      .1       0
Bank Sta=395.7,442.4
XS Rating Curve= 0 ,0
Exp/Cntr(USF)=0,0
Exp/Cntr=0.3,0.1

Type RM Length L Ch R = 1 ,40254   ,238.3,238.4,237.6
XS GIS Cut Line= 2
2307622.30967609589720.4733094062307268.76968623589254.443322773
#Sta/Elev= 30
       0 2944.55     9.2 2942.95    38.1 2935.01    49.9 2933.76    63.8 2930.18
    74.4 2929.68    83.8 2927.23   103.8 2924.37   119.6 2919.97   144.7 2915.11
   155.2 2911.34     169 2908.74   180.9 2905.09   199.9 2906.25   215.1 2903.59
   235.1 2902.75   303.6 2903.75   347.7 2900.77   374.2 2900.22   380.8 2897.54
     394 2896.09     446 2896.12     456 2897.15   460.7 2899.15   480.7 2911.67
   501.2 2926.86   526.3 2949.21   549.2 2964.76   567.6 2980.12     585 2990.99
#Mann= 5 ,-1,0
       0      .1       0     160     .06       0     310      .1       0
   380.8    .045       0     456      .1       0
#XS Ineff= 2 , 0
          198.34 2929.76
Permanent Ineff=
       F       F
Bank Sta=380.8,456
XS Rating Curve= 0 ,0
Exp/Cntr(USF)=0,0
Exp/Cntr=0.3,0.1

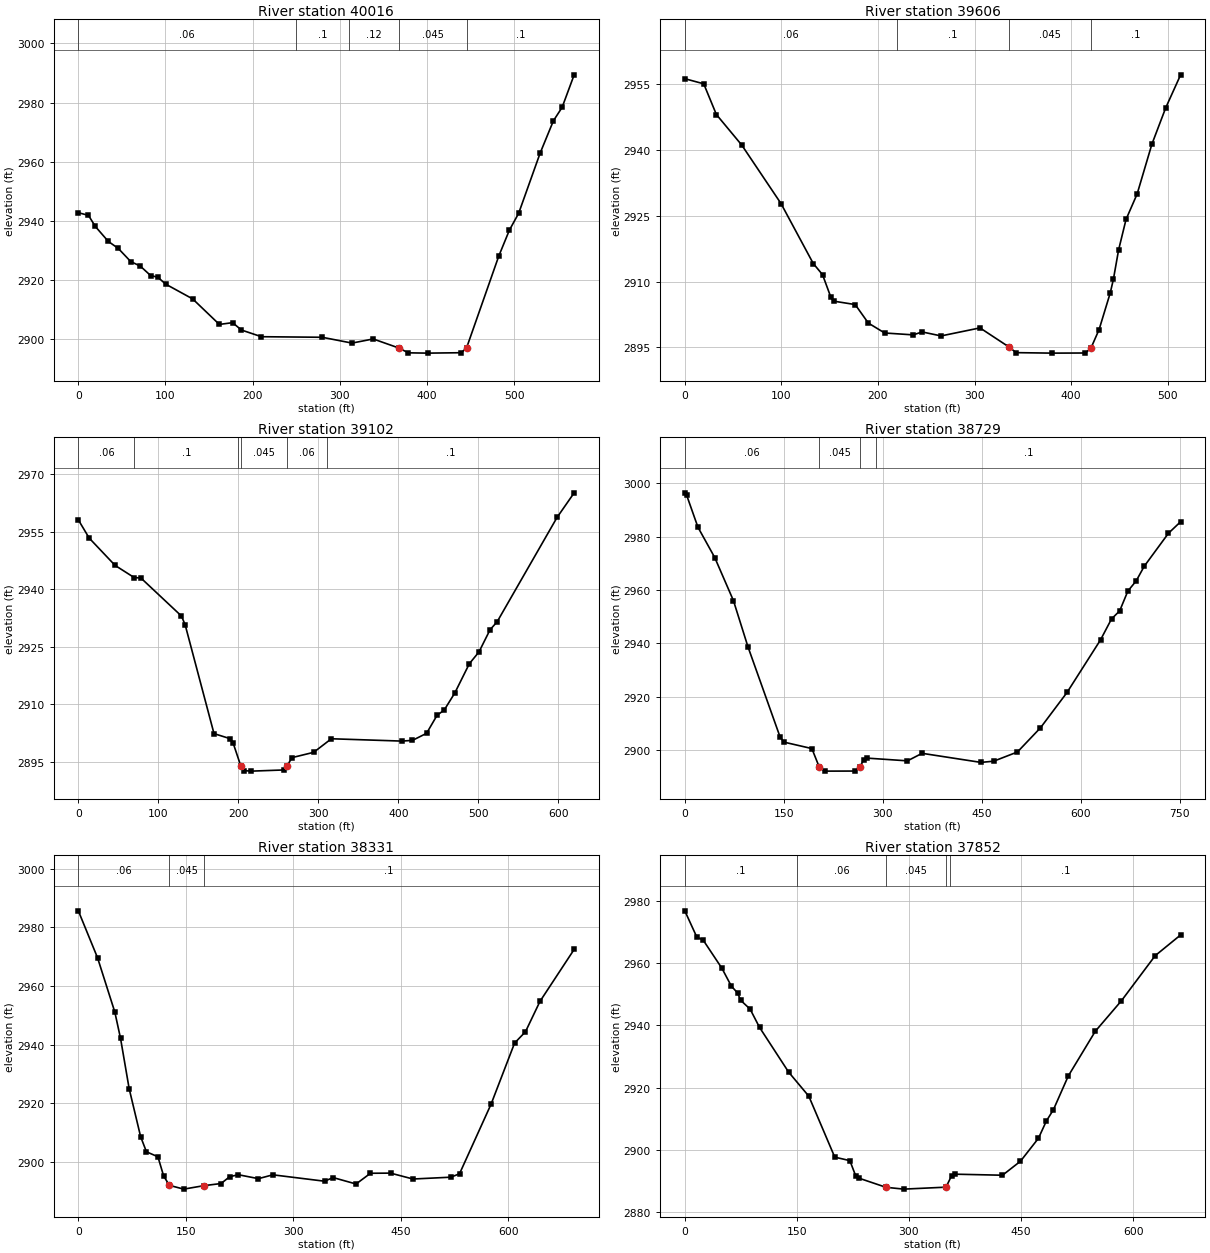
Type RM Length L Ch R = 1 ,40016   ,410.9,410,413
XS GIS Cut Line= 2
2307812.03693339589573.6034336832307465.79881097589122.179046222
#Sta/Elev= 30
       0 2942.68    11.6 2941.79    19.5 2938.02    34.4 2932.96    45.9 2930.56
    60.1 2926.14    71.1 2924.59    82.9 2921.41    91.3 2920.82   100.1 2918.51
   131.2 2913.48   161.8 2904.84     177 2905.44   187.1 2902.95   210.1 2900.68
   279.8 2900.49     314 2898.52   338.3 2899.92   367.8 2896.85   378.6 2895.22
   400.7 2895.12   439.6 2895.26   445.62897.021   482.3 2927.91   494.6 2936.79
   505.2 2942.47   529.8 2962.82   545.1 2973.82   555.1 2978.37   568.9 2989.38
#Mann= 5 ,-1,0
       0     .06       0     250      .1       0     310     .12       0
   367.8    .045       0   445.6      .1       0
Bank Sta=367.8,445.6
XS Rating Curve= 0 ,0
Exp/Cntr(USF)=0,0
Exp/Cntr=0.3,0.1

Type RM Length L Ch R = 1 ,39606   ,574.1,503.4,439.8
XS GIS Cut Line= 2
 2308147.3181532589361.0395230822307847.09902173588944.677223968
#Sta/Elev= 30
       0 2956.24    19.6 2955.07    32.7 2948.07      59  2941.1    99.6 2927.78
     133 2914.11   142.6 2911.57   151.1 2906.49     154 2905.54   176.4 2904.76
     190 2900.54   206.9 2898.28   236.5 2897.85   245.7 2898.52   265.3 2897.61
   305.6 2899.44   335.2 2895.15   343.1  2893.8   380.4 2893.69   414.8 2893.72
   420.5 2894.85   428.9 2899.07   440.5 2907.46   443.7 2910.52   449.1 2917.23
   456.8 2924.17   468.3 2929.98   483.5 2941.28   497.9 2949.62   513.3 2957.12
#Mann= 4 ,-1,0
       0     .06       0     220      .1       0   335.2    .045       0
   420.5      .1       0
Bank Sta=335.2,420.5
XS Rating Curve= 0 ,0
Exp/Cntr(USF)=0,0
Exp/Cntr=0.3,0.1

Type RM Length L Ch R = 1 ,39102   ,387.3,373.6,361.1
XS GIS Cut Line= 3
2308383.98724954588565.568393722 2308140.7628176588704.968087467
2307832.80911424588847.751581673
#Sta/Elev= 30
       0 2958.09    13.6 2953.33    45.9 2946.21    69.9 2943.02    78.2 2942.92
   128.9 2932.99   133.5 2930.72   169.6 2902.29   190.1 2900.95   193.4  2899.9
   203.32893.717   207.3 2892.62   216.4  2892.5   257.5 2892.81   260.4 2893.73
   267.2 2896.03   294.2 2897.41   316.3 2900.95   404.5 2900.34   417.7 2900.53
   435.3 2902.37   448.5  2907.1   457.3 2908.42   470.6  2912.9   488.8 2920.55
   500.8 2923.61   514.7 2929.42   523.5 2931.48   598.4 2958.72   619.8 2965.15
#Mann= 6 ,-1,0
       0     .06       0      70      .1       0     200     .06       0
   203.3    .045       0   260.4     .06       0  310.34      .1       0
Bank Sta=203.3,260.4
XS Rating Curve= 0 ,0
Exp/Cntr(USF)=0,0
Exp/Cntr=0.3,0.1

Type RM Length L Ch R = 1 ,38729   ,423.9,397.8,366.9
XS GIS Cut Line= 3
2308114.44744538  588219.33027132307770.40070348588587.482198938
2307706.85066835588826.342675799
#Sta/Elev= 30
       0 2996.42     2.9 2995.46    19.9 2983.54    45.4 2972.16    73.7 2956.03
    95.6  2938.8   144.4 2904.91   150.3 2903.03   192.5 2900.62   203.8 2893.61
   212.3 2892.17   257.6  2892.2   265.3 2893.69   270.8 2896.37   276.3 2897.04
   337.3 2896.02   359.5 2898.84   448.6 2895.44   467.9 2895.89   503.9 2899.34
   538.8  2908.4     579 2921.63   629.8 2941.35   646.4 2949.17   658.8 2952.21
   671.2 2959.64   683.7 2963.39     696 2968.92   732.7 2981.28   751.1  2985.6
#Mann= 4 ,-1,0
       0     .06       0   203.8    .045       0   265.3     .06       0
     290      .1       0
Bank Sta=203.8,265.3
XS Rating Curve= 0 ,0
Exp/Cntr(USF)=0,0
Exp/Cntr=0.3,0.1

Type RM Length L Ch R = 1 ,38331   ,481.5,479,483.5
XS GIS Cut Line= 2
2307623.57820853588050.3750522192307584.13335914588740.878835454
#Sta/Elev= 30
       0 2985.62    26.8 2969.61    50.9 2951.09    58.9 2942.08    70.9 2924.96
    86.9  2908.6      95 2903.44     111 2901.75     119 2895.19     127    2892
     147 2890.71   175.1 2891.89   199.1 2892.62   211.1 2894.95   223.2 2895.62
   251.2 2894.28   271.3 2895.59   343.4 2893.41   355.4 2894.65   387.4 2892.46
   407.5 2896.12   435.5 2896.17   466.8 2894.16   519.6 2894.78   531.7 2895.95
   575.7 2919.68   608.5 2940.52   623.7 2944.39   643.9 2954.73   691.6 2972.47
#Mann= 3 ,-1,0
       0     .06       0     127    .045       0   175.1      .1       0
Bank Sta=127,175.1
XS Rating Curve= 0 ,0
Exp/Cntr(USF)=0,0
Exp/Cntr=0.3,0.1

Type RM Length L Ch R = 1 ,37852   ,372.5,393.5,419.8
XS GIS Cut Line= 4
2307219.14304822588061.7961899132307157.49147075 588257.45925559
2307164.92327481588418.5456774452307146.01428654588715.147896728
#Sta/Elev= 30
       0 2976.79    16.1 2968.36    24.5 2967.43    49.7 2958.35    62.3 2952.63
    70.6 2950.45    74.8 2948.07    87.4 2945.26     100  2939.4     139 2925.03
     166  2917.3   200.7 2897.75   220.9 2896.64   228.9 2891.64   232.9 2891.02
   269.2 2888.08     293 2887.49   349.6 2888.12     357 2891.75     361 2892.29
   425.2 2891.95   449.2 2896.43   473.3  2903.8     484 2909.39   493.3 2912.95
   513.3 2923.82   549.4 2938.14   584.4 2947.94   629.6 2962.41   663.6 2969.05
#Mann= 5 ,-1,0
       0      .1       0     150     .06       0   269.2    .045       0
   349.6     .06       0  355.15      .1       0
Bank Sta=269.2,349.6
XS Rating Curve= 0 ,0
Exp/Cntr(USF)=0,0
Exp/Cntr=0.3,0.1

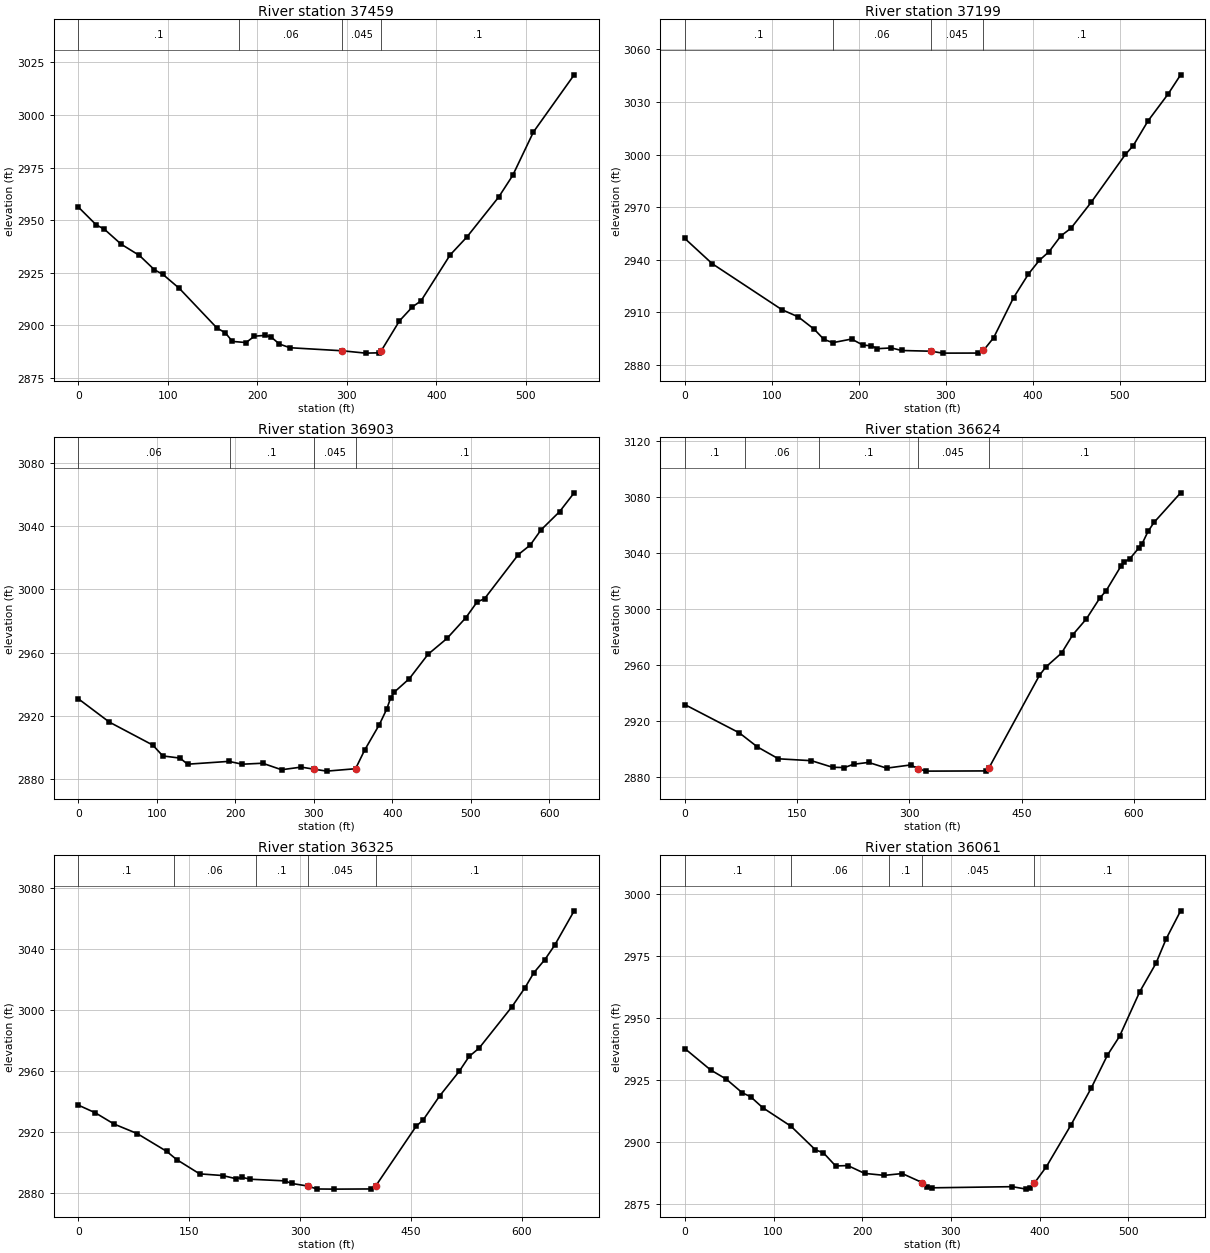
Type RM Length L Ch R = 1 ,37459   ,255.8,259.4,263.6
XS GIS Cut Line= 2
 2306939.0817882588048.0836351762306655.69835395588524.271323774
#Sta/Elev= 30
       0 2956.29    19.9 2947.85    29.2 2945.71    47.8 2938.65    68.3 2933.27
    85.1 2926.45    94.4 2924.31     113 2917.58   154.9  2898.8   164.2 2896.53
   172.2 2892.42   187.5 2891.89   196.8 2894.92     209  2895.3   215.4 2894.53
   224.7 2891.18   236.4 2889.43   295.1 2887.97     321 2886.86   335.6    2887
   338.5 2887.95   358.9  2902.2   373.3 2908.82     383 2911.72   415.5 2933.53
   434.2 2942.04   469.8 2961.06   485.4  2971.3   508.6 2991.97   554.1 3019.13
#Mann= 4 ,-1,0
       0      .1       0     180     .06       0   295.1    .045       0
   338.5      .1       0
Bank Sta=295.1,338.5
XS Rating Curve= 0 ,0
Exp/Cntr(USF)=0,0
Exp/Cntr=0.3,0.1

Type RM Length L Ch R = 1 ,37199   ,280.1,296.1,310.8
XS GIS Cut Line= 2
2306742.39556899587927.7427247432306407.25260338588388.402553929
#Sta/Elev= 30
       0 2952.13    31.5 2937.74   111.4 2911.56   130.4 2907.39   148.7 2900.35
   159.8 2894.59     170 2892.69   191.6 2894.76   204.6 2891.33   214.5 2890.88
   221.3 2889.26   237.4  2889.7   249.1 2888.23   283.2 2887.82   296.1 2886.73
   336.9 2886.77   343.1 2888.23   354.8 2895.47   377.7 2918.32   394.9 2931.89
   407.4 2939.68   418.5 2944.58   432.1  2953.6   443.6  2957.9   466.8 2972.67
   506.3 3000.09   515.2 3005.03   532.3 3019.22   555.3  3034.5   569.7 3045.46
#Mann= 4 ,-1,0
       0      .1       0     170     .06       0   283.2    .045       0
   343.1      .1       0
Bank Sta=283.2,343.1
XS Rating Curve= 0 ,0
Exp/Cntr(USF)=0,0
Exp/Cntr=0.3,0.1

Type RM Length L Ch R = 1 ,36903   ,255.2,279.1,303.6
XS GIS Cut Line= 3
2306625.27030045587829.9902267592306509.47767783587872.101228521
2306084.81539494588151.482812548
#Sta/Elev= 30
       0 2930.79    39.5 2916.07    94.8 2901.57   107.6  2894.7   129.6 2893.33
   139.1 2889.48   191.8 2891.27   208.7 2889.48   234.7  2890.1   258.8 2885.99
   283.8 2887.64   299.8 2886.37   316.3 2885.11   353.1 2886.63   364.6 2898.34
   383.3  2914.4   392.9  2924.4   397.7 2931.27   402.5 2935.04   421.6 2943.51
   445.4 2958.89   469.5 2968.89   493.4 2981.91   507.8 2991.87   517.4 2994.02
   560.5  3021.9   575.5 3027.83   589.2 3037.38     613    3049   631.5 3060.85
#Mann= 4 ,-1,0
       0     .06       0  193.21      .1       0   299.8    .045       0
   353.1      .1       0
Bank Sta=299.8,353.1
XS Rating Curve= 0 ,0
Exp/Cntr=0.3,0.1

Type RM Length L Ch R = 1 ,36624   ,265.8,298.9,332.6
XS GIS Cut Line= 2
2306620.76067028587687.0609038752305960.82664532 587746.58436495
#Sta/Elev= 30
       0 2931.87    72.9 2911.66      97 2901.66   125.1 2893.18   169.3 2891.82
   197.4 2887.13   213.4 2886.93   225.5 2889.28   245.6 2890.59   269.7 2886.51
   301.8 2888.79   311.7 2886.17   321.9 2884.38   402.2 2884.53   406.2 2886.42
     474 2952.78   482.5 2958.68   503.5 2968.62   518.7 2981.82   536.7 2993.03
   554.8 3008.02   562.9 3012.95   582.9  3030.7     587 3033.46     595 3036.08
   606.7 3043.59   611.1 3046.57   619.1 3055.48   627.1 3061.86   662.6 3082.94
#Mann= 5 ,-1,0
       0      .1       0      80     .06       0     180      .1       0
   311.7    .045       0   406.2      .1       0
Bank Sta=311.7,406.2
XS Rating Curve= 0 ,0
Exp/Cntr(USF)=0,0
Exp/Cntr=0.3,0.1

Type RM Length L Ch R = 1 ,36325   ,260.9,264.5,269.3
XS GIS Cut Line= 2
2306659.71396069587588.5541288732306056.36869955587295.981753969
#Sta/Elev= 30
       0 2937.69    23.1 2932.63    48.4 2925.28    79.5  2919.1   119.5 2907.43
   132.9 2902.09     164 2892.71   195.1 2891.62   212.9 2889.57   221.8 2890.38
   232.7  2889.2   279.6 2888.11   288.4 2886.44   310.3 2884.74   322.5 2882.82
   345.6 2882.72   395.1 2882.83   401.9 2884.62   456.9 2923.91   466.3 2927.98
   488.5 2943.63   515.2  2959.9   528.5 2969.58   541.8 2974.89     586 3001.84
   604.1 3014.58   615.9 3024.27   630.9 3032.93   644.1 3042.29   670.5 3064.84
#Mann= 5 ,-1,0
       0      .1       0     130     .06       0     240      .1       0
   310.3    .045       0   401.9      .1       0
Bank Sta=310.3,401.9
XS Rating Curve= 0 ,0
Exp/Cntr=0.3,0.1

Type RM Length L Ch R = 1 ,36061   ,333.2,327.1,317.3
XS GIS Cut Line= 2
2306744.98354556587355.7999031122306255.85597412587085.356351708
#Sta/Elev= 30
       0 2937.69      29 2929.08    46.7 2925.36    64.9 2919.81    74.1 2918.29
    87.8 2913.85   119.8 2906.33   147.2 2896.85   156.3 2895.63     170 2890.36
   183.8  2890.5   202.7 2887.35   224.9 2886.56   245.1 2887.29   267.4 2883.68
   273.3 2881.83   279.2 2881.54   369.1    2882   384.9 2881.01   389.4 2881.51
   394.1 2883.45   407.7 2890.13     435 2906.69     458 2921.66   476.4 2935.02
     490 2942.57   512.8 2960.57   531.1 2972.04   542.7 2981.97   558.9  2993.2
#Mann= 5 ,-1,0
       0      .1       0     120     .06       0     230      .1       0
   267.4    .045       0   394.1      .1       0
Bank Sta=267.4,394.1
XS Rating Curve= 0 ,0
Exp/Cntr(USF)=0,0
Exp/Cntr=0.3,0.1

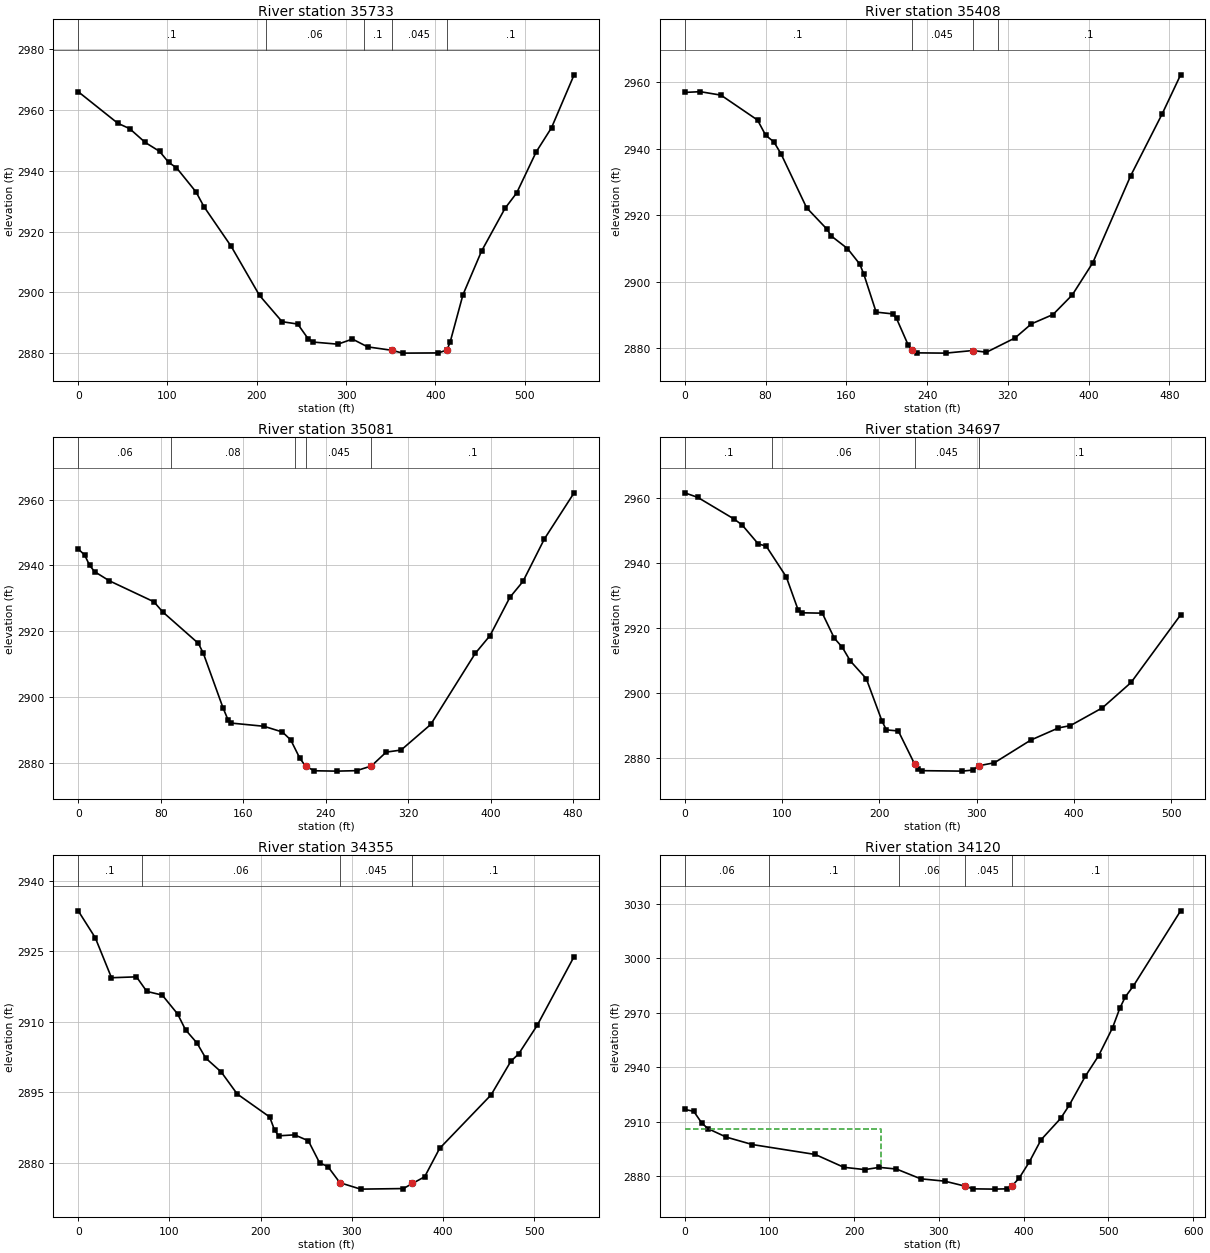
Type RM Length L Ch R = 1 ,35733   ,351.6,325.4,299.7
XS GIS Cut Line= 2
2306928.72988192587056.888609454 2306421.4864745586830.440659714
#Sta/Elev= 30
       0 2966.08    44.4 2955.67    57.6 2953.91    75.1 2949.35    91.1 2946.43
   101.4 2942.77   110.1 2941.02     132 2933.04   140.8 2928.23   171.4 2915.11
   203.1 2898.95   228.4  2890.3   245.9 2889.52   257.6 2884.66   263.4 2883.58
   290.9 2882.89   307.2 2884.57   324.2    2882     351 2880.89   363.6 2879.94
   403.6 2880.01   413.2    2881   416.8 2883.74     431 2899.17   451.8 2913.54
   478.1 2927.64   491.2 2932.73   513.1 2946.27   530.2  2954.2   555.5 2971.64
#Mann= 5 ,-1,0
       0      .1       0     210     .06       0     320      .1       0
     351    .045       0   413.2      .1       0
Bank Sta=351,413.2
XS Rating Curve= 0 ,0
Exp/Cntr(USF)=0,0
Exp/Cntr=0.3,0.1

Type RM Length L Ch R = 1 ,35408   ,362.1,327,285.8
XS GIS Cut Line= 2
 2306971.4314953586579.4069325732306486.18588872586655.752241342
#Sta/Elev= 30
       0 2956.91    15.4 2957.13    35.9 2956.09    72.1  2948.6    80.2 2944.01
    88.3 2942.03    95.4 2938.42   120.7 2922.23     141 2915.74     145 2913.76
   161.2 2909.95   173.4 2905.27   177.4 2902.23   189.6 2890.83   205.8 2890.31
   209.8 2888.92   221.3 2880.97   224.8 2879.45   230.1 2878.58   258.4  2878.5
   285.3 2879.28   298.9 2878.77   327.2 2883.07   343.4  2887.3   364.8 2890.11
   383.9 2896.01   404.2 2905.68   441.7 2931.83     473  2950.5   491.2  2962.2
#Mann= 4 ,-1,0
       0      .1       0   224.8    .045       0   285.3     .06       0
     310      .1       0
Bank Sta=224.8,285.3
XS Rating Curve= 0 ,0
Exp/Cntr(USF)=0,0
Exp/Cntr=0.3,0.1

Type RM Length L Ch R = 1 ,35081   ,400.2,383.7,366.8
XS GIS Cut Line= 2
2306668.63823679586164.0366933342306403.37063853586565.173061446
#Sta/Elev= 30
       0 2944.98     6.2 2943.16      11 2940.05    15.8  2938.1    30.1 2935.32
    73.4 2928.93      82 2925.84   116.5  2916.3   121.3 2913.31   140.4 2896.73
   145.2 2893.12   148.4 2892.07   180.1  2891.1     198 2889.36   206.1 2886.95
   214.8 2881.46   220.5 2878.95   228.9 2877.58   250.7 2877.47   269.9 2877.61
   284.3 2879.03   298.7 2883.25   313.1 2883.87   341.9 2891.66     385 2913.23
   399.4 2918.67   418.6 2930.27   431.3  2935.1   452.1 2948.03   480.9 2962.04
#Mann= 5 ,-1,0
       0     .06       0      90     .08       0     210     .06       0
   220.5    .045       0   284.3      .1       0
Bank Sta=220.5,284.3
XS Rating Curve= 0 ,0
Exp/Cntr(USF)=0,0
Exp/Cntr=0.3,0.1

Type RM Length L Ch R = 1 ,34697   ,341.7,342.1,342.6
XS GIS Cut Line= 2
2306246.79805613585955.7045795732306129.04512227586451.302092434
#Sta/Elev= 30
       0 2961.59    13.4 2960.19    50.9  2953.5    59.1 2951.67    75.5  2945.9
    83.7 2945.21   104.3 2935.77   116.6 2925.51   120.7 2924.73   141.3 2924.62
   153.6 2916.96   161.9 2914.11   170.1 2909.94   186.5 2904.49   202.7 2891.43
   207.1 2888.76   219.4 2888.43   236.3 2878.17     240 2876.61   244.1 2876.23
   285.2 2876.09   295.7 2876.41   302.4 2877.76   318.1 2878.66   355.5 2885.63
   383.9 2889.36   396.2 2890.08   429.1 2895.55   458.5 2903.32   509.4 2924.09
#Mann= 4 ,-1,0
       0      .1       0      90     .06       0   236.3    .045       0
   302.4      .1       0
Bank Sta=236.3,302.4
XS Rating Curve= 0 ,0
Exp/Cntr(USF)=0,0
Exp/Cntr=0.3,0.1

Type RM Length L Ch R = 1 ,34355   ,188.6,235.5,262.1
XS GIS Cut Line= 3
2306024.23207125585887.1232005092305870.24746542586063.105607164
 2305797.7841215 586364.60487739
#Sta/Elev= 30
       0 2933.65    18.7 2927.92    36.5  2919.4    63.9 2919.59    75.2 2916.49
    92.2  2915.7     109 2911.69   117.7 2908.31   130.3 2905.49   139.8  2902.3
   156.9 2899.32   174.4 2894.64     210 2889.75   215.3 2886.98   219.8 2885.73
   237.3 2885.94   252.4 2884.68   264.8 2879.96   273.8 2879.19     287 2875.75
   309.7 2874.38   356.7  2874.5   366.6 2875.59     380 2877.01   396.4 2883.05
   452.9 2894.46   474.6 2901.63     483 2903.15   503.4 2909.25   543.9 2923.91
#Mann= 4 ,-1,0
       0      .1       0      70     .06       0     287    .045       0
   366.6      .1       0
Bank Sta=287,366.6
XS Rating Curve= 0 ,0
Exp/Cntr(USF)=0,0
Exp/Cntr=0.3,0.1

Type RM Length L Ch R = 1 ,34120   ,311.4,315,315.8
XS GIS Cut Line= 3
 2305912.9490788585803.0139620342305766.72840268585984.172321826
2305469.11109731586173.094611324
#Sta/Elev= 30
       0 2916.67    10.6 2915.67    20.3 2909.05    27.7 2906.06      49 2901.45
    79.9 2897.34   154.1 2891.89   187.8 2884.83   212.6 2883.56   229.6 2884.79
   249.9 2883.87   278.5 2878.49   306.9  2877.2   330.6 2874.48   340.1 2872.97
   365.8 2872.81   380.3 2872.98   386.1 2874.45   394.8 2878.94   406.4 2887.51
   420.6 2900.01   443.7 2911.75   453.8 2918.98   472.7 2934.88   488.5 2946.26
   504.9  2961.6   513.6 2972.48   520.1 2978.74   529.6  2984.7   585.3 3026.03
#Mann= 5 ,-1,0
       0     .06       0     100      .1       0  252.81     .06       0
   330.6    .045       0   386.1      .1       0
#XS Ineff= 2 , 0
          232.23 2906.02
Permanent Ineff=
       F       F
Bank Sta=330.6,386.1
XS Rating Curve= 0 ,0
Exp/Cntr(USF)=0,0
Exp/Cntr=0.3,0.1

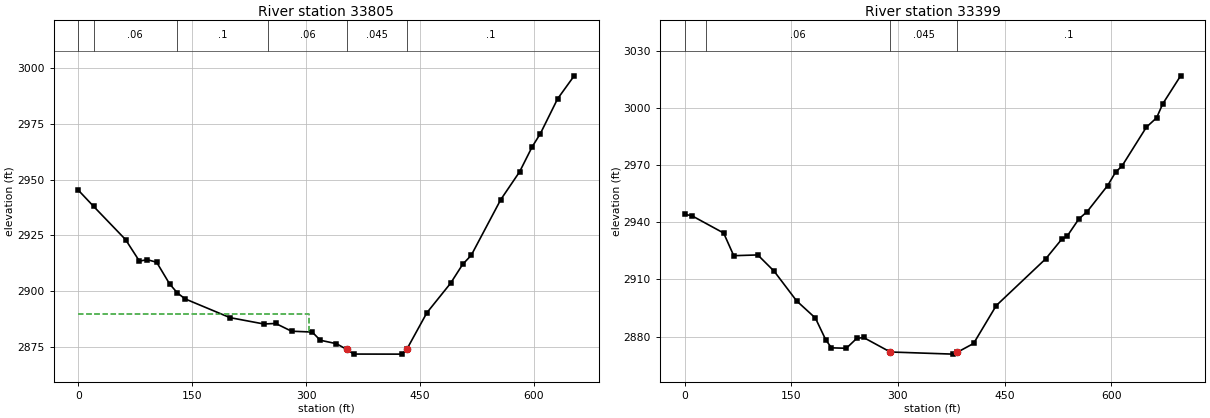
Type RM Length L Ch R = 1 ,33805   ,412.7,405.3,400.6
XS GIS Cut Line= 2
2305870.83284354585580.774515494 2305297.0774418585893.181878683
#Sta/Elev= 30
       0 2945.24      20 2938.05    62.2 2923.16    80.5 2913.52    90.7 2914.18
   103.2 2913.02   120.2 2903.36   130.6 2899.25   140.9 2896.61   199.8 2888.26
   244.4 2885.42   260.1 2885.65   280.9 2882.19   308.2 2881.81   318.7 2878.16
   340.1  2876.6   353.7 2874.03   362.8 2871.97   426.6 2871.94   432.8 2874.11
   459.3 2890.47   490.4  2903.6   506.5 2912.13   517.7 2916.14   556.6 2941.04
   581.4 2953.46   597.9  2964.6   608.8 2970.56   631.5 2986.11   653.3 2996.38
#Mann= 6 ,-1,0
       0      .1       0      20     .06       0     130      .1       0
     250     .06       0   353.7    .045       0   432.8      .1       0
#XS Ineff= 2 , 0
          303.27  2889.9
Permanent Ineff=
       F       F
Bank Sta=353.7,432.8
XS Rating Curve= 0 ,0
Exp/Cntr=0.3,0.1

Type RM Length L Ch R = 1 ,33399   ,417.4,435,440.3
XS GIS Cut Line= 2
2305604.09950308585226.3650671672305027.32482772585619.278074723
#Sta/Elev= 30
       0  2944.1     9.6 2943.51    54.7 2934.35    68.9 2922.47   102.7 2922.87
   125.8 2914.31   157.4 2898.76   183.8 2889.77   198.3 2878.41   206.4 2874.13
   227.4 2873.91   241.9 2879.06   251.6 2879.56   289.2 2871.95   377.4 2870.83
   383.8 2871.86   406.5 2876.43   438.4 2896.31   508.1 2920.87   530.8 2931.23
   537.9 2932.57   554.7 2941.78   566.3 2945.57   595.2 2959.28   606.5 2966.39
   615.2 2969.42   649.7  2989.9   664.1 2994.82   672.7 3002.12   697.9 3016.84
#Mann= 4 ,-1,0
       0      .1       0      30     .06       0   289.2    .045       0
   383.8      .1       0
Bank Sta=289.2,383.8
XS Rating Curve= 0 ,0
Exp/Cntr=0.3,0.1