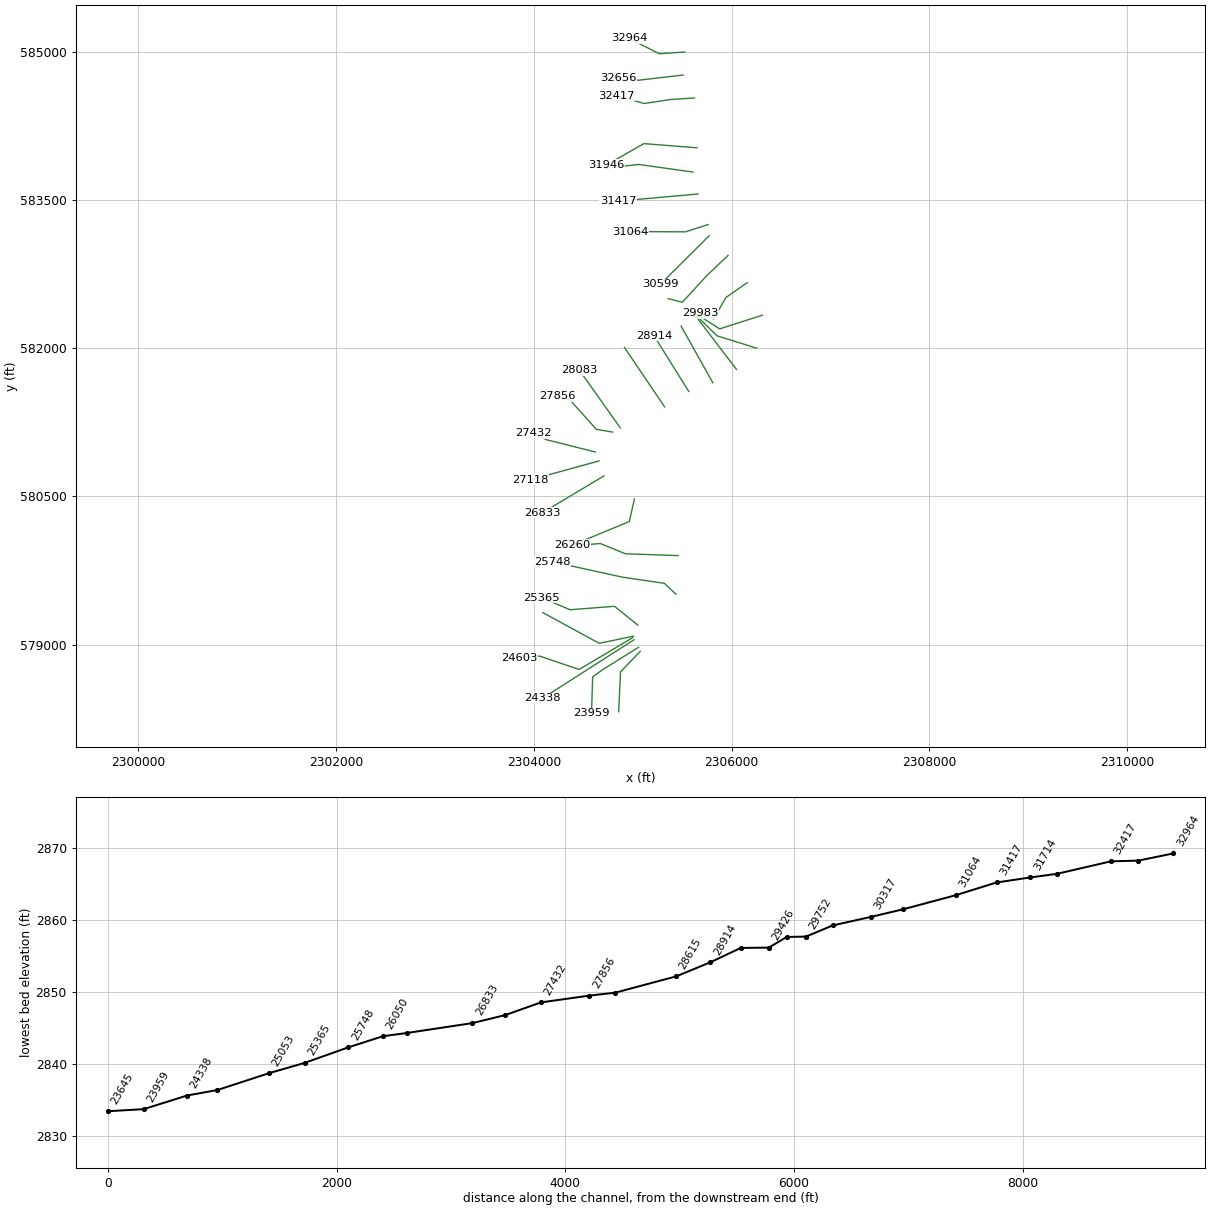
HEC-RAS study WFGRNBRRRV.prj: WFGRNBRRRV

--- WFGRNBRRRV.g01 (geometry) --- (continued)

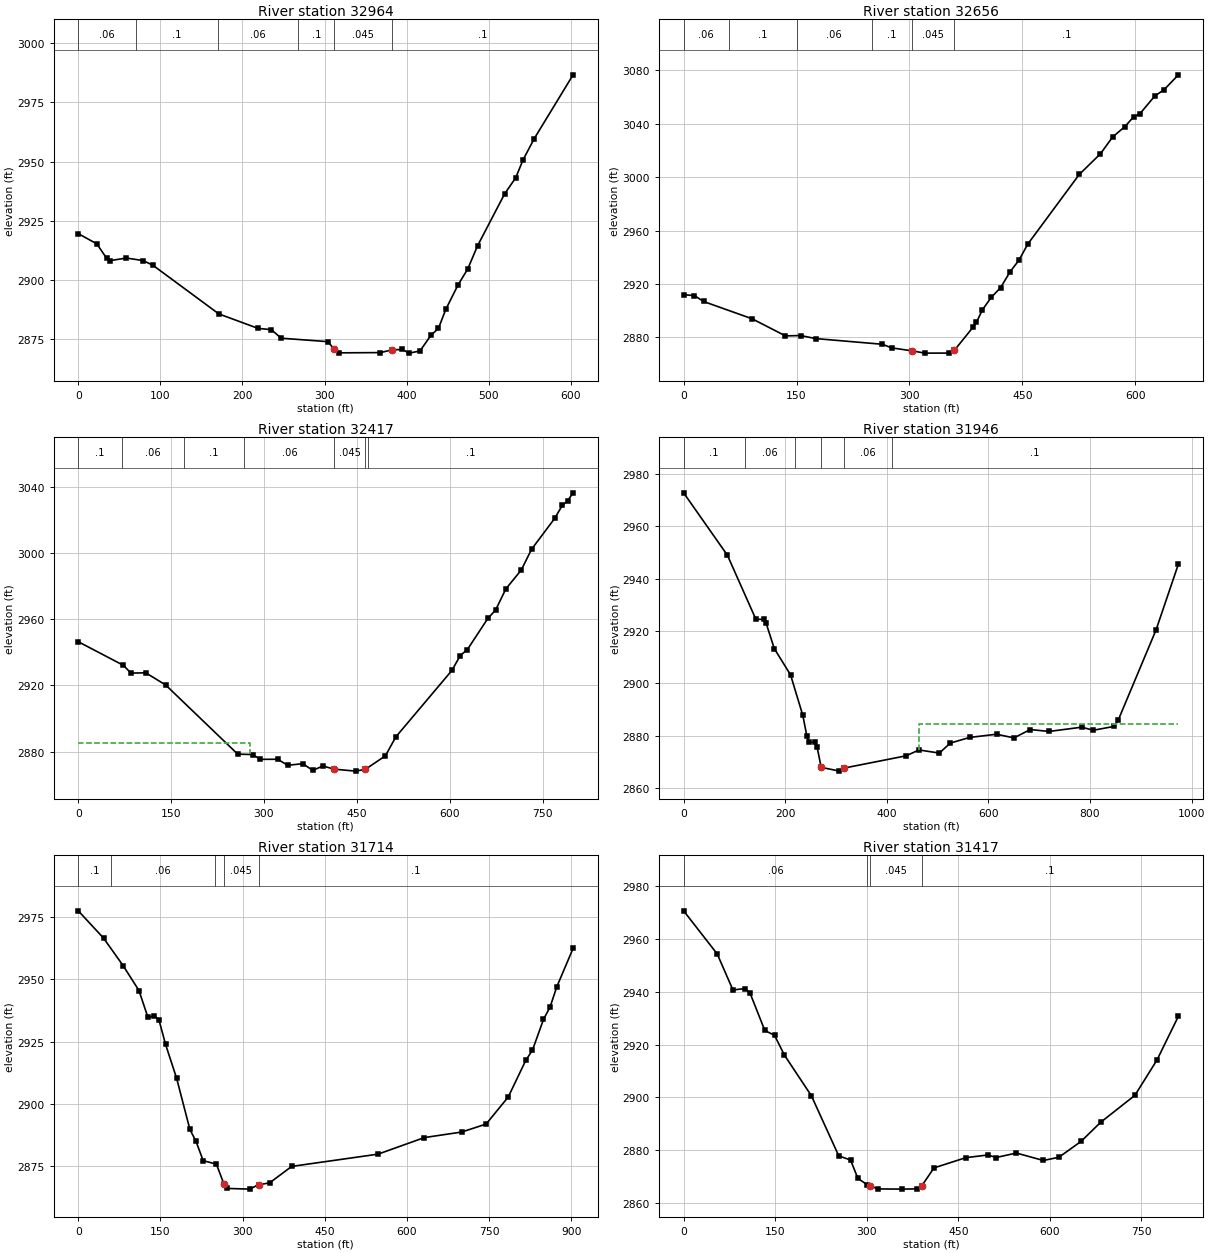
Type RM Length L Ch R = 1 ,32964   ,273,307.9,330.4
XS GIS Cut Line= 3
2305526.76224187584996.8066094962305269.11231363584979.543826439
2304961.86768989 585135.31600737
#Sta/Elev= 30
       0 2919.63    22.6 2915.31    34.7 2909.15    38.7 2908.25    58.7 2909.33
    78.8 2908.28    90.8 2906.32   171.2 2885.78   219.1 2879.66   235.1 2879.16
   247.1 2875.55   304.1 2874.08   311.52870.967   317.6 2869.37     368 2869.47
   381.92870.603   394.5  2870.8     403 2869.25   416.2 2870.16   429.7 2876.83
   438.7 2879.68   447.6 2887.66   462.5 2897.97   474.4 2904.73   486.3 2914.48
   519.4 2936.45   532.8 2943.16   541.8 2950.75   555.3 2959.63   602.7 2986.57
#Mann= 6 ,-1,0
       0     .06       0      70      .1       0     170     .06       0
  268.23      .1       0   311.5    .045       0   381.9      .1       0
Bank Sta=311.5,381.9
XS Rating Curve= 0 ,0
Exp/Cntr(USF)=0,0
Exp/Cntr=0.3,0.1

Type RM Length L Ch R = 1 ,32656   ,238.1,239,240.4
XS GIS Cut Line= 3
 2305510.5187224584763.9413697952305055.03484636584710.887850142
2304857.05463887584729.003686121
#Sta/Elev= 30
       0 2912.01    14.4 2911.35    26.5 2906.92      91 2893.97   135.3 2881.16
   155.4 2881.42   175.5 2879.14   264.1 2874.88   276.2  2872.2     304 2869.92
   320.5 2868.25   352.7 2868.28   359.6 2870.26   384.9 2887.94     389 2891.28
     397  2900.7   408.6 2909.94   421.2 2917.34   433.8 2929.26   445.3 2937.65
   457.4 2950.03   525.7 3002.11   553.8 3017.55     570 3030.15     586 3037.77
     598 3045.27     606 3047.39   626.1  3060.9   638.2 3065.47   657.4 3076.69
#Mann= 6 ,-1,0
       0     .06       0      60      .1       0     150     .06       0
     250      .1       0     304    .045       0   359.6      .1       0
Bank Sta=304,359.6
XS Rating Curve= 0 ,0
Exp/Cntr(USF)=0,0
Exp/Cntr=0.3,0.1

Type RM Length L Ch R = 1 ,32417   ,480,471.5,458.5
XS GIS Cut Line= 4
2305625.01255771584531.768238399 2305387.3800674584516.973049781
2305117.58309122584476.0721545712304839.53610661584552.640849475
#Sta/Elev= 30
       0 2946.41      73 2932.12      85 2927.44     109 2927.61   141.1 2920.28
   257.5 2878.44   281.8 2878.17   293.9 2875.28   322.2 2875.32   338.4 2871.67
   362.7 2872.66   378.9 2868.59   395.1 2871.25   413.8 2869.32     448 2868.15
   463.8 2869.23   496.2 2877.41     513 2888.84   603.7 2929.08   617.1 2938.05
   628.6 2941.67   661.8 2960.57   674.2 2965.58   690.8 2978.37   715.7 2989.79
   732.3 3002.32   769.7 3021.03   782.1 3028.98   790.4 3031.54   799.4 3036.47
#Mann= 7 ,-1,0
       0      .1       0      70     .06       0     170      .1       0
  268.09     .06       0   413.8    .045       0   463.8     .06       0
  468.09      .1       0
#XS Ineff= 2 , 0
          276.94 2884.96
Permanent Ineff=
       F       F
Bank Sta=413.8,463.8
XS Rating Curve= 0 ,0
Exp/Cntr=0.3,0.1

Type RM Length L Ch R = 1 ,31946   ,234,231.9,228.9
XS GIS Cut Line= 3
2305650.06670231584027.9665330882305114.32448111584070.161865747
2304734.46356275583854.855309836
#Sta/Elev= 30
       0 2972.76    86.2 2948.91   142.3 2924.41   158.4 2924.45   162.4 2922.95
   178.4 2913.27   210.5  2903.2   234.6 2887.72   242.6 2879.82   246.7 2877.48
   258.7 2877.41   262.7  2875.7   270.7 2867.88   306.8 2866.42   314.9 2867.55
   438.1 2872.28   463.3 2874.51   503.4 2873.32   524.9 2877.13   562.9 2879.29
     616 2880.52   650.2 2879.12   682.4 2882.31   719.2 2881.58   783.6 2883.21
   806.5 2882.04   847.6 2883.52   855.8 2886.06     930 2920.41     974 2945.57
#Mann= 6 ,-1,0
       0      .1       0     120     .06       0     220      .1       0
   270.7    .045       0   314.9     .06       0     410      .1       0
#XS Ineff= 2 , 0
                          462.54         2884.57
Permanent Ineff=
       F       F
Bank Sta=270.7,314.9
XS Rating Curve= 0 ,0
Exp/Cntr(USF)=0,0
Exp/Cntr=0.3,0.1

Type RM Length L Ch R = 1 ,31714   ,284.4,296.5,307.6
XS GIS Cut Line= 3
2305609.87851133583782.4446560832305060.21079949583859.443559117
2304714.58245276583819.220429324
#Sta/Elev= 30
       0 2977.35    46.1 2966.43    81.9 2955.39   110.8 2945.41   126.9 2934.82
     139 2935.24   147.1 2933.78   159.2 2923.93   179.4 2910.34   203.7 2889.81
   214.9 2885.02   227.9 2877.33   252.1 2875.91   266.1 2867.81   272.3  2866.2
   312.7 2865.92   328.9 2867.68   349.1 2868.41   389.5 2875.02     547 2879.92
   631.6 2886.56     700 2888.79   744.3 2891.98   784.6 2902.79   816.8 2917.54
   828.9 2921.58     849 2933.88   861.1  2938.9   873.2 2946.89     903 2962.32
#Mann= 5 ,-1,0
       0      .1       0      60     .06       0     250      .1       0
   266.1    .045       0   328.9      .1       0
Bank Sta=266.1,328.9
XS Rating Curve= 0 ,0
Exp/Cntr=0.3,0.1

Type RM Length L Ch R = 1 ,31417   ,357.6,353.4,351.6
XS GIS Cut Line= 2
2305660.62136338583560.5322654592304853.17267402583488.068921542
#Sta/Elev= 30
       0 2970.65    55.1 2954.29    80.8 2940.66   100.9 2941.22   108.9 2939.44
     133 2925.33     149 2923.46   165.1 2916.01   209.3  2900.6   254.1 2877.85
   273.5 2876.23   285.6 2869.25   301.2 2866.84   305.6  2866.5   317.7  2865.3
   357.9 2865.22     382 2865.32   390.5 2866.56   410.1 2873.25   462.3 2877.14
   498.4 2878.15   512.1  2877.2   545.2 2878.89   589.5 2876.07   614.9  2877.3
   651.1 2883.29   683.2 2890.52   739.4 2900.76   775.6 2914.15   810.7 2930.74
#Mann= 4 ,-1,0
       0     .06       0   301.2      .1       0   305.6    .045       0
   390.5      .1       0
Bank Sta=305.6,390.5
XS Rating Curve= 0 ,0
Exp/Cntr(USF)=0,0
Exp/Cntr=0.3,0.1

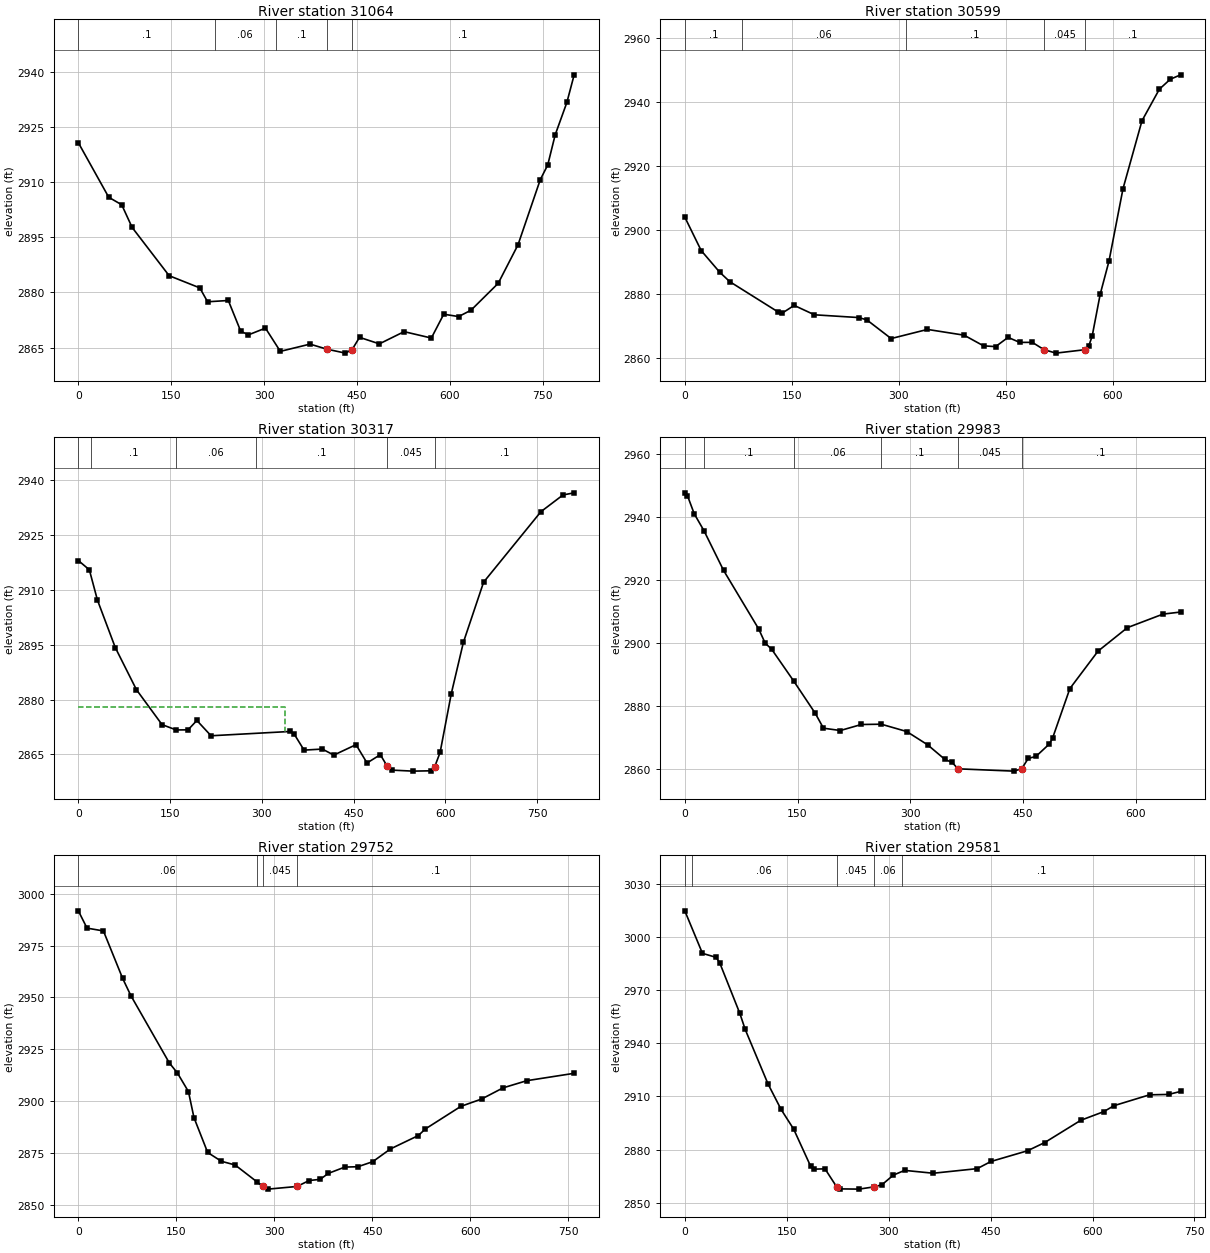
Type RM Length L Ch R = 1 ,31064   ,420.2,464.8,492.8
XS GIS Cut Line= 3
2305762.84643783583251.269065528 2305535.1044998583177.511733327
2304973.51358445583180.099709895
#Sta/Elev= 30
       0 2920.68    49.1 2905.85    70.1  2903.8    86.9 2897.64   146.7 2884.52
   196.2 2881.21   208.8 2877.43   242.3 2877.78   262.3 2869.44   274.8 2868.44
   302.3 2870.27   326.3 2863.95   374.3 2865.92   401.2 2864.56   431.5 2863.47
   442.3 2864.44   454.3 2867.76   486.3 2865.99   526.3 2869.31   570.3 2867.57
   590.3 2874.05   614.3 2873.41   634.3 2875.13   678.3 2882.45   710.3 2892.92
   746.3 2910.65   758.3 2914.61   770.3 2922.79   789.2 2931.61     801 2939.13
#Mann= 5 ,-1,0
       0      .1       0     220     .06       0  319.39      .1       0
   401.2    .045       0   442.3      .1       0
Bank Sta=401.2,442.3
XS Rating Curve= 0 ,0
Exp/Cntr(USF)=0,0
Exp/Cntr=0.3,0.1

Type RM Length L Ch R = 1 ,30599   ,278.9,282.6,285.3
XS GIS Cut Line= 2
 2305773.1983441583137.3980965162305280.18880781582646.976536792
#Sta/Elev= 30
       0 2904.08      23  2893.6      49 2886.82    63.1 2883.87   131.2 2874.34
   136.9 2874.07   153.4 2876.44   181.8  2873.5   244.1 2872.63   255.3 2871.91
   289.4 2866.06   340.3 2868.92   391.7 2867.12     419 2863.78   435.9 2863.54
   453.4 2866.43   469.7 2864.86   487.4 2864.87   503.6 2862.61   520.5  2861.5
   561.8 2862.59   566.6 2863.78   571.3 2866.78   582.6 2879.94   594.9 2890.27
   614.6 2912.99   641.2 2934.24   665.6 2944.13   680.9 2947.24   695.4 2948.62
#Mann= 5 ,-1,0
       0      .1       0      80     .06       0     310      .1       0
   503.6    .045       0   561.8      .1       0
Bank Sta=503.6,561.8
XS Rating Curve= 0 ,0
Exp/Cntr(USF)=0,0
Exp/Cntr=0.3,0.1

Type RM Length L Ch R = 1 ,30317   ,320.3,333.3,343.8
XS GIS Cut Line= 4
2305964.11903377582938.690510051 2305748.6125667582733.673751835
2305502.01181437582464.7302967522305358.84892308582502.009047771
#Sta/Elev= 30
       0 2918.09      18 2915.55    31.2 2907.27    60.4 2894.26      95 2882.72
   136.8 2873.17     160 2871.71   179.3 2871.74   193.7 2874.31   216.9 2870.12
   345.4 2871.29   352.4 2870.68   368.9 2866.19   398.7 2866.48   417.5 2864.83
   453.8 2867.68   471.8 2862.67   493.5 2864.94   504.8 2861.79   513.3 2860.71
   546.7 2860.44   576.3 2860.53   582.2 2861.57   591.2 2865.54   609.5 2881.65
   629.3 2895.71   662.3 2912.16     756 2931.46   792.1 2936.04   810.3 2936.62
#Mann= 6 ,-1,0
       0     .06       0      20      .1       0     160     .06       0
     290      .1       0   504.8    .045       0   582.2      .1       0
#XS Ineff= 2 , 0
          338.03 2878.09
Permanent Ineff=
       F       F
Bank Sta=504.8,582.2
XS Rating Curve= 0 ,0
Exp/Cntr(USF)=0,0
Exp/Cntr=0.3,0.1

Type RM Length L Ch R = 1 ,29983   ,257.4,231.3,187
XS GIS Cut Line= 4
2306158.41885265582663.7646527192305942.63777548582512.858932085
2305818.52839776582297.0778549172305683.13634934582354.901542263
#Sta/Elev= 30
       0 2947.53     3.5 2946.66    12.5  2940.9    25.5 2935.52    51.5 2922.96
    98.3 2904.34   106.9 2899.86   115.5 2897.93   144.7 2887.89   173.6 2877.57
   184.4 2872.88   206.9 2872.14   234.8 2874.05   261.4 2874.14   295.2 2871.82
   322.9 2867.62     346 2862.97   355.7    2862  363.39 2859.99   437.7 2859.26
  448.19 2860.03   456.8  2863.3     467 2863.91   484.9 2867.87   489.1 2869.68
   512.2 2885.45   549.6 2897.31   588.7 2904.77     636 2909.06   659.5 2909.72
#Mann= 6 ,-1,0
       0     .06       0    25.5      .1       0   144.7     .06       0
   261.4      .1       0  363.39    .045       0  448.19      .1       0
Bank Sta=363.39,448.19
XS Rating Curve= 0 ,0
Exp/Cntr(USF)=0,0
Exp/Cntr=0.3,0.1

Type RM Length L Ch R = 1 ,29752   ,192,170.8,140.4
XS GIS Cut Line= 3
2306312.79749498582334.3283205912305879.61816294582195.932553385
2305623.09570313582359.711137692
#Sta/Elev= 30
       0 2991.73    13.3  2983.4    38.4 2982.05    67.8 2959.22    80.4 2950.91
   139.2 2918.54   151.8 2913.59   168.6 2904.68     177 2892.19     198 2875.37
     219 2871.13     240 2869.35   273.6  2861.2     282 2859.02   290.4 2857.72
  334.78    2859   353.4 2861.87   370.2 2862.42   382.8 2865.31     408 2868.34
   427.9  2868.5   450.7 2870.93   477.8 2877.07   520.5 2883.52   531.4 2886.71
   585.6 2897.57   617.5 2901.12   650.3 2906.49   686.6 2909.94   759.1 2913.49
#Mann= 4 ,-1,0
       0     .06       0   273.6      .1       0     282    .045       0
  334.78      .1       0
Bank Sta=282,334.78
XS Rating Curve= 0 ,0
Exp/Cntr(USF)=0,0
Exp/Cntr=0.3,0.1

Type RM Length L Ch R = 1 ,29581   ,179.9,155.2,127.6
XS GIS Cut Line= 3
2306253.02943513582000.5520847212305851.86634186582126.238375746
2305631.48490007582343.176357514
#Sta/Elev= 30
       0 3014.75      26 2990.74    45.9 2988.51    51.2 2985.56      81 2956.84
    88.9 2947.78   122.5    2917   141.6  2902.7   160.2 2891.53   185.3 2870.47
   189.5 2868.94   206.3 2869.11   223.42858.984   227.8  2857.8   256.3 2857.66
   278.9 2858.96   290.1 2860.13   306.9 2865.58   323.5 2868.24   365.6 2866.63
   430.3 2869.23   450.5 2873.27   504.3 2879.31   529.7 2883.97   582.7 2896.52
   616.4 2901.38   631.6 2904.77   683.8 2910.89   711.8 2911.11   729.6 2912.81
#Mann= 5 ,-1,0
       0      .1       0      10     .06       0   223.4    .045       0
   278.9     .06       0     320      .1       0
Bank Sta=223.4,278.9
XS Rating Curve= 0 ,0
Exp/Cntr(USF)=0,0
Exp/Cntr=0.3,0.1

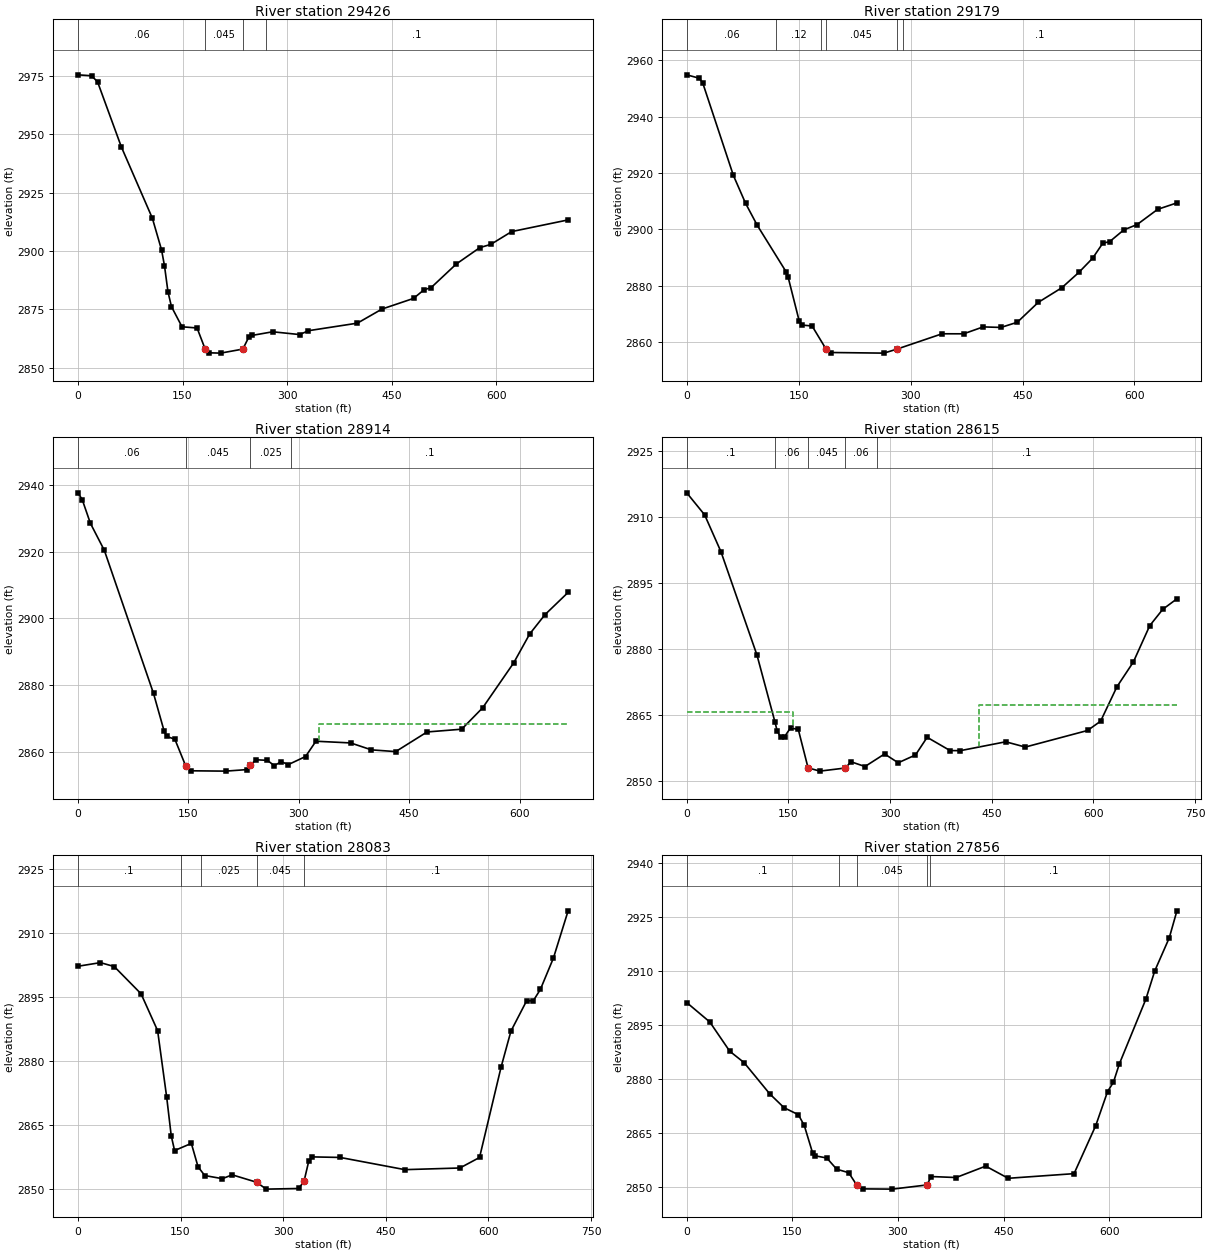
Type RM Length L Ch R = 1 ,29426   ,251,246.9,243.9
XS GIS Cut Line= 2
2306048.81784864581786.4743277772305623.09570313582345.477266566
#Sta/Elev= 30
       0  2975.6    19.5  2975.2    28.1 2972.62    62.3 2944.63   106.7 2914.08
   119.9 2900.45   124.1 2893.64   129.1 2882.47   134.1 2876.12   149.2 2867.49
   170.8 2866.98   182.2 2858.07   187.9 2856.33   204.5 2856.19   236.4 2857.92
   244.7  2862.9   249.8  2863.8   279.2 2865.35     318 2864.15   330.2  2865.8
   400.6 2869.05   435.8 2875.09   481.1 2879.67   496.1 2883.37   506.2 2884.27
   542.4 2894.43   576.1 2901.46   591.7 2902.82   621.8 2908.34   702.7 2913.35
#Mann= 4 ,-1,0
       0     .06       0   182.2    .045       0   236.4     .06       0
     270      .1       0
Bank Sta=182.2,236.4
XS Rating Curve= 0 ,0
Exp/Cntr(USF)=0,0
Exp/Cntr=0.3,0.1

Type RM Length L Ch R = 1 ,29179   ,262,265.4,267.6
XS GIS Cut Line= 2
2305810.72400435581650.6055579332305489.81490986582223.842367848
#Sta/Elev= 30
       0 2954.83    16.7 2953.63    21.3 2952.07    62.5 2919.16    78.9 2909.24
    94.6 2901.42   133.1 2885.02   135.9 2883.06   150.7 2867.56   154.2  2866.1
     168 2865.76   186.3 2857.75   193.6 2856.36   264.2 2856.14   281.2 2857.52
   342.2    2863   371.1 2862.99   397.2 2865.44   421.1 2865.25     443 2867.09
     471 2874.13   502.6 2879.32   525.5 2884.77   543.9 2889.79   557.6 2895.13
   566.8 2895.68   585.7 2899.84   603.5 2901.73     631 2907.12   656.9 2909.42
#Mann= 6 ,-1,0
       0     .06       0     120     .12       0     180     .06       0
   186.3    .045       0   281.2     .06       0     290      .1       0
Bank Sta=186.3,281.2
XS Rating Curve= 0 ,0
Exp/Cntr(USF)=0,0
Exp/Cntr=0.3,0.1

Type RM Length L Ch R = 1 ,28914   ,298.2,298.6,300.2
XS GIS Cut Line= 2
2305567.24606613581562.8219263092305214.92121504582127.852461075
#Sta/Elev= 30
       0 2937.65     5.8 2935.64    16.9 2928.53    35.9 2920.38   102.7 2877.45
   117.2 2866.09   120.6 2864.57   131.7 2863.71   146.2 2855.82   153.6 2854.25
   200.8 2854.15     229  2854.6   233.8  2855.9     242 2857.56   257.3 2857.38
   266.8  2855.8   276.2    2857   285.8 2856.11   309.2 2858.53   323.3 2863.12
   370.5 2862.61   398.7 2860.53   431.7 2860.01   474.3  2865.9   521.3 2866.73
   549.8 2873.15     592 2886.65   613.7  2895.3   634.4 2901.08   665.9 2907.78
#Mann= 4 ,-1,0
       0     .06       0   146.2    .045       0   233.8    .025       0
     290      .1       0
#XS Ineff= 2 , 0
                          327.72         2868.39
Permanent Ineff=
       F       F
Bank Sta=146.2,233.8
XS Rating Curve= 0 ,0
Exp/Cntr=0.3,0.1

Type RM Length L Ch R = 1 ,28615   ,531.5,532.7,537.6
XS GIS Cut Line= 2
2305322.89042119581407.3357604972304917.87208823582006.452336097
#Sta/Elev= 30
       0 2915.56    26.4 2910.55    50.5 2902.15   103.6 2878.64     130 2863.48
   133.4 2861.37   138.7 2859.87   144.4 2860.06   153.1 2862.04   164.6 2861.68
     179 2852.95   196.3  2852.2     234 2852.91   242.4 2854.33     263 2853.25
   291.9 2856.11     312  2854.1   337.5 2855.88   354.7  2859.9   388.5 2856.88
   403.7 2856.86   470.6 2858.88   499.5 2857.68   591.3 2861.45   610.6 2863.57
   634.7 2871.41   658.9 2877.04   683.1 2885.32   702.3 2889.04   723.2 2891.43
#Mann= 5 ,-1,0
       0      .1       0     130     .06       0     179    .045       0
     234     .06       0     280      .1       0
#XS Ineff= 2 , 0
          156.95 2865.57  430.56         2867.24
Permanent Ineff=
       F       F
Bank Sta=179,234
XS Rating Curve= 0 ,0
Exp/Cntr(USF)=0,0
Exp/Cntr=0.3,0.1

Type RM Length L Ch R = 1 ,28083   ,224.5,226.9,232.3
XS GIS Cut Line= 2
2304875.17047485581193.8276935992304461.09422389581778.710398072
#Sta/Elev= 30
       0 2902.13    32.9 2902.98    53.1 2902.06    92.3 2895.68   116.5 2887.05
   129.8 2871.41   136.4 2862.43   141.3 2858.97   165.8 2860.65   175.6 2855.17
   185.4 2853.12   211.2 2852.39   225.5 2853.29   261.3 2851.55   275.2 2849.94
   322.7 2850.09   330.5 2851.77   337.4 2856.47   342.3 2857.49   383.3 2857.36
     478  2854.5   558.4 2854.89   587.1 2857.35   618.6 2878.52     633 2886.94
   655.9 2894.03   665.7 2894.06     676 2896.69   695.1 2904.05   716.6 2915.11
#Mann= 5 ,-1,0
       0      .1       0     150     .06       0     180    .025       0
   261.3    .045       0   330.5      .1       0
Bank Sta=261.3,330.5
XS Rating Curve= 0 ,0
Exp/Cntr(USF)=0,0
Exp/Cntr=0.3,0.1

Type RM Length L Ch R = 1 ,27856   ,393.2,423.3,442.8
XS GIS Cut Line= 4
2304796.44584326581151.7391878022304632.88149193581179.286868027
2304364.29160974581478.8678904692304242.04877874581516.745950778
#Sta/Elev= 30
       0 2901.35    32.7 2895.97    61.1 2887.83    81.4 2884.68   117.9 2875.99
   138.2 2872.15   158.5 2870.21   166.9 2867.23     179 2859.44   181.9  2858.8
   198.9 2858.18     213 2855.06     230  2854.1   241.4 2850.67   249.9  2849.6
     292 2849.53  341.61  2850.7   346.7 2853.03   382.6 2852.75   424.6 2855.92
   456.6 2852.54   550.1 2853.83   580.9 2867.18   597.7 2876.63     606 2879.21
   614.4  2884.3   652.1  2902.3   664.7 2910.14   685.3 2919.32   696.2 2926.83
#Mann= 5 ,-1,0
       0      .1       0  215.87     .06       0   241.4    .045       0
  341.61     .06       0  345.87      .1       0
Bank Sta=241.4,341.61
XS Rating Curve= 0 ,0
Exp/Cntr(USF)=0,0
Exp/Cntr=0.3,0.1

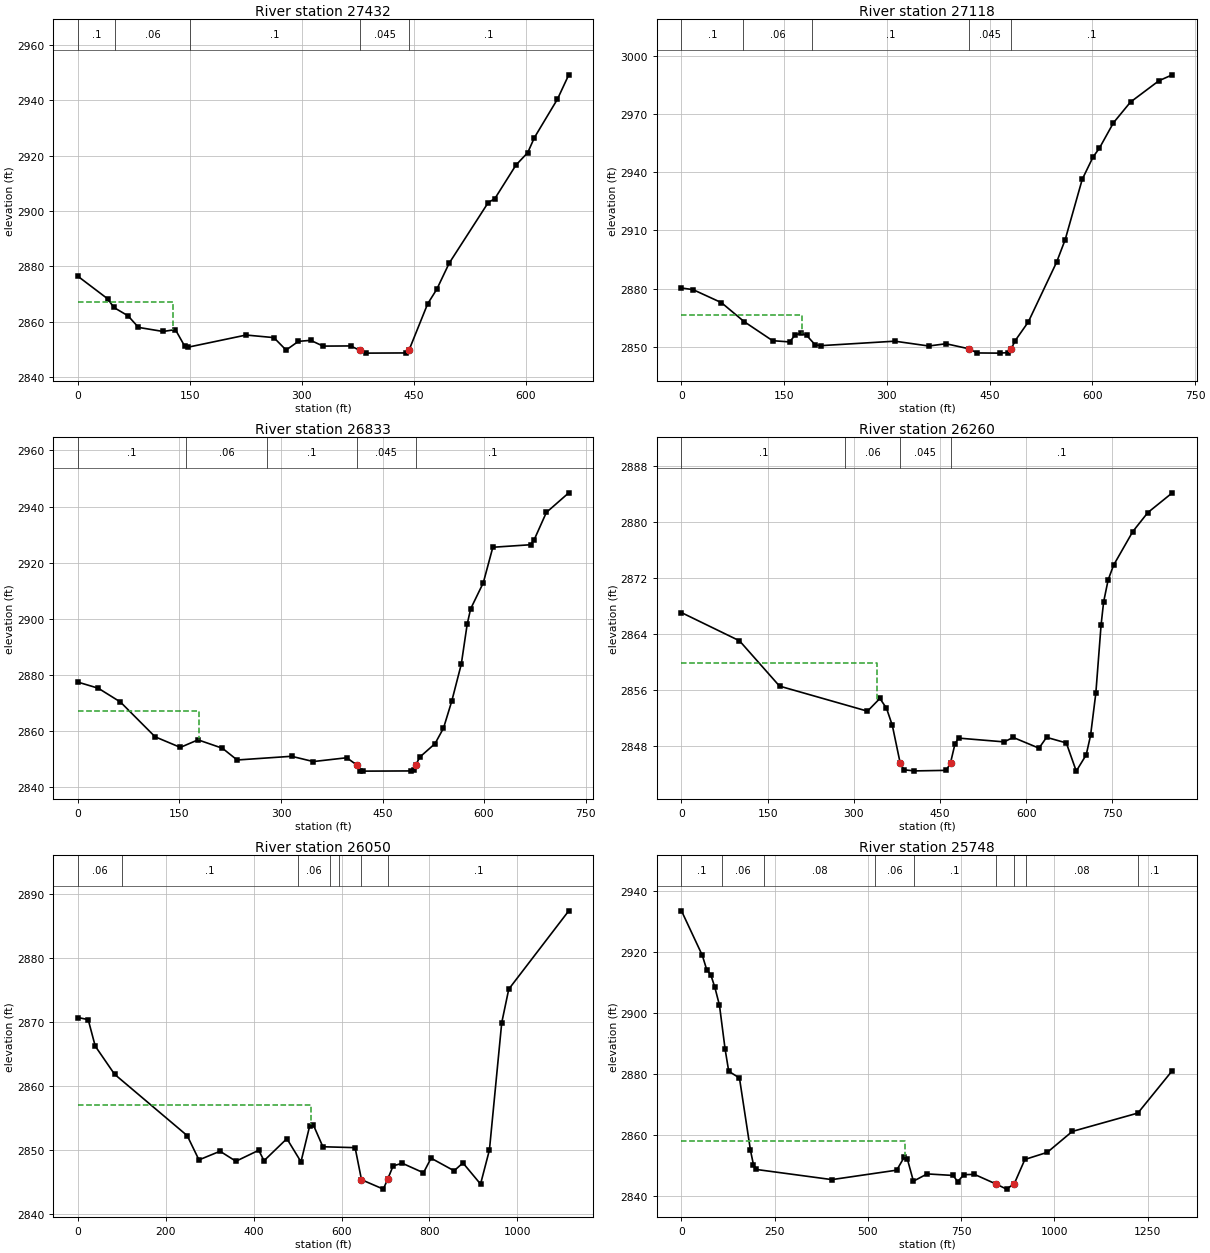
Type RM Length L Ch R = 1 ,27432   ,289.4,314.8,337.7
XS GIS Cut Line= 3
 2304622.8604879580950.3040510232304131.12721141581073.486783165
2303994.39104347581137.468980728
#Sta/Elev= 30
       0 2876.36    39.9 2868.21    48.1  2865.1    67.2 2862.07    81.1 2857.89
   114.1 2856.42   130.6  2857.1     143 2851.14   147.1 2850.71   225.4 2855.13
   262.6  2854.2     279  2849.7   295.5 2852.85     312 2853.21   328.5 2851.13
   365.6 2851.19     378 2849.57   386.3 2848.59   439.9 2848.66     444 2849.83
   468.7 2866.39   481.1 2871.74   497.6 2881.11   549.9 2903.01   558.8 2904.45
   587.1 2916.58   602.9 2921.09   611.8  2926.5   642.7  2940.4   657.9 2949.21
#Mann= 5 ,-1,0
       0      .1       0      50     .06       0     150      .1       0
     378    .045       0     444      .1       0
#XS Ineff= 2 , 0
          127.77 2866.98
Permanent Ineff=
       F       F
Bank Sta=378,444
XS Rating Curve= 0 ,0
Exp/Cntr=0.3,0.1

Type RM Length L Ch R = 1 ,27118   ,268.7,284.7,298.7
XS GIS Cut Line= 2
2304660.36841966580859.9787162672303969.37867588580669.762438485
#Sta/Elev= 30
       0 2880.34    16.8 2879.52    58.3 2872.81    91.5 2863.03     133 2853.23
   157.9 2852.59   166.2 2856.24   174.4    2857   182.7 2855.99   195.2 2851.08
   203.5 2850.67   311.5 2852.97   361.1 2850.49   386.3 2851.65   419.9 2849.04
   431.7 2846.91   464.4 2846.82   477.3  2847.1   481.5 2849.04   487.2  2853.2
   506.4 2862.85   547.8 2893.66   560.3 2905.24   585.2  2936.3     601  2947.8
   610.1 2952.24   630.8 2965.42   655.7 2976.08   697.2 2987.05   716.7 2990.09
#Mann= 5 ,-1,0
       0      .1       0      90     .06       0     190      .1       0
   419.9    .045       0   481.5      .1       0
#XS Ineff= 2 , 0
          176.23 2866.33
Permanent Ineff=
       F       F
Bank Sta=419.9,481.5
XS Rating Curve= 0 ,0
Exp/Cntr(USF)=0,0
Exp/Cntr=0.3,0.1

Type RM Length L Ch R = 1 ,26833   ,577,572.6,561.3
XS GIS Cut Line= 2
2304709.93087868580708.3220351472304087.79348867 580335.63347279
#Sta/Elev= 30
       0 2877.44      30 2875.27    62.7 2870.36     114 2857.95   151.3 2854.18
   177.4 2856.87   213.5 2853.87   235.2 2849.69   315.6 2851.01   347.7 2849.13
   397.2 2850.49   411.8 2847.94     417 2845.92   421.7 2845.72   491.6 2845.79
   496.3 2846.12   499.3 2847.99   505.1 2850.73   527.6 2855.52   540.1 2861.04
   552.3 2870.66   566.4 2883.87   575.1 2898.08   580.2 2903.55   598.9 2912.85
     613 2925.51   668.8 2926.41   674.2 2928.25   692.1 2937.92   725.2 2944.91
#Mann= 5 ,-1,0
       0      .1       0     160     .06       0     280      .1       0
   411.8    .045       0   499.3      .1       0
#XS Ineff= 2 , 0
          179.38 2867.14
Permanent Ineff=
       F       F
Bank Sta=411.8,499.3
XS Rating Curve= 0 ,0
Exp/Cntr=0.3,0.1

Type RM Length L Ch R = 1 ,26260   ,250.7,210.1,178
XS GIS Cut Line= 3
2305018.03283516580475.6771076312304965.88090859580246.126595574
2304393.68464256580009.804129356
#Sta/Elev= 30
       0 2867.06     101 2863.02   170.7 2856.53   323.8 2852.94   345.4 2854.76
   356.9 2853.37   367.1 2850.89  380.64 2845.55   387.5 2844.54   405.5 2844.38
     461 2844.46   468.4 2845.54   476.3  2848.3   482.5 2849.08   561.8 2848.54
   577.4 2849.18   622.4 2847.64   635.6 2849.19     670 2848.39   687.3 2844.35
   704.6 2846.68   712.2 2849.46   721.4 2855.53   730.5 2865.27   734.9 2868.57
   742.8 2871.74   752.2 2873.84   785.7 2878.67   811.9 2881.39   854.5 2884.22
#Mann= 4 ,-1,0
       0      .1       0   285.4     .06       0  380.64    .045       0
   468.4      .1       0
#XS Ineff= 2 , 0
          340.85 2859.91
Permanent Ineff=
       F       F
Bank Sta=380.64,468.4
XS Rating Curve= 0 ,0
Exp/Cntr(USF)=0,0
Exp/Cntr=0.3,0.1

Type RM Length L Ch R = 1 ,26050   ,292.4,301.9,305.6
XS GIS Cut Line= 4
 2305459.4238753579901.7355380952304926.54118884579920.499616138
2304673.30830251580024.0622846532304364.04510257579998.182518969
#Sta/Elev= 30
       0 2870.67    23.3 2870.34    39.3 2866.21    83.3 2861.82   248.7 2852.24
   275.4 2848.46   323.4 2849.81   359.5 2848.25   411.5 2849.96   423.5 2848.33
   475.5 2851.77   507.6 2848.16   527.6 2853.81   535.8 2853.91   557.4 2850.51
   630.8 2850.37   645.32845.371     695  2843.9   705.22845.498   717.3 2847.52
     738 2847.94   786.4 2846.45   803.7 2848.73   856.1 2846.76   876.2 2847.99
   916.3 2844.69   936.5    2850   964.5 2869.85   980.5 2875.09  1117.1 2887.31
#Mann= 7 ,-1,0
       0     .06       0     100      .1       0     500     .06       0
  573.21     .12       0  593.21     .06       0   645.3    .045       0
   705.2      .1       0
#XS Ineff= 2 , 0
          529.35 2857.02
Permanent Ineff=
       F       F
Bank Sta=645.3,705.2
XS Rating Curve= 0 ,0
Exp/Cntr(USF)=0,0
Exp/Cntr=0.3,0.1

Type RM Length L Ch R = 1 ,25748   ,368.1,383,394.6
XS GIS Cut Line= 4
2305437.42672145579511.3515166952305320.74196906579621.144136421
2304891.25014589579684.7023498452304186.02653098579839.980943953
#Sta/Elev= 30
       0 2933.61    55.9 2918.99    67.6 2914.35    78.6 2912.65    89.6 2908.49
   101.9 2902.63   117.1 2888.17   126.7 2881.01   155.5 2878.79   185.1 2855.04
   193.1 2850.36   201.2  2848.8   403.4 2845.48   577.3 2848.58   597.5 2852.85
   605.7  2852.3   622.1 2844.97     659 2847.35   728.6 2846.84   740.9 2844.81
   757.3  2847.1   785.9 2847.19   842.4 2844.11     872 2842.36   892.82844.168
   921.1 2852.09   981.2 2854.42  1048.1 2861.27  1224.2  2867.3  1316.5 2881.21
#Mann= 9 ,-1,0
       0      .1       0     110     .06       0  220.22     .08       0
  520.22     .06       0  624.39      .1       0   842.4    .045       0
   892.8      .1       0  924.39     .08       0 1224.39      .1       0
#XS Ineff= 2 , 0
          598.65 2858.22
Permanent Ineff=
       F       F
Bank Sta=842.4,892.8
XS Rating Curve= 0 ,0
Exp/Cntr(USF)=0,0
Exp/Cntr=0.3,0.1

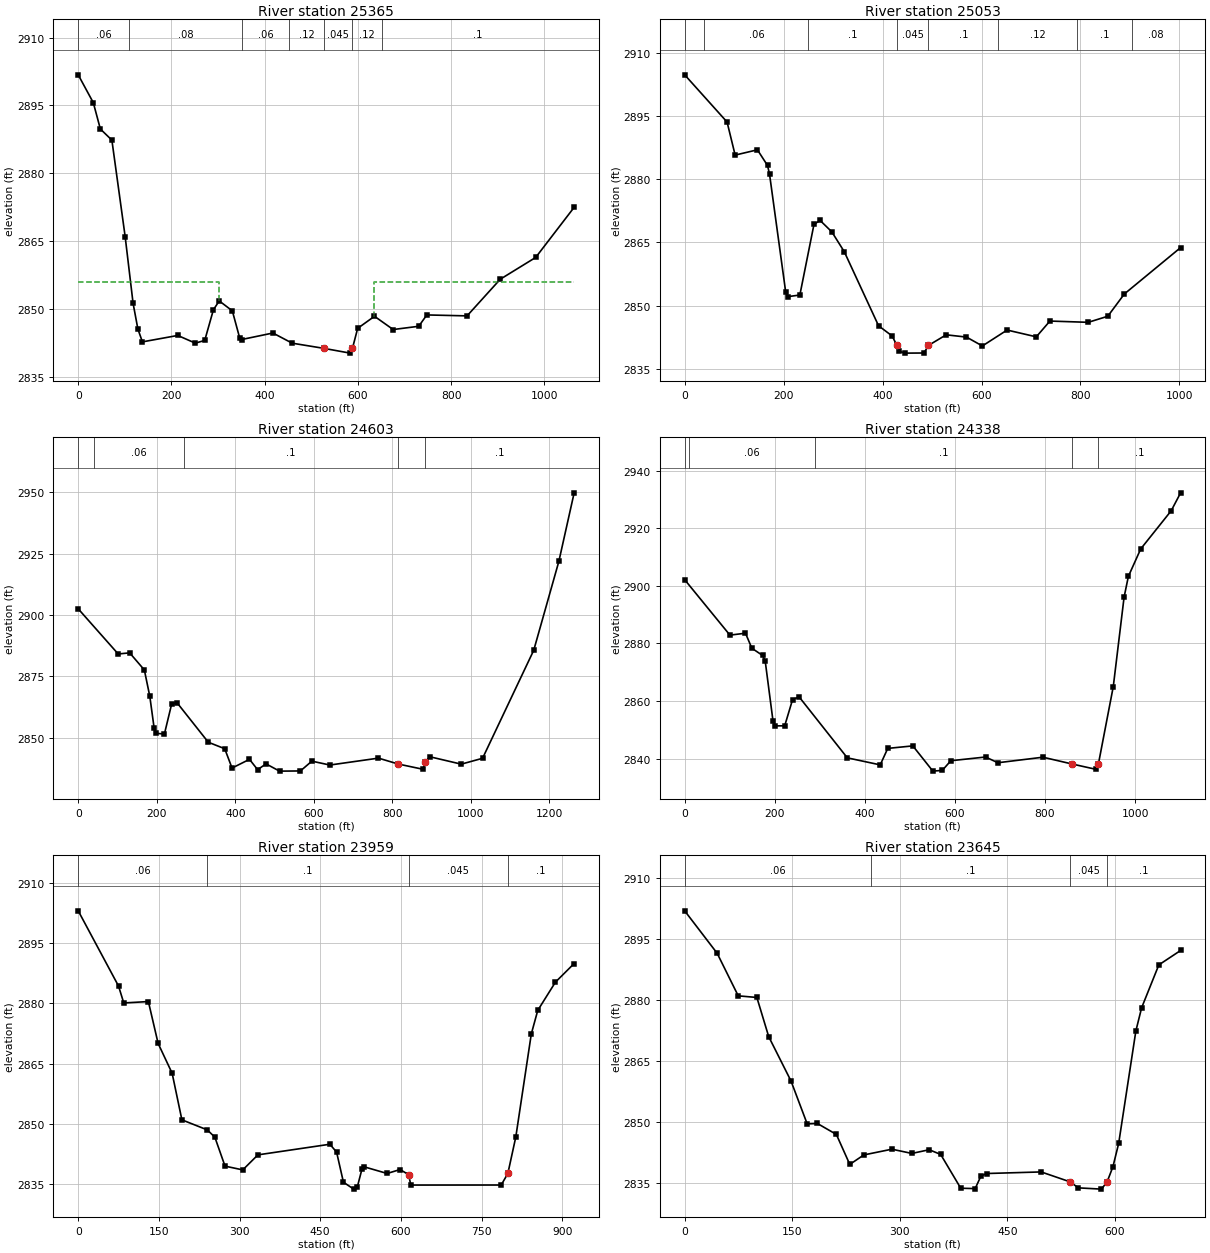
Type RM Length L Ch R = 1 ,25365   ,343,312.2,289.4
XS GIS Cut Line= 4
2305051.91058499579199.3740144022304816.42163515579388.824652237
 2304368.9558983579354.1840482172304079.91949168579473.782259515
#Sta/Elev= 30
       0 2901.77    32.4  2895.6    47.5 2889.78    72.2 2887.33   100.7 2865.98
   117.7 2851.22     128 2845.53   137.7 2842.69   213.5 2844.11   251.2 2842.41
   271.4 2843.01     290  2849.8   302.5 2851.75   330.6 2849.55   346.6 2843.46
   350.6 2843.21   417.6 2844.65     459  2842.4   527.2 2841.25   583.3  2840.2
  588.26 2841.25   599.4 2845.68   635.5 2848.35   675.6 2845.42   730.4 2846.14
   747.8 2848.65   834.1 2848.44   905.3 2856.55   981.3 2861.37  1063.8 2872.46
#Mann= 7 ,-1,0
       0     .06       0     110     .08       0  352.24     .06       0
  452.24     .12       0   527.2    .045       0  588.26     .12       0
  652.24      .1       0
#XS Ineff= 2 , 0
          301.52 2855.92  634.82         2856.01
Permanent Ineff=
       F       F
Bank Sta=527.2,588.26
XS Rating Curve= 0 ,0
Exp/Cntr(USF)=0,0
Exp/Cntr=0.3,0.1

Type RM Length L Ch R = 1 ,25053   ,439.2,450,462.4
XS GIS Cut Line= 3
2305008.09510418579086.3086118362304661.59379696579014.420373823
 2304092.2389519579324.977562038
#Sta/Elev= 30
       0 2904.72    85.7 2893.53     102  2885.7     147 2886.95   167.4 2883.25
   171.5 2881.19   204.2 2853.22   208.3 2852.15   232.8 2852.54   261.3 2869.26
   273.6 2870.23   297.4 2867.51   322.6  2862.8   391.9 2845.25   419.3 2842.84
   428.4 2840.71   433.6  2839.2   445.4 2838.77   483.7  2838.8   492.6 2840.59
   528.6 2843.11   569.6 2842.57   601.7 2840.47   651.7 2844.24   710.7 2842.63
   738.2 2846.37   815.7 2846.07   855.2 2847.51   888.6 2852.78  1002.4 2863.78
#Mann= 8 ,-1,0
       0      .1       0      40     .06       0     250      .1       0
   428.4    .045       0   492.6      .1       0  633.88     .12       0
  793.88      .1       0  903.88     .08       0
Bank Sta=428.4,492.6
XS Rating Curve= 0 ,0
Exp/Cntr(USF)=0,0
Exp/Cntr=0.3,0.1

Type RM Length L Ch R = 1 ,24603   ,229.1,265.6,311.9
XS GIS Cut Line= 4
2305000.90628038579071.9309642332304458.86896576578749.871657935
2304059.17036241  578885.02154542303849.25670741578869.206133037
#Sta/Elev= 30
       0 2902.51   101.8 2884.13     131 2884.59   168.4 2877.63   182.3  2866.9
   193.3 2853.98   198.1 2851.83   219.5 2851.55   238.1 2863.87   252.1 2864.19
   331.2 2848.21   373.1 2845.56   391.7 2837.69   436.1 2841.24   456.8 2837.04
   478.3 2839.39   512.7 2836.44   565.8 2836.51     595  2840.5   640.8 2838.92
   764.6 2841.73   814.9 2839.33   878.2 2837.19   883.52839.958   895.1  2842.3
   975.4 2839.28  1029.7 2841.67    1160 2885.65  1223.9  2921.8  1262.9 2949.73
#Mann= 5 ,-1,0
       0      .1       0      40     .06       0     270      .1       0
   814.9    .045       0   883.5      .1       0
Bank Sta=814.9,883.5
XS Rating Curve= 0 ,0
Exp/Cntr(USF)=0,0
Exp/Cntr=0.3,0.1

Type RM Length L Ch R = 1 ,24338   ,342.5,379,416.8
XS GIS Cut Line= 2
2305013.84616322579050.3644928292304086.48789286578456.567646843
#Sta/Elev= 30
       0 2902.12   100.5 2882.88     135 2883.55   149.2 2878.32     173 2875.83
   178.7    2874   196.1  2853.1   201.5 2851.38   222.1 2851.41   239.5 2860.48
     254 2861.47   361.1 2840.29   434.2 2837.85   450.9 2843.57   506.6 2844.44
   551.1 2835.68     572 2835.94     591 2839.29   668.1 2840.58   695.4 2838.59
   795.5 2840.51   859.2 2838.19   913.9 2836.28   918.7 2838.19   951.7 2865.05
   975.7 2896.09   985.2 2903.27  1012.6  2912.8  1080.2 2926.03  1101.2 2932.27
#Mann= 5 ,-1,0
       0      .1       0      10     .06       0     290      .1       0
   859.2    .045       0   918.7      .1       0
Bank Sta=859.2,918.7
XS Rating Curve= 0 ,0
Exp/Cntr(USF)=0,0
Exp/Cntr=0.3,0.1

Type RM Length L Ch R = 1 ,23959   ,312.2,313.3,278.3
XS GIS Cut Line= 4
2305059.85463555578974.1629605362304697.53791597578748.433893175
2304595.45661799578675.1078904022304583.95449991578305.602347016
#Sta/Elev= 30
       0 2902.99      75 2884.28    84.7 2880.08   130.5 2880.43   148.6 2870.02
   174.7 2862.59   192.8 2851.02     240 2848.52   254.1 2846.71     273 2839.51
     306 2838.57   334.2 2842.31     468 2844.95   480.5    2843   493.2 2835.52
   512.3 2833.79     519 2834.31   527.6 2838.73     532 2839.33   574.5 2837.68
   598.5 2838.66   614.5 2837.39   618.5  2834.8   786.6 2834.81     799 2837.68
   813.8 2846.77   842.6 2872.37   854.6 2878.23   887.5 2885.26   922.3 2889.89
#Mann= 4 ,-1,0
       0     .06       0     240      .1       0   614.5    .045       0
     799      .1       0
Bank Sta=614.5,799
XS Rating Curve= 0 ,0
Exp/Cntr(USF)=0,0
Exp/Cntr=0.3,0.1

Type RM Length L Ch R = 1 ,23645   ,357.3,325.7,294.6
XS GIS Cut Line= 3
2305077.10781267578933.905547248  2304877.258511578725.429657011
2304858.56756911578322.855524139
#Sta/Elev= 30
       0 2901.95    45.3 2891.51    74.7 2881.04   100.7 2880.64   117.2 2871.01
   148.3  2860.1   170.9 2849.54   185.1 2849.65   211.6 2846.95   230.3 2839.58
   249.9 2841.91     289 2843.32   316.9 2842.28   341.1 2843.19   357.1 2842.03
   385.1 2833.72   405.2 2833.63   413.2 2836.69   421.2 2837.34   497.3 2837.73
   537.3 2835.31   549.3 2833.81   581.4  2833.5   589.4 2835.35   597.4 2839.02
   605.4 2844.76   629.4 2872.43   637.4  2878.1   661.4 2888.65   691.8  2892.2
#Mann= 4 ,-1,0
       0     .06       0     260      .1       0   537.3    .045       0
   589.4      .1       0
Bank Sta=537.3,589.4
XS Rating Curve= 0 ,0
Exp/Cntr(USF)=0,0
Exp/Cntr=0.3,0.1