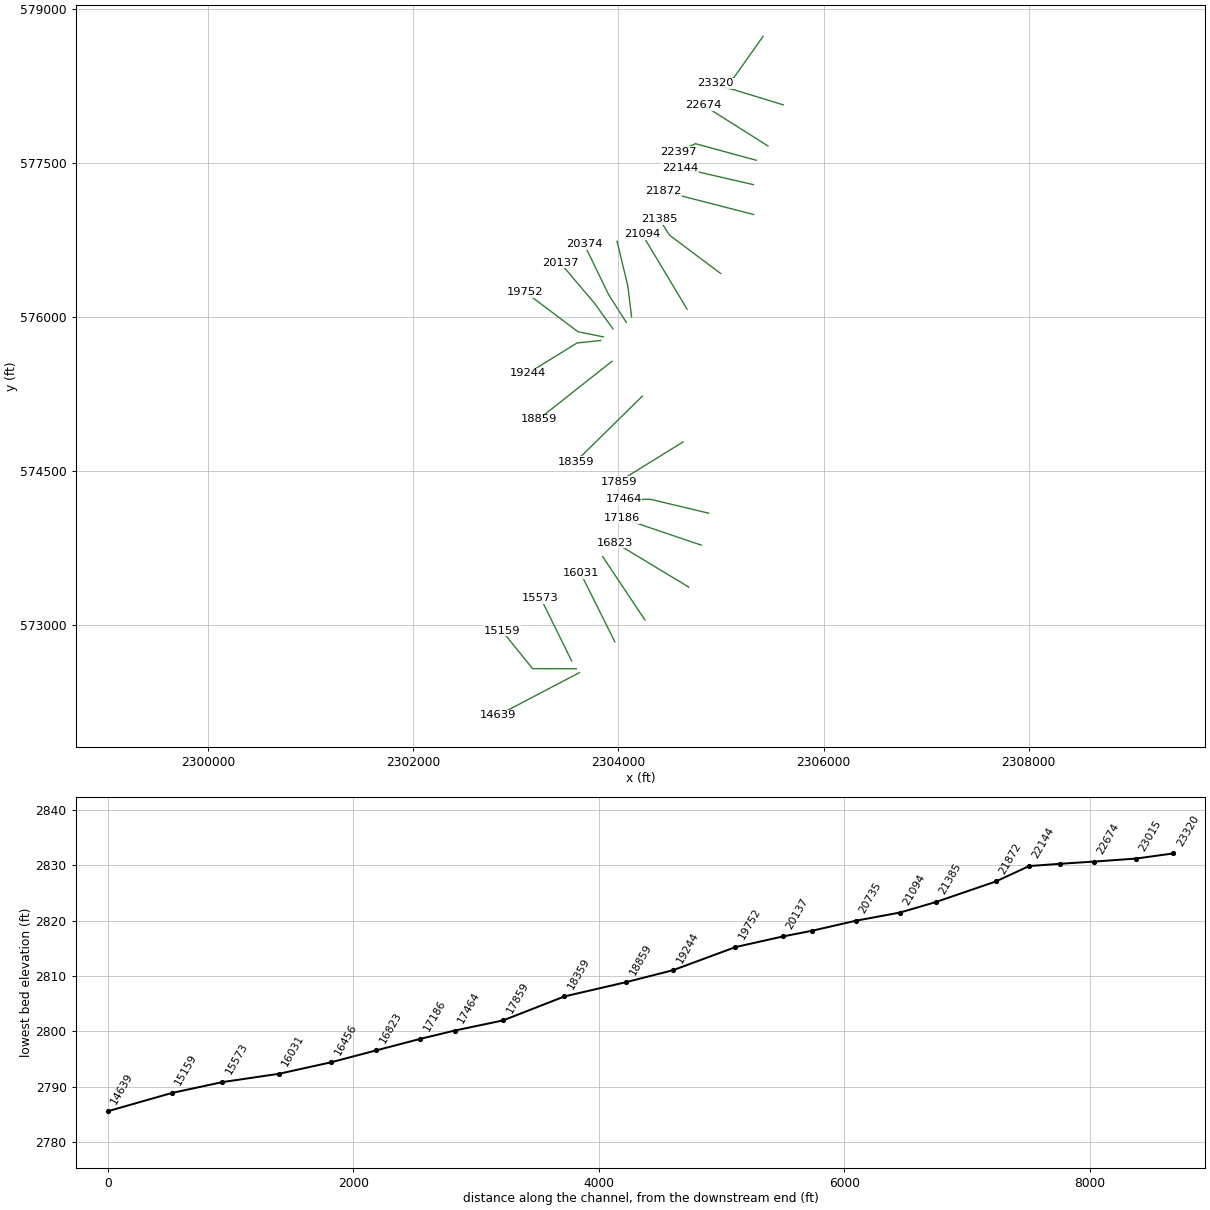
HEC-RAS study WFGRNBRRRV.prj: WFGRNBRRRV

--- WFGRNBRRRV.g01 (geometry) --- (continued)

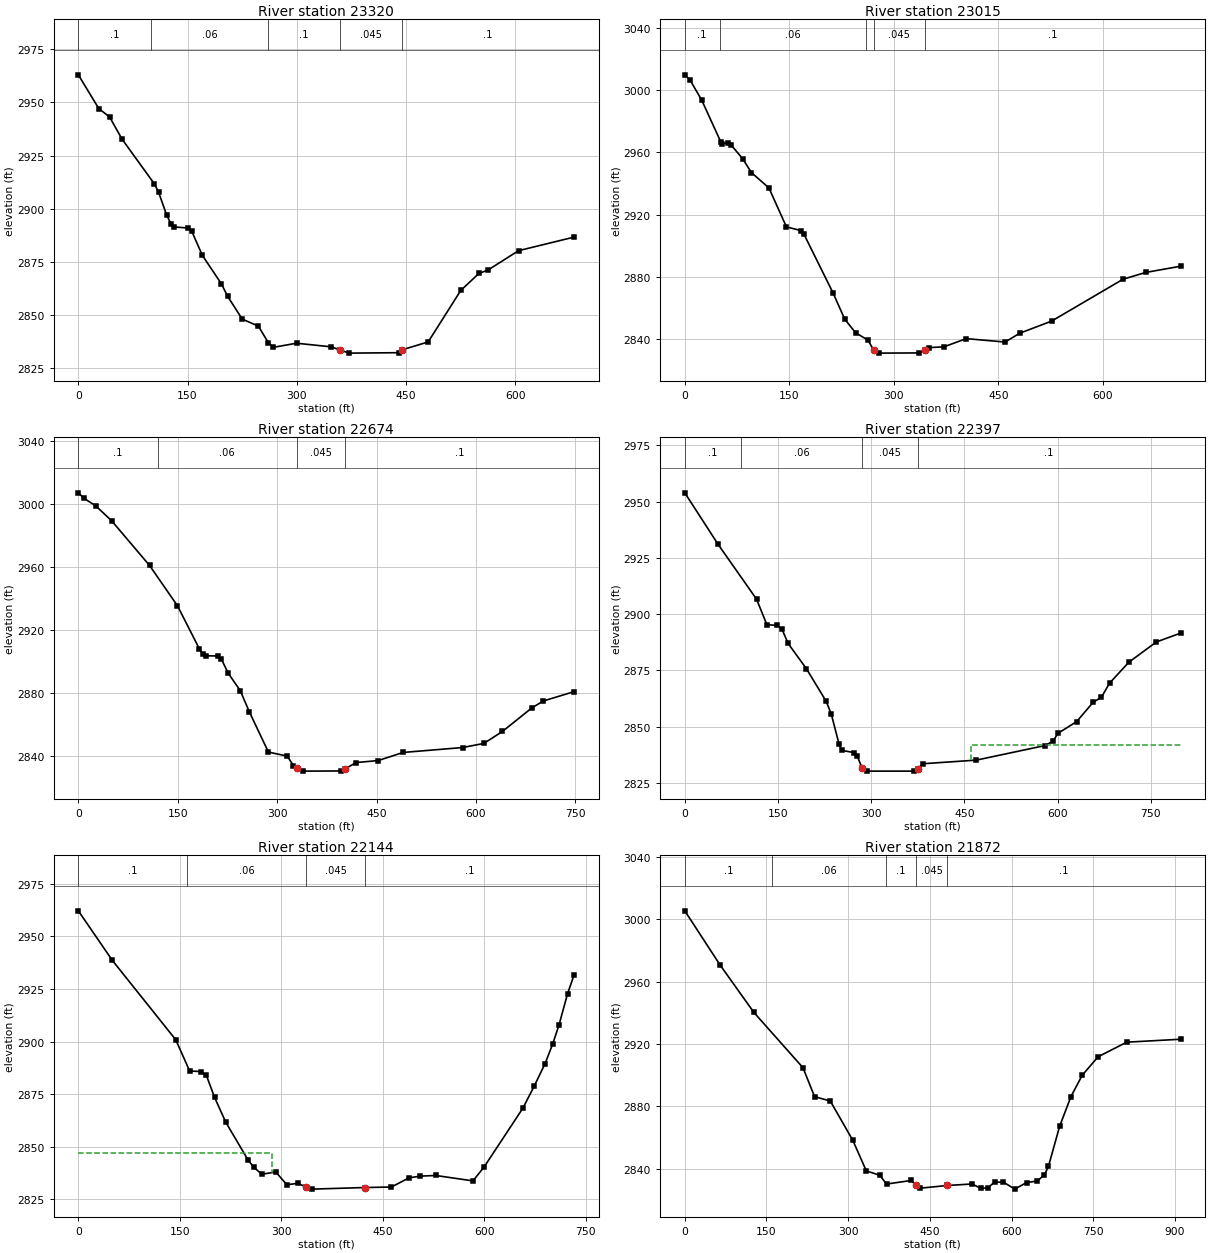
Type RM Length L Ch R = 1 ,23320   ,372.3,305,238.5
XS GIS Cut Line= 3
2305410.88921506578732.2331598572305124.74958577578327.654782909
2304946.56739903578276.296387908
#Sta/Elev= 30
       0 2962.98    28.2 2947.07    42.9 2943.16    60.1  2932.7   104.6 2911.61
   110.3  2907.7   121.3 2897.05   127.5 2892.66   131.1 2891.45   150.2 2890.95
   155.6 2889.58   170.3 2878.08   196.4 2864.74     205 2858.84   225.1 2848.09
   247.2 2844.81     261 2836.99   267.9 2834.82   299.7 2836.75   346.7 2835.07
     360 2833.59   371.2 2832.09   439.8 2832.29   444.7 2833.65   480.5 2837.36
   525.3 2861.59   550.3 2869.58   562.7 2871.18   604.6 2880.27     681 2886.67
#Mann= 5 ,-1,0
       0      .1       0     100     .06       0     260      .1       0
     360    .045       0   444.7      .1       0
Bank Sta=360,444.7
XS Rating Curve= 0 ,0
Exp/Cntr(USF)=0,0
Exp/Cntr=0.3,0.1

Type RM Length L Ch R = 1 ,23015   ,353.8,340.1,326.5
XS GIS Cut Line= 3
2305607.52798803578064.2762477852305116.78660552578214.708296638
2304923.48712109578257.841239445
#Sta/Elev= 30
       0 3009.67     7.7 3006.23    24.4 2993.31    51.4 2966.88    53.7 2965.47
    62.1  2966.2    66.3 2964.75      83 2955.86    95.5    2947   120.7 2937.11
   145.8 2912.14   166.7 2909.75   170.9 2907.47   212.7 2869.74   229.4 2852.95
     245 2844.24   262.8 2839.47   271.3 2832.85   278.8 2831.16   336.4 2831.29
   344.3 2833.16   350.8 2834.72   371.7 2835.18   403.7 2840.46   459.5 2838.27
   480.5 2843.92   526.2 2851.69   628.7 2878.56   661.4 2882.93   711.3  2886.9
#Mann= 5 ,-1,0
       0      .1       0      50     .06       0     260      .1       0
   271.3    .045       0   344.3      .1       0
Bank Sta=271.3,344.3
XS Rating Curve= 0 ,0
Exp/Cntr(USF)=0,0
Exp/Cntr=0.3,0.1

Type RM Length L Ch R = 1 ,22674   ,260.3,277.5,294.1
XS GIS Cut Line= 2
2305458.65511518577663.5651385392304826.03862067 578062.94423861
#Sta/Elev= 30
       0 3007.14     8.8 3003.57    26.2  2998.9    50.2 2989.43   107.4  2961.1
   149.6 2935.49   182.7  2908.1   187.4 2905.06   192.2  2903.8   211.1 2903.63
   215.8  2901.7   226.2 2892.67   244.2 2881.76   258.1 2868.15   286.8 2842.69
   315.1 2840.17   324.6 2834.12   329.3 2832.44   338.8 2830.62   395.6 2830.72
   403.1 2832.22   419.2 2836.07   452.3 2837.31   490.1 2842.47     580 2845.59
   611.9  2848.2   639.9 2855.79   684.4 2870.77   701.8 2875.14   748.1 2881.04
#Mann= 4 ,-1,0
       0      .1       0     120     .06       0   329.3    .045       0
   403.1      .1       0
Bank Sta=329.3,403.1
XS Rating Curve= 0 ,0
Exp/Cntr(USF)=0,0
Exp/Cntr=0.3,0.1

Type RM Length L Ch R = 1 ,22397   ,250.4,253.1,254.8
XS GIS Cut Line= 3
2305343.63393436577524.5812117142304750.95534986577685.930368143
2304584.81364423577607.652064529
#Sta/Elev= 30
       0 2953.95    53.3 2931.16   115.5 2906.64   132.1 2895.31   148.7 2895.02
   156.5 2893.27   166.2    2887   195.6 2875.79   227.4 2861.32   235.7 2855.63
   248.2 2842.24   252.3 2839.45     273 2838.43   277.2 2837.11   285.5 2831.48
   293.3 2830.22   368.4 2830.22   374.8 2831.29     383  2833.5   469.3 2835.12
   579.4 2841.58   592.3 2843.48   600.5 2847.02   630.6 2852.25   657.1 2860.82
   670.4 2863.06   683.6 2869.35   714.6 2878.64   758.8 2887.64   797.9 2891.58
#Mann= 4 ,-1,0
       0      .1       0      90     .06       0   285.5    .045       0
   374.8      .1       0
#XS Ineff= 2 , 0
                          460.07         2841.63
Permanent Ineff=
       F       F
Bank Sta=285.5,374.8
XS Rating Curve= 0 ,0
Exp/Cntr(USF)=0,0
Exp/Cntr=0.3,0.1

Type RM Length L Ch R = 1 ,22144   ,273.3,271.4,270.4
XS GIS Cut Line= 2
2305316.47615556577286.5512680722304602.38632463577451.095457301
#Sta/Elev= 30
       0 2962.14    50.2  2938.6     144 2900.82   164.5 2885.99   180.9 2885.72
   189.1 2884.01   201.4 2873.41   217.9 2861.62   250.7 2843.72   259.3 2840.22
   271.2 2836.89   291.8 2837.95   308.2 2831.92   324.6 2832.55   336.9 2830.73
   345.1 2829.81   423.6 2830.57   462.8 2830.82   488.8 2835.18   505.2 2835.99
   528.3  2836.3   583.2 2833.73   599.6 2840.29   657.1 2868.35   673.5 2878.64
   689.7  2889.4     701 2898.76   710.4 2907.84     723 2922.68   732.8  2931.8
#Mann= 4 ,-1,0
       0      .1       0     160     .06       0   336.9    .045       0
   423.6      .1       0
#XS Ineff= 2 , 0
          286.65 2846.93
Permanent Ineff=
       F       F
Bank Sta=336.9,423.6
XS Rating Curve= 0 ,0
Exp/Cntr(USF)=0,0
Exp/Cntr=0.3,0.1

Type RM Length L Ch R = 1 ,21872   ,505.7,487.7,470.6
XS GIS Cut Line= 2
     2305318.951      576995.577     2304437.101      577222.741
#Sta/Elev= 30
       0 3005.27    64.8 2970.57   126.8 2940.24   217.1 2904.77   238.3 2886.28
   267.2 2883.45   308.5 2858.34   333.3 2838.73   358.1 2835.89   370.5 2830.28
   415.9 2832.58   424.5 2829.54   432.4 2827.64     482 2829.36   527.5 2830.33
     544 2827.46   556.4 2827.88   568.8 2831.49   585.3 2831.51   605.9 2827.03
   627.6 2831.23   647.2 2832.23   660.5 2836.13   667.9 2841.66   688.5 2867.37
   709.2 2886.31   729.8 2899.92     759 2911.79   811.6 2921.14   910.6 2923.03
#Mann= 5 ,-1,0
       0      .1       0     160     .06       0     370      .1       0
   424.5    .045       0     482      .1       0
Bank Sta=424.5,482
XS Rating Curve= 0 ,0
Exp/Cntr=0.3,0.1

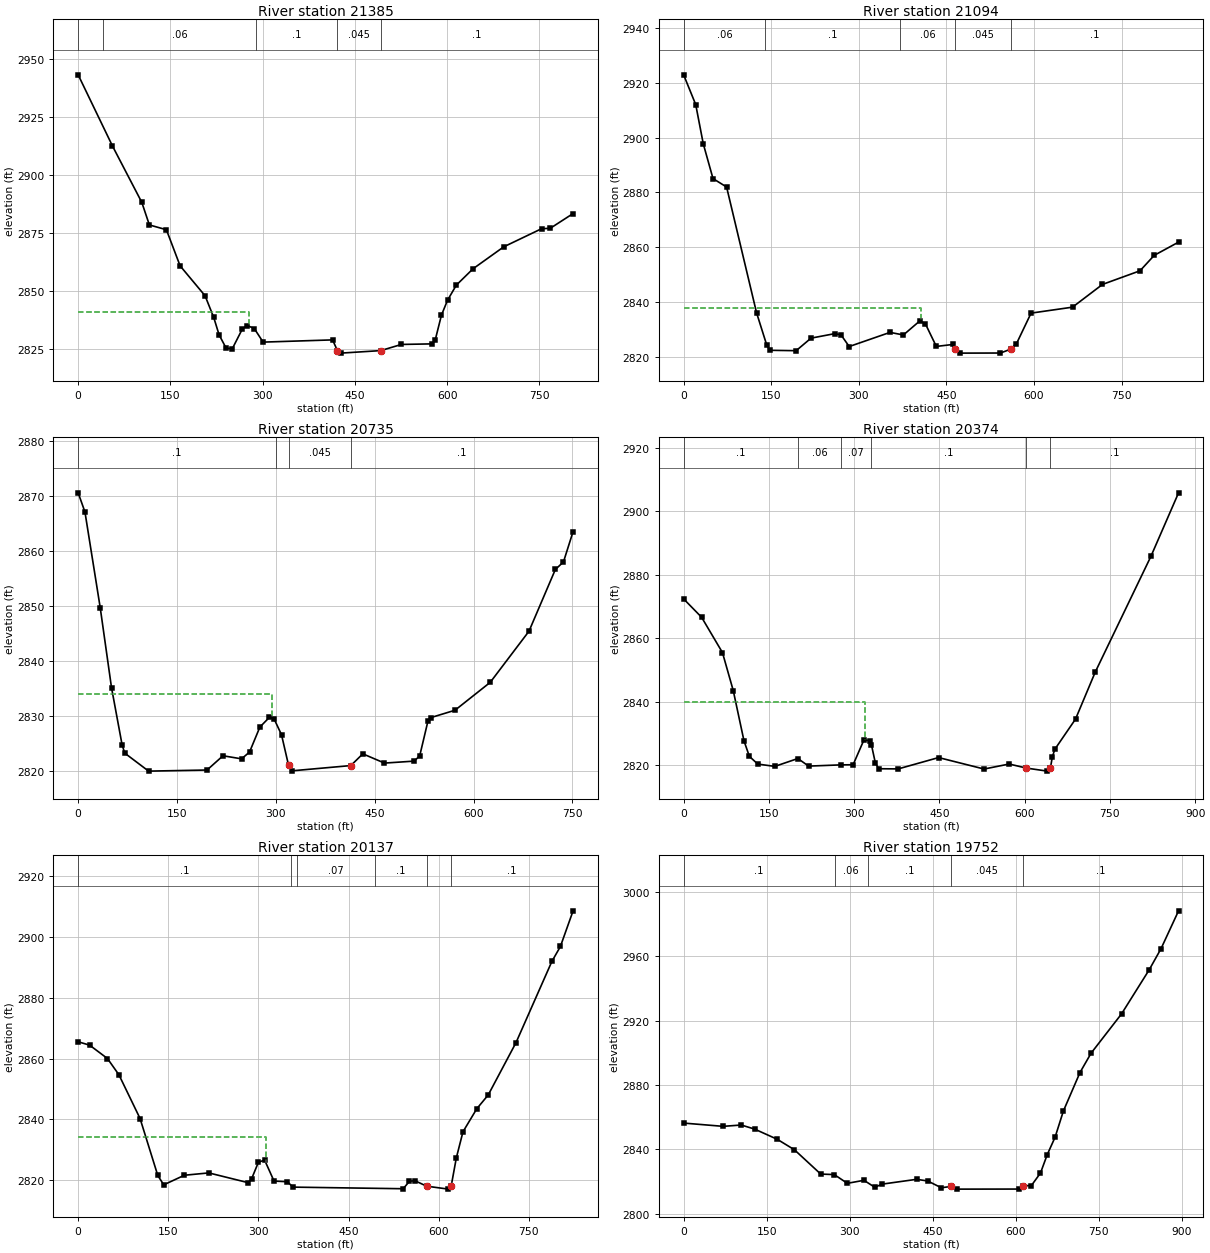
Type RM Length L Ch R = 1 ,21385   ,313.3,291.3,271.7
XS GIS Cut Line= 3
 2304996.8427132576420.9301968032304498.54775861576794.516216784
2304401.46434482576948.572704795
#Sta/Elev= 30
       0 2943.36    55.8 2912.66   103.5 2888.35   115.8 2878.62   143.5 2876.55
   165.8 2860.97   206.4 2848.07   220.5  2838.7   229.2 2831.21   240.8  2825.4
   250.8 2825.29   267.1 2833.79   274.9 2835.24   286.4 2833.94   300.8 2828.08
   413.8 2829.04   421.6 2824.41   427.2 2823.33   492.1 2824.42   525.8 2827.08
   575.8 2827.32   580.7 2829.01   590.8 2839.69   600.7 2846.14     615 2852.65
   642.2 2859.71   692.1 2869.17   753.6 2876.98   767.8 2877.17   804.9 2883.53
#Mann= 5 ,-1,0
       0      .1       0      40     .06       0     290      .1       0
   421.6    .045       0   492.1      .1       0
#XS Ineff= 2 , 0
          277.18 2841.11
Permanent Ineff=
       F       F
Bank Sta=421.6,492.1
XS Rating Curve= 0 ,0
Exp/Cntr=0.3,0.1

Type RM Length L Ch R = 1 ,21094   ,381.5,358.5,343.8
XS GIS Cut Line= 2
2304669.48201344576074.0363202552304233.36003616576800.906282385
#Sta/Elev= 30
       0 2922.86    20.7 2912.02    33.6 2897.75    50.3 2885.05    73.6 2881.97
   124.9 2836.15   142.5 2824.27   148.3 2822.47   192.7 2822.33   218.2  2826.9
   259.1 2828.55   269.6 2828.08   283.6 2823.84   353.5    2829   376.4 2828.06
   404.8 2833.23   414.2 2832.07   432.8 2823.88   460.8 2824.59   465.5 2822.77
   472.6 2821.44   542.6 2821.48   560.1 2822.87   570.1 2824.88   595.1 2836.02
   666.1 2838.19   717.4 2846.48   781.7 2851.45     806 2857.07   847.7 2861.89
#Mann= 5 ,-1,0
       0     .06       0     140      .1       0     370     .06       0
   465.5    .045       0   560.1      .1       0
#XS Ineff= 2 , 0
           406.2 2837.79
Permanent Ineff=
       F       F
Bank Sta=465.5,560.1
XS Rating Curve= 0 ,0
Exp/Cntr(USF)=0,0
Exp/Cntr=0.3,0.1

Type RM Length L Ch R = 1 ,20735   ,375.5,361.5,361.2
XS GIS Cut Line= 3
2304129.17863818575998.995994385   2304092.64994576298.750048483
2303987.34251052576735.408109973
#Sta/Elev= 30
       0 2870.52    10.3 2867.04    33.5 2849.64    50.6 2835.14    66.7 2824.73
    70.7 2823.24   106.9 2819.97   195.6 2820.17   219.8 2822.76     248  2822.2
   260.1 2823.44   275.8 2827.98   290.2 2829.73   297.4 2829.44   308.6 2826.58
   319.32821.024     325 2820.03   413.8 2820.98     432 2823.11   464.9 2821.43
   510.2 2821.79   518.4 2822.78   530.8 2829.04   534.9 2829.68   571.9 2831.03
   625.4  2836.1   684.2 2845.39   724.2  2856.6   736.5 2857.97   751.1 2863.48
#Mann= 4 ,-1,0
       0      .1       0     300     .07       0   319.3    .045       0
   413.8      .1       0
#XS Ineff= 2 , 0
          293.69  2833.9
Permanent Ineff=
       F       F
Bank Sta=319.3,413.8
XS Rating Curve= 0 ,0
Exp/Cntr(USF)=0,0
Exp/Cntr=0.3,0.1

Type RM Length L Ch R = 1 ,20374   ,227.1,236.3,245
XS GIS Cut Line= 3
2304078.18718194575943.523823468 2303905.5623202576215.154120609
2303665.66453441576708.911997187
#Sta/Elev= 30
       0 2872.37    31.6 2866.59    68.3 2855.47    87.3  2843.5   106.2 2827.67
   115.7 2822.77   130.5 2820.36   160.4 2819.63     201 2822.11   219.9 2819.72
   276.8 2820.11   298.2 2820.15     317 2827.87   327.4 2827.78   330.4 2826.44
   337.4 2820.65   343.3 2818.89   377.5 2818.84   448.6 2822.41   528.7  2818.8
   572.8 2820.38   602.7 2819.11   639.8 2818.14   645.4 2819.14   648.7 2822.64
   653.2 2825.04   689.5 2834.52   724.3 2849.36   822.2 2885.78   870.8 2905.77
#Mann= 6 ,-1,0
       0      .1       0     201     .06       0   276.8     .07       0
   330.4      .1       0   602.7    .045       0   645.4      .1       0
#XS Ineff= 2 , 0
          319.44 2839.95
Permanent Ineff=
       F       F
Bank Sta=602.7,645.4
XS Rating Curve= 0 ,0
Exp/Cntr(USF)=0,0
Exp/Cntr=0.3,0.1

Type RM Length L Ch R = 1 ,20137   ,386.3,385.1,392.6
XS GIS Cut Line= 3
2303947.32124436575881.6530741982303767.60499581576130.992129303
2303434.17945902576524.985344609
#Sta/Elev= 30
       0 2865.54    19.1 2864.43    48.7 2860.04    67.8  2854.7     103 2840.32
   132.5  2821.6   142.4 2818.53   176.7 2821.68   217.4 2822.45   282.7 2819.25
   288.5 2820.47   299.9 2825.94   310.2 2826.68   325.9 2819.77   348.2 2819.55
   357.4 2817.78   540.8 2817.25   551.3 2819.71   560.3 2819.89579.85872818.088
   616.1 2817.12   620.7 2818.15   629.2 2827.36   640.3 2835.97   663.3 2843.54
   682.3 2848.07   728.6 2865.29   788.2 2891.94   802.4 2896.85   823.5 2908.57
#Mann= 6 ,-1,0
       0      .1       0  353.76     .06       0  363.76     .07       0
  493.76      .1       0579.8587    .045       0   620.7      .1       0
#XS Ineff= 2 , 0
          312.68 2834.37
Permanent Ineff=
       F       F
Bank Sta=579.8587,620.7
XS Rating Curve= 0 ,0
Exp/Cntr(USF)=0,0
Exp/Cntr=0.3,0.1

Type RM Length L Ch R = 1 ,19752   ,406.9,507.8,580.6
XS GIS Cut Line= 3
2303854.21787898575803.0866478732303606.59188004575853.488399871
2303093.80883797576239.171371682
#Sta/Elev= 30
       0 2856.26    71.3 2854.23   104.1 2855.05   128.1 2852.55   169.1 2846.19
   200.2 2839.67   247.7 2824.57   272.2 2824.25   295.8 2818.82   325.8 2820.69
   345.4 2816.38   358.7 2818.32   420.9  2821.3   440.9 2820.29   465.6 2816.07
   482.7 2816.85   494.2 2815.21   605.6 2815.25   614.1 2817.31   628.4 2817.45
   644.8 2825.21     657 2836.63   671.2 2847.48   686.2 2863.77   716.2 2887.69
   736.2 2899.68   791.3 2924.13   841.3 2951.56   862.7  2964.7   894.3 2988.17
#Mann= 5 ,-1,0
       0      .1       0   272.7     .06       0   332.7      .1       0
   482.7    .045       0   614.1      .1       0
Bank Sta=482.7,614.1
XS Rating Curve= 0 ,0
Exp/Cntr(USF)=0,0
Exp/Cntr=0.3,0.1

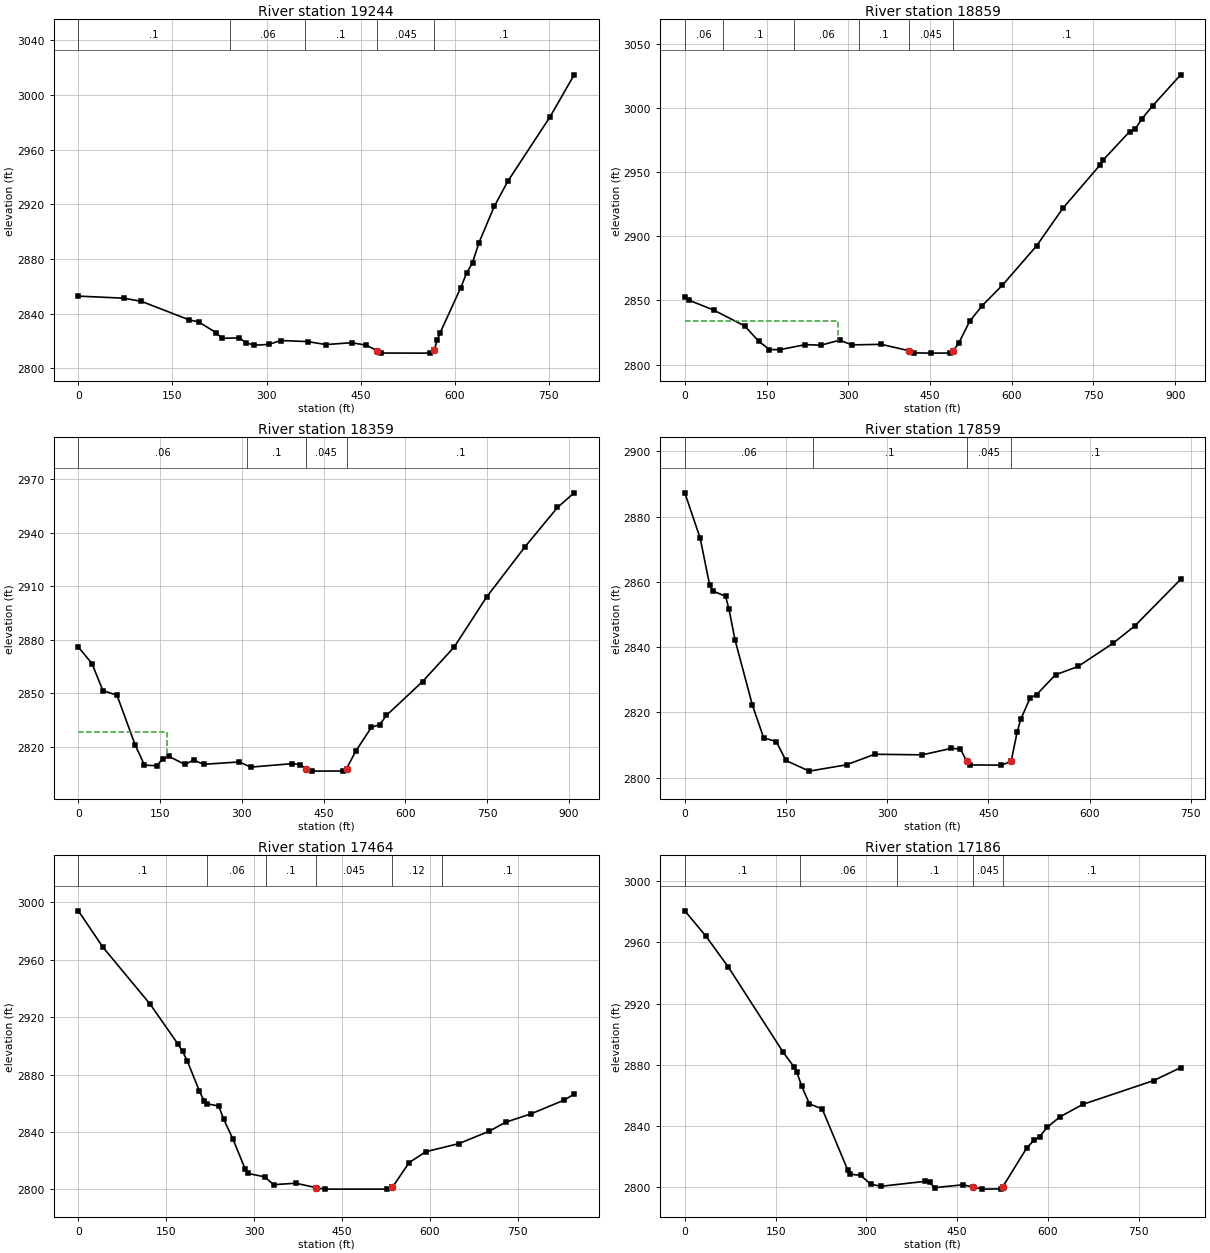
Type RM Length L Ch R = 1 ,19244   ,378.1,384.9,392
XS GIS Cut Line= 3
2303827.92131272575768.0245595262303597.82635795575743.919373788
2303122.29678475575450.274383887
#Sta/Elev= 30
       0 2852.77    72.1 2851.24   100.3 2848.96   176.2 2835.45   191.7  2833.9
   219.3 2826.08     229 2821.87   256.8 2822.23   266.5 2818.78   280.3 2816.83
   303.8 2817.44   322.6 2820.28     366 2819.48   394.4 2817.32   435.4 2818.66
     459 2816.86   475.8 2812.89   482.5 2811.11   560.1 2811.05   567.1 2813.05
   571.7 2820.33   576.5 2825.79   609.5 2859.01   618.8  2869.6   628.2 2877.21
   638.5 2891.84   662.9 2918.44   684.6 2936.89   751.9 2984.01   790.2 3014.66
#Mann= 5 ,-1,0
       0      .1       0  241.35     .06       0  361.35      .1       0
   475.8    .045       0   567.1      .1       0
Bank Sta=475.8,567.1
XS Rating Curve= 0 ,0
Exp/Cntr(USF)=0,0
Exp/Cntr=0.3,0.1

Type RM Length L Ch R = 1 ,18859   ,494.1,500,505.6
XS GIS Cut Line= 2
     2303938.545      575565.496     2303224.472      575001.403
#Sta/Elev= 30
       0  2852.8     8.1 2850.03    53.2  2842.4   110.1 2829.98     136 2817.98
   155.4 2811.67   174.7 2811.57   221.2 2815.51   249.7 2815.07   284.4 2818.97
   306.6 2815.29   360.7 2815.73     412 2810.69     421 2809.06   451.6 2808.88
     486 2808.94   492.4  2810.6   502.6 2816.55     523 2833.82   545.8 2845.85
   582.9 2861.79   645.8 2892.58   693.9 2921.78   762.3 2955.58   768.4 2959.63
   816.4 2981.51   826.5 2983.33     839  2991.5   858.7 3001.62     910 3025.74
#Mann= 6 ,-1,0
       0     .06       0      70      .1       0     200     .06       0
     320      .1       0     412    .045       0   492.4      .1       0
#XS Ineff= 2 , 0
          281.13 2833.92
Permanent Ineff=
       F       F
Bank Sta=412,492.4
XS Rating Curve= 0 ,0
Exp/Cntr=0.3,0.1

Type RM Length L Ch R = 1 ,18359   ,511.4,500,490
XS GIS Cut Line= 2
     2304234.714      575226.257     2303585.781      574588.303
#Sta/Elev= 30
       0 2875.94    25.2 2866.55      45 2851.49    70.9  2848.9   104.4 2820.94
   121.4 2809.66     144 2809.35   155.3 2813.39   166.6 2814.53   195.5 2810.09
   211.9 2812.52   229.8 2810.14   295.2 2811.46   316.5 2808.58   392.9 2810.52
   407.4 2809.98   418.1 2807.57   429.5 2806.32   486.5 2806.41   492.2  2807.7
   509.3 2817.59   537.9 2830.85   553.3 2832.46   565.4 2837.55   631.8 2856.57
   689.9 2875.94   749.3 2903.94     820 2932.18   879.4 2954.18     910 2962.38
#Mann= 4 ,-1,0
       0     .06       0     310      .1       0   418.1    .045       0
   492.2      .1       0
#XS Ineff= 2 , 0
          163.38 2828.49
Permanent Ineff=
       F       F
Bank Sta=418.1,492.2
XS Rating Curve= 0 ,0
Exp/Cntr=0.3,0.1

Type RM Length L Ch R = 1 ,17859   ,452.1,395.4,333.3
XS GIS Cut Line= 2
     2304631.568      574779.7632304006.56587547574393.262981909
#Sta/Elev= 30
       0  2887.3    22.8 2873.39    36.9 2858.97    41.6 2857.21    60.4 2855.59
    65.4 2851.69    74.5 2842.18   100.2 2822.23   116.9 2812.21   135.7 2811.05
   149.8 2805.26   184.5    2802   239.7 2803.94   281.5 2807.17     352 2806.99
   394.3 2808.95   408.5 2808.82   417.9 2804.98   423.2  2803.9   469.3 2803.84
   483.7 2804.99   492.5 2813.88   497.8 2817.83   511.9 2824.44   521.3 2825.43
   549.5 2831.53   582.9 2834.08   634.2 2841.12   666.9 2846.49   734.9 2860.77
#Mann= 4 ,-1,0
       0     .06       0     190      .1       0   417.9    .045       0
   483.7      .1       0
Bank Sta=417.9,483.7
XS Rating Curve= 0 ,0
Exp/Cntr=0.3,0.1

Type RM Length L Ch R = 1 ,17464   ,287.5,277.8,272.4
XS GIS Cut Line= 3
2304881.16626404574084.7380734692304316.35467673 574219.60207343
2304051.13384252574223.275637995
#Sta/Elev= 30
       0 2994.14    42.1  2968.7   122.5 2929.09   169.6 2901.49   177.9 2896.15
   186.1  2889.3   206.6 2868.44   214.9  2861.3     219 2859.69   239.5 2858.11
   247.8 2849.05   263.5 2835.26   284.8 2814.04   288.9 2811.14   317.7 2808.75
   333.2 2803.26   371.1 2804.29   406.2 2801.11   420.5 2800.16   527.4 2800.16
   535.6  2801.3   535.6 2801.31   564.4  2818.7   592.9 2826.25   648.9 2831.85
   700.9 2840.49   728.9 2846.77   772.9 2852.72   828.9 2862.23   845.9 2866.38
#Mann= 6 ,-1,0
       0      .1       0     220     .06       0     320      .1       0
   406.2    .045       0   535.6     .12       0  620.69      .1       0
Bank Sta=406.2,535.6
XS Rating Curve= 0 ,0
Exp/Cntr(USF)=0,0
Exp/Cntr=0.3,0.1

Type RM Length L Ch R = 1 ,17186   ,367.8,362.6,352.9
XS GIS Cut Line= 2
2304807.16012249573774.0426310572304031.41141783574037.008293655
#Sta/Elev= 30
       0 2980.63    34.7 2964.18    72.1 2943.77   162.5 2888.19   180.5 2878.52
   184.8 2875.46   193.2 2865.94   205.9 2854.43     227  2851.1   269.2 2811.14
   273.5 2808.42   290.4 2807.72   307.2 2801.91   324.1 2800.53     396 2803.72
   404.4 2803.04   412.8 2799.66     459  2801.5   476.2 2800.12   490.6 2798.68
   522.7 2798.81   525.3 2800.21   564.9 2825.59   577.6    2831     586 2832.88
   598.7 2839.15   619.9 2845.98   657.8 2854.13   774.5 2869.64   819.1 2878.09
#Mann= 5 ,-1,0
       0      .1       0     190     .06       0     350      .1       0
   476.2    .045       0   525.3      .1       0
Bank Sta=476.2,525.3
XS Rating Curve= 0 ,0
Exp/Cntr(USF)=0,0
Exp/Cntr=0.3,0.1

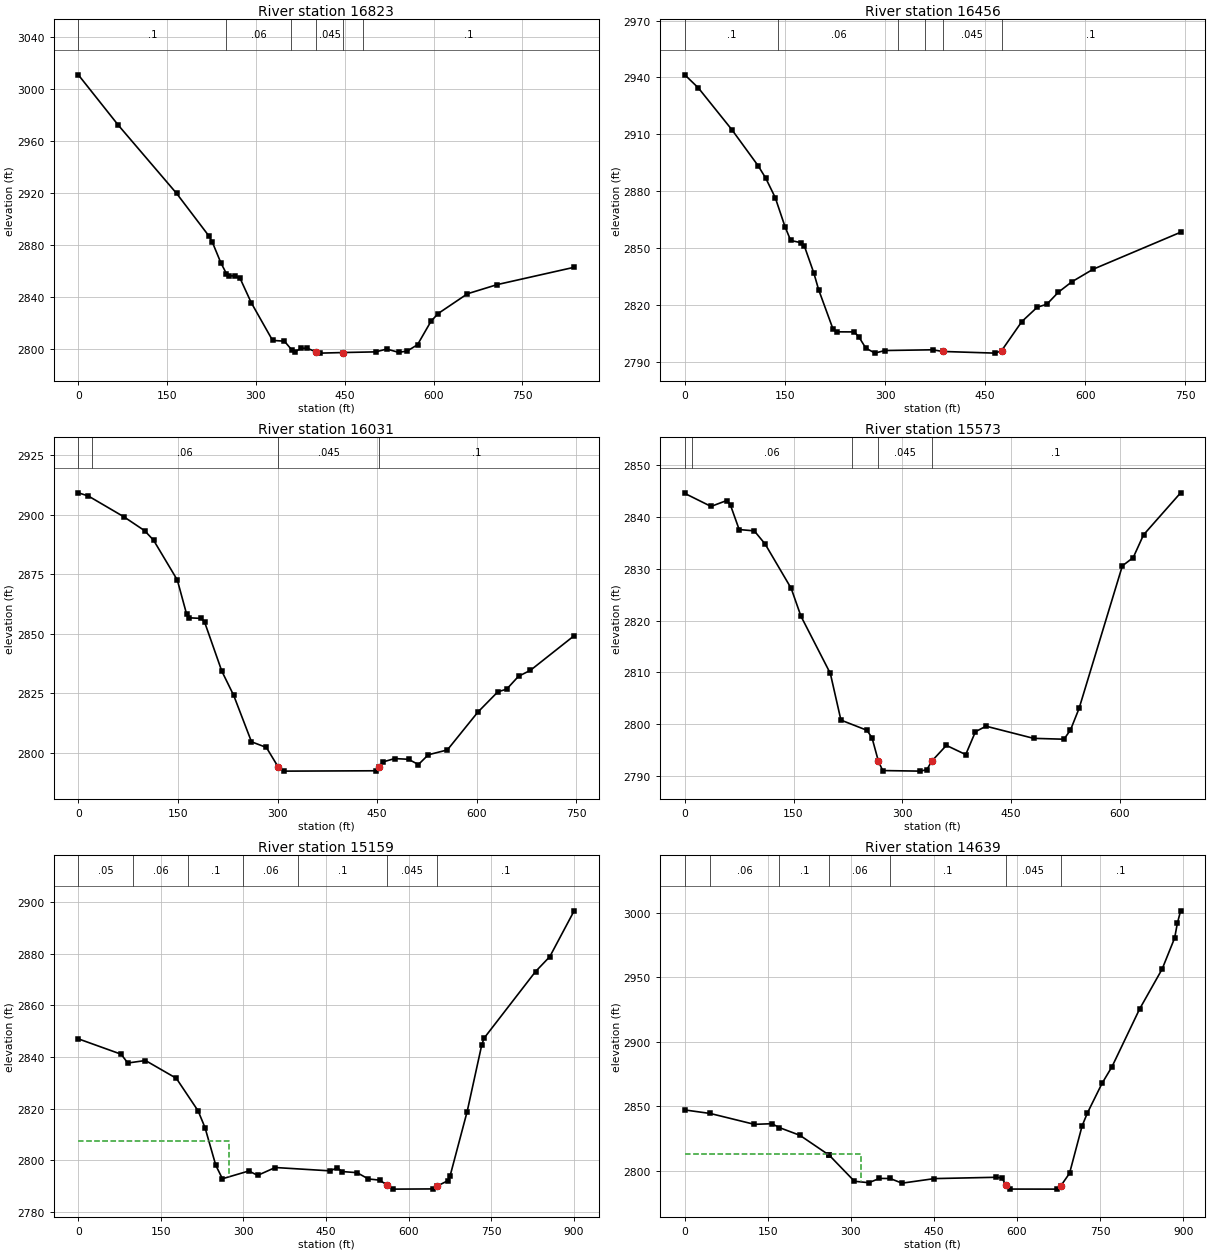
Type RM Length L Ch R = 1 ,16823   ,383.8,367.5,354.9
XS GIS Cut Line= 2
  2304686.173248573364.6852570472303969.22916765573797.548345394
#Sta/Elev= 30
       0 3010.54    67.7 2971.73   165.9 2919.41   220.3  2886.8   226.2 2882.07
   240.6 2866.16     250 2857.79   254.7 2855.95   264.1 2855.99   273.3    2854
     292 2835.42   328.1 2806.36   348.1 2805.76   360.2 2799.23     366 2797.64
   376.1 2800.27   386.4 2800.37     401 2797.62   408.8 2796.58   447.6 2797.04
   502.3 2797.55     521 2799.71   540.8 2797.19   555.4 2798.15   572.9 2803.03
   595.7 2821.09   607.8 2827.02   657.3 2842.22   707.9 2849.31   837.5 2862.58
#Mann= 6 ,-1,0
       0      .1       0     250     .06       0     360     .07       0
     401    .045       0   447.6     .07       0     480      .1       0
Bank Sta=401,447.6
XS Rating Curve= 0 ,0
Exp/Cntr=0.3,0.1

Type RM Length L Ch R = 1 ,16456   ,385.5,424.6,327.9
XS GIS Cut Line= 2
2304259.31499208573044.3129173472303847.33545401573662.282224453
#Sta/Elev= 30
       0 2941.37    20.2  2934.5    70.6 2912.36   109.6 2893.49   121.2 2886.84
   135.5 2876.52   150.1  2861.2   158.6 2853.93   174.1 2852.73   178.9 2851.18
   193.3 2836.72   200.4 2828.01   222.2 2806.95   227.9 2805.68   253.8 2805.64
   260.6 2803.08   271.1 2797.11   284.7 2794.47     300 2795.82   371.2  2796.2
   386.5 2795.32   464.4 2794.44   474.4 2795.67   504.8 2811.08   527.9 2818.68
   542.3 2820.24   559.6 2826.61   579.8  2832.1   611.5 2838.71   742.7 2858.26
#Mann= 6 ,-1,0
       0      .1       0     140     .06       0     320     .07       0
     360      .1       0   386.5    .045       0   474.4      .1       0
Bank Sta=386.5,474.4
XS Rating Curve= 0 ,0
Exp/Cntr(USF)=0,0
Exp/Cntr=0.3,0.1

Type RM Length L Ch R = 1 ,16031   ,459.5,458.9,468.5
XS GIS Cut Line= 2
2303965.67000218572831.7490067472303632.58016289 573500.12006585
#Sta/Elev= 30
       0 2909.15      15 2907.83    68.6 2899.09    99.9 2893.25   113.3 2889.28
   149.1 2872.56   163.2 2858.11     167 2856.71   184.8 2856.45   190.1 2854.97
   216.1 2834.32     234 2824.16   260.8 2804.68   283.2 2802.31     301 2794.12
     310 2792.37   448.5 2792.52   452.6 2793.93   458.5  2796.2   476.4 2797.64
   497.3 2797.34   512.2 2795.13   527.1 2799.23   555.8 2801.26   601.7 2817.11
   631.8 2825.64   645.2 2826.78     663 2832.17   680.9 2834.67   746.8 2849.19
#Mann= 4 ,-1,0
       0      .1       0      20     .06       0     301    .045       0
   452.6      .1       0
Bank Sta=301,452.6
XS Rating Curve= 0 ,0
Exp/Cntr(USF)=0,0
Exp/Cntr=0.3,0.1

Type RM Length L Ch R = 1 ,15573   ,402.6,413.3,428.6
XS GIS Cut Line= 2
2303544.92494202572645.4816624062303242.51443003573259.068208469
#Sta/Elev= 30
       0 2844.59    36.2 2842.07    57.6  2843.2    63.1 2842.29      75  2837.6
    95.9 2837.34   110.9 2834.78   146.8 2826.22   160.2 2820.86   200.8 2809.77
   215.4 2800.75   251.3 2798.78   258.3 2797.33   267.2 2792.75   273.1 2790.99
   325.2 2790.88   334.1 2791.18   340.6 2792.79   360.9 2795.86   387.6 2794.08
     401  2798.5   415.6 2799.57   481.2 2797.22   523.1 2797.05   532.1 2798.82
     544 2803.01   603.7 2830.58   618.7 2832.18   632.9 2836.57   684.1  2844.7
#Mann= 5 ,-1,0
       0     .05       0      10     .06       0     230      .1       0
   267.2    .045       0   340.6      .1       0
Bank Sta=267.2,340.6
XS Rating Curve= 0 ,0
Exp/Cntr(USF)=0,0
Exp/Cntr=0.3,0.1

Type RM Length L Ch R = 1 ,15159   ,439.5,520.2,608.4
XS GIS Cut Line= 3
2303590.01491357572568.5767042412303164.59109278572570.294014836
2302865.14945374572939.618760541
#Sta/Elev= 30
       0 2847.03    77.8 2841.08    89.8 2837.68     122 2838.65     178 2831.78
   217.6 2819.18   230.2 2812.69   249.8 2798.09   261.8 2792.92   309.8 2795.93
   325.8 2794.23   357.8 2797.27   457.8 2795.97   470.3 2797.19     479 2795.71
   506.4 2795.28     527 2792.84   547.6 2792.39   561.4  2790.4   572.2 2788.91
   643.9 2788.99   652.4 2790.14   671.2 2792.15   675.2  2793.8   706.5 2818.93
     733 2844.71   737.3 2847.31   830.8 2873.07   856.6 2878.81   900.9 2896.54
#Mann= 7 ,-1,0
       0     .05       0     100     .06       0     200      .1       0
     300     .06       0     400      .1       0   561.4    .045       0
   652.4      .1       0
#XS Ineff= 2 , 0
          274.09 2807.51
Permanent Ineff=
       F       F
Bank Sta=561.4,652.4
XS Rating Curve= 0 ,0
Exp/Cntr=0.3,0.1

Type RM Length L Ch R = 1 ,14639   ,431.2,461.7,489.8
XS GIS Cut Line= 2
2303619.40988268572530.5901674852302826.56840994572114.447006423
#Sta/Elev= 30
       0 2847.09    46.1 2844.34   125.6 2835.92   157.2  2836.4   170.8 2833.39
   207.9  2827.4   261.2 2811.85   261.2  2811.8   306.3 2791.74   332.3 2790.61
   351.5 2793.94   370.8 2793.88   392.2 2790.26   450.9 2793.81   562.5 2794.83
   572.9 2794.23   579.7 2788.82   587.1 2785.68   672.2 2785.63   679.4  2788.4
   694.8 2797.92   717.4 2834.59   726.9  2844.6   753.6 2867.82   771.6 2880.76
   821.3 2925.43     862 2956.43   884.6 2980.56   889.5 2992.02   895.4 3001.65
#Mann= 7 ,-1,0
       0     .05       0    46.1     .06       0   170.8      .1       0
   261.2     .06       0   370.8      .1       0   579.7    .045       0
   679.4      .1       0
#XS Ineff= 2 , 0
          318.94 2812.93
Permanent Ineff=
       F       F
Bank Sta=579.7,679.4
XS Rating Curve= 0 ,0
Exp/Cntr(USF)=0,0
Exp/Cntr=0.3,0.1