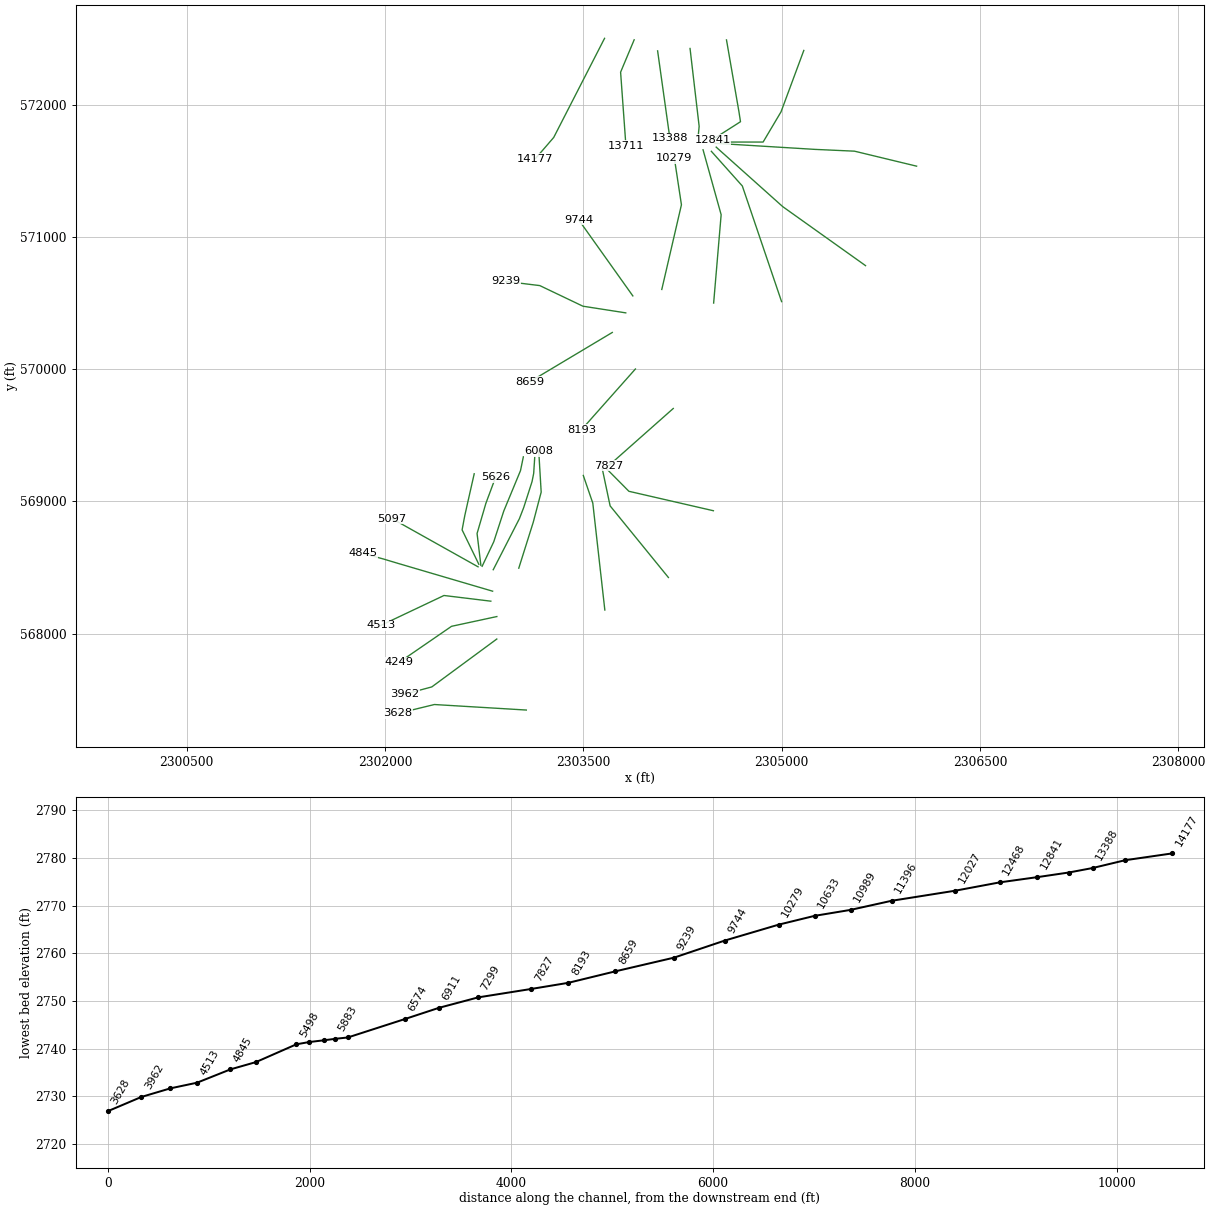
HEC-RAS study WFGRNBRRRV.prj: WFGRNBRRRV

--- WFGRNBRRRV.g01 (geometry) --- (continued)

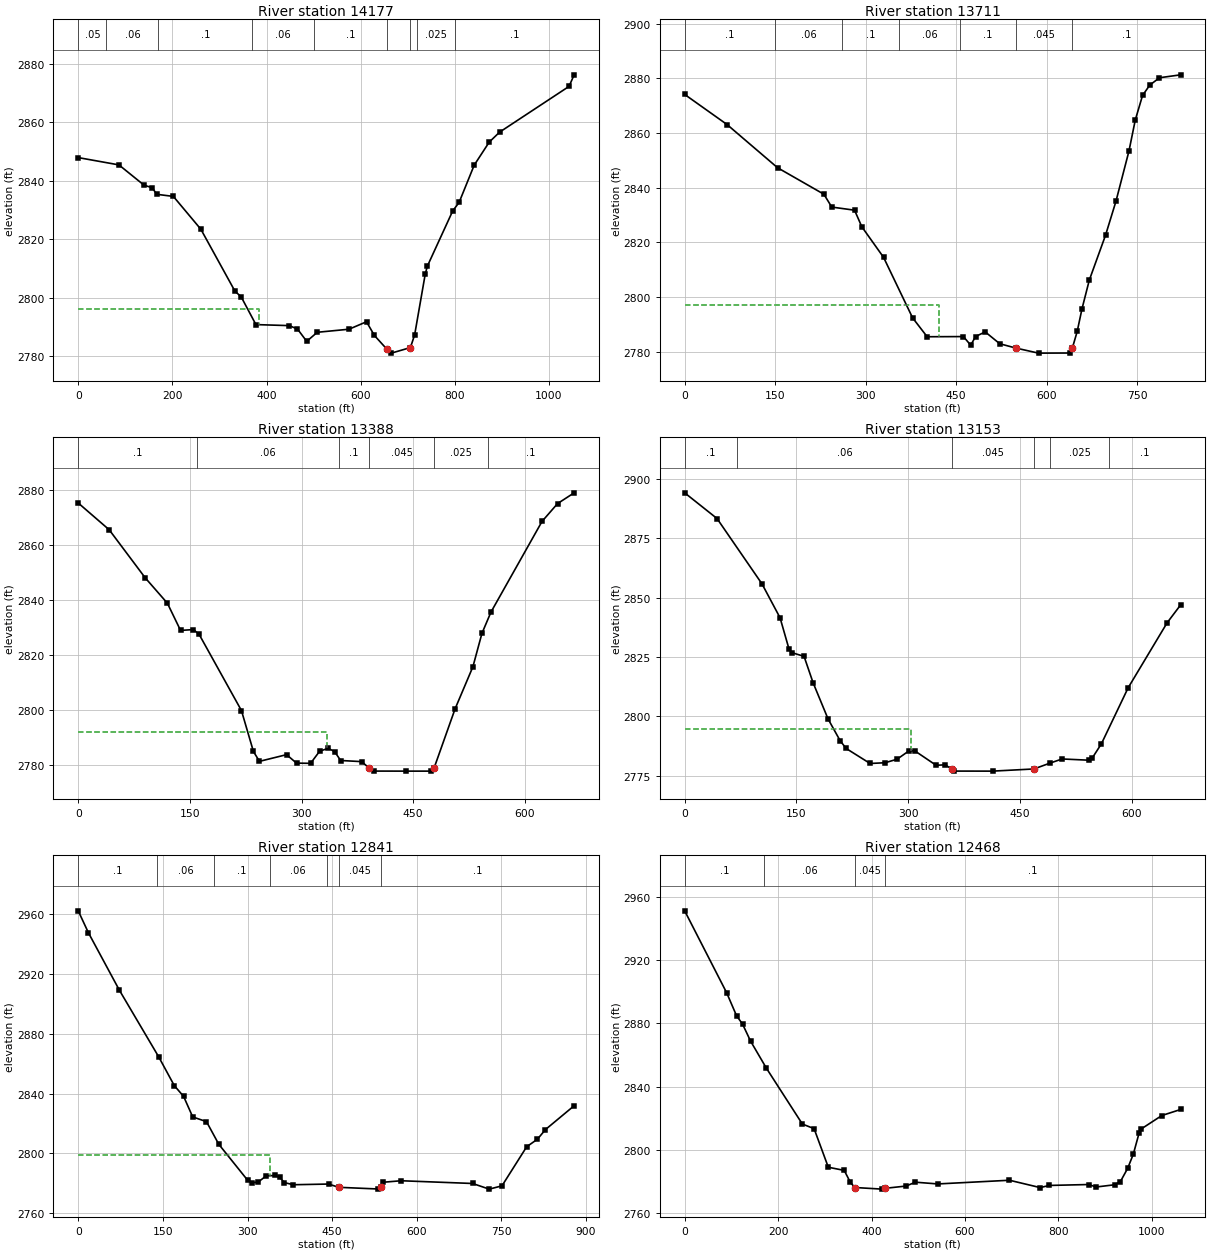
Type RM Length L Ch R = 1 ,14177   ,443.3,466.5,486.7
XS GIS Cut Line= 3
2303660.82697454572501.0065304432303276.23969299571751.554392038
2303138.18272012571591.802752009
#Sta/Elev= 30
       0 2847.87    86.5 2845.37     140 2838.41   157.2 2837.57   166.7 2835.31
   202.1 2834.59   260.6 2823.34   333.1 2802.13     346 2800.28   377.5 2790.74
   448.3 2790.39   465.8 2789.22   485.4 2785.01   507.8 2788.11   575.3 2789.16
   612.4 2791.71   629.2 2787.02   656.2 2782.23   665.2 2780.98   705.7 2782.88
   714.7 2787.25   737.1 2807.96   741.6  2810.7   795.6 2829.65   809.1 2832.53
   841.2 2845.29   873.1 2853.17   895.1 2856.57  1042.6 2872.22  1053.5 2876.18
#Mann= 9 ,-1,0
       0     .05       0      60     .06       0     170      .1       0
     370     .06       0     500      .1       0   656.2    .045       0
   705.7      .1       0     720    .025       0     800      .1       0
#XS Ineff= 2 , 0
          384.72  2796.1
Permanent Ineff=
       F       F
Bank Sta=656.2,705.7
XS Rating Curve= 0 ,0
Exp/Cntr(USF)=0,0
Exp/Cntr=0.3,0.1

Type RM Length L Ch R = 1 ,13711   ,317.9,322.5,326.6
XS GIS Cut Line= 3
2303884.78196123572489.9561189132303782.14936853572245.140863548
2303822.36245831571690.300301988
#Sta/Elev= 30
       0 2874.11    70.2 2863.11   153.9 2847.32   230.7 2837.63   243.7 2832.94
   281.5  2831.8   293.5 2825.75   329.6 2814.55   377.7 2792.44   401.8 2785.54
   461.9  2785.6     474 2782.44     482 2785.62     498 2787.31   522.1 2782.98
   548.6 2781.41   586.3 2779.55   638.4 2779.59   642.4 2781.39   650.4 2787.46
   658.4 2795.77   670.5 2806.25   697.4 2822.66   714.6 2835.02   736.2 2853.42
   746.7  2864.8   758.7 2873.73   770.7 2877.53   786.8 2880.21   821.8 2881.28
#Mann= 7 ,-1,0
       0      .1       0     150     .06       0     260      .1       0
  355.46     .06       0  455.46      .1       0   548.6    .045       0
   642.4      .1       0
#XS Ineff= 2 , 0
          421.93 2797.22
Permanent Ineff=
       F       F
Bank Sta=548.6,642.4
XS Rating Curve= 0 ,0
Exp/Cntr(USF)=0,0
Exp/Cntr=0.3,0.1

Type RM Length L Ch R = 1 ,13388   ,238.2,235.6,234.7
XS GIS Cut Line= 2
2304062.12361464572406.347322761   2304154.64857571746.498299019
#Sta/Elev= 30
       0  2875.3    41.6 2865.58      90 2848.12   119.8  2838.9   137.5 2829.01
   154.7 2829.32   162.3 2827.65   219.3 2799.91   235.4 2785.04   243.5 2781.46
   279.9 2783.89   293.3 2780.82   312.2 2780.74   324.3 2785.12   335.8  2786.2
   344.5    2785   352.6 2781.77   380.9 2781.36   390.62779.075     397 2777.93
   440.6 2777.91   473.8 2777.91   478.1 2779.01   506.3 2800.51   530.3 2815.84
   542.4 2827.94   554.5 2835.65   623.2 2868.63     644 2875.08   666.3 2878.99
#Mann= 6 ,-1,0
       0      .1       0     160     .06       0     350      .1       0
   390.6    .045       0   478.1    .025       0     550      .1       0
#XS Ineff= 2 , 0
          334.42 2792.11
Permanent Ineff=
       F       F
Bank Sta=390.6,478.1
XS Rating Curve= 0 ,0
Exp/Cntr(USF)=0,0
Exp/Cntr=0.3,0.1

Type RM Length L Ch R = 1 ,13153   ,316.6,311.2,315.8
XS GIS Cut Line= 3
2304307.47451928572424.2897466482304376.34371984571835.458081847
2304369.45679978571763.145421257
#Sta/Elev= 30
       0  2894.1    43.4 2883.28   103.8 2855.75     128  2841.5   140.1 2828.24
   144.1 2826.81   160.2 2825.27   172.3 2814.18   192.4 2798.93   208.5 2789.84
   216.6 2786.52   248.8 2780.19   268.9  2780.5     285 2781.98   301.1 2785.53
   309.2 2785.42   337.4 2779.43   349.5 2779.62   358.5 2777.83   361.6 2776.99
   413.2 2776.97   468.6 2777.88   490.2 2780.34   506.5 2782.09   542.8 2781.56
   546.8 2782.43   559.2 2788.47   595.1 2812.05   647.4 2839.41   665.5 2846.93
#Mann= 6 ,-1,0
       0      .1       0      70     .06       0   358.5    .045       0
   468.6      .1       0   490.2    .025       0     570      .1       0
#XS Ineff= 2 , 0
          304.06 2794.82
Permanent Ineff=
       F       F
Bank Sta=358.5,468.6
XS Rating Curve= 0 ,0
Exp/Cntr(USF)=0,0
Exp/Cntr=0.3,0.1

Type RM Length L Ch R = 1 ,12841   ,396.3,373.3,345.7
XS GIS Cut Line= 4
2304583.18520535572489.1328091342304677.37745704 571946.12502782
2304689.11335429571870.5394437272304477.30732084571735.520833683
#Sta/Elev= 30
       0 2962.27    18.1 2947.58      73 2909.11   142.7 2864.49   170.3 2845.25
   186.7  2838.1   202.9 2824.32   227.3 2821.16   249.2 2805.96   300.4 2781.86
   308.5 2780.32   319.1 2780.75   332.9 2784.85   349.1 2785.15   357.2 2783.85
   365.3 2780.35   381.4 2778.94   443.6  2779.4   461.72777.216   531.8 2776.08
   535.8 2777.34   540.5 2780.61   572.3 2781.61   698.8 2779.78   728.3    2776
   750.9  2778.2   794.7 2804.37   813.7  2809.4     828 2815.88   878.8 2831.82
#Mann= 7 ,-1,0
       0      .1       0     140     .06       0     240      .1       0
     340     .06       0     440      .1       0   461.7    .045       0
   535.8      .1       0
#XS Ineff= 2 , 0
          339.72 2798.68
Permanent Ineff=
       F       F
Bank Sta=461.7,535.8
XS Rating Curve= 0 ,0
Exp/Cntr(USF)=0,0
Exp/Cntr=0.3,0.1

Type RM Length L Ch R = 1 ,12468   ,500.5,441.2,372.7
XS GIS Cut Line= 4
2305167.98165803572409.3835431462304995.88047624571945.487332458
2304860.07364412571716.708863163 2304559.3745348571716.681227125
#Sta/Elev= 30
       0 2951.44    89.8 2899.49   111.1 2884.84   123.9 2879.58     141 2868.81
   175.1 2851.52   251.9 2816.18     277 2813.26   307.4 2788.79   341.5 2786.78
   354.3 2779.37   364.1 2775.93   422.6  2774.9   429.5 2775.43   473.8 2776.85
   493.9  2779.3   541.7 2778.19   695.2 2780.53   760.8 2775.88   780.7 2777.24
   864.7 2777.82   880.7 2776.25   920.7 2777.68   932.7 2779.73   948.3 2788.17
   960.3 2797.12   972.7 2810.56   976.7 2812.98  1021.2 2821.58  1061.5 2825.42
#Mann= 4 ,-1,0
       0      .1       0     170     .06       0   364.1    .045       0
   429.5      .1       0
Bank Sta=364.1,429.5
XS Rating Curve= 0 ,0
Exp/Cntr(USF)=0,0
Exp/Cntr=0.3,0.1

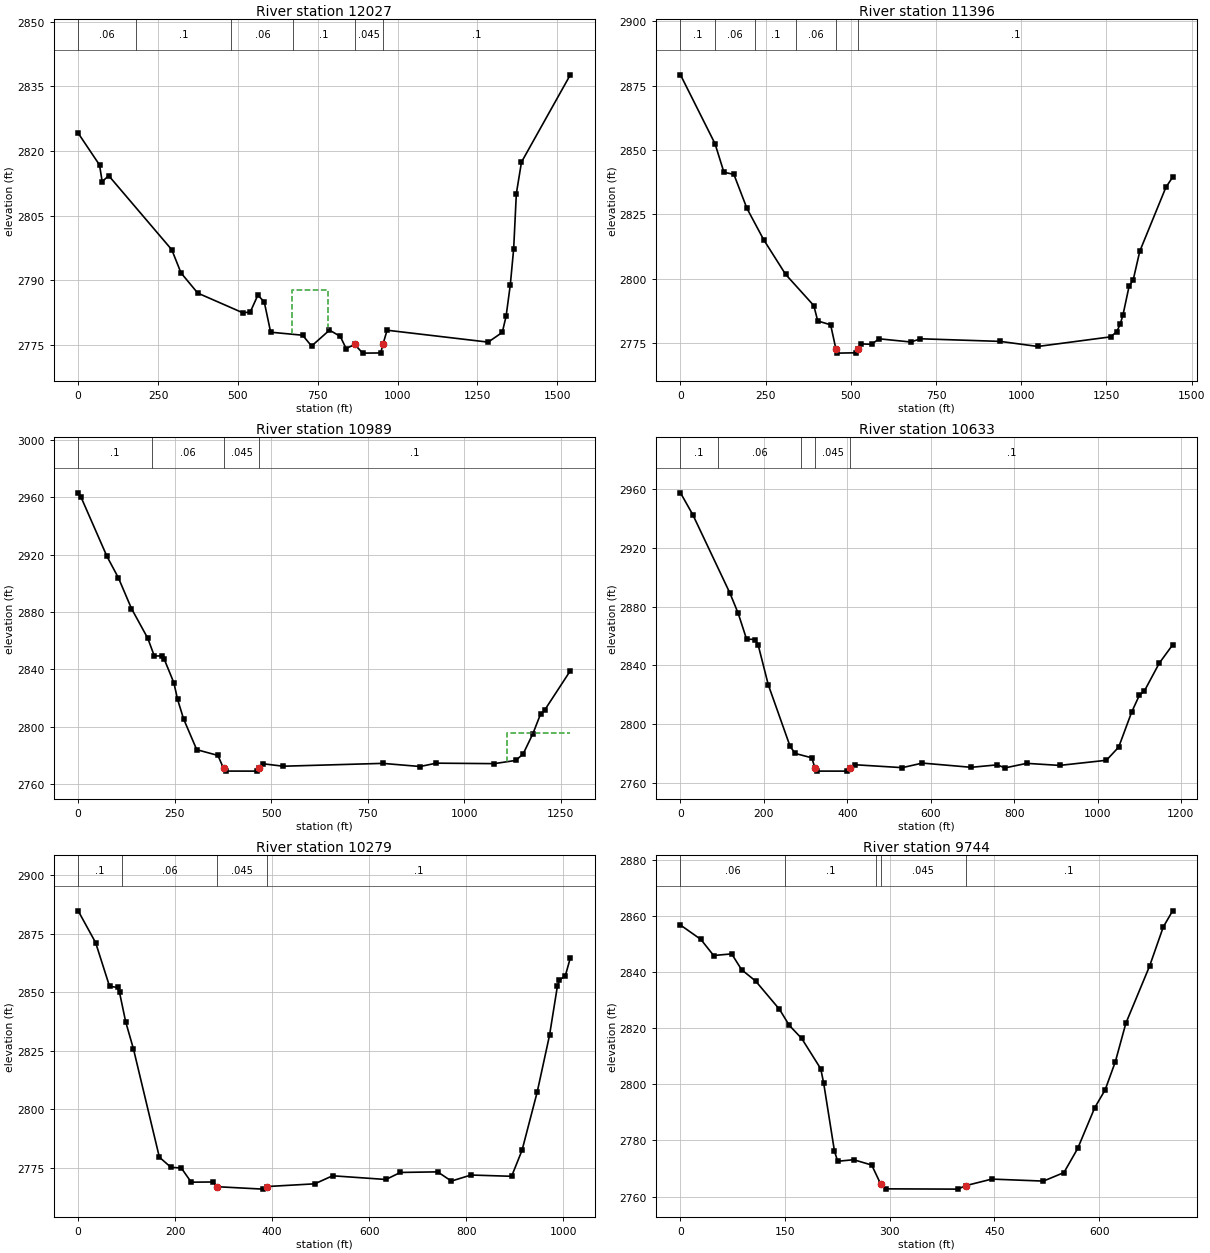
Type RM Length L Ch R = 1 ,12027   ,657.5,631,613.9
XS GIS Cut Line= 4
2306021.23506787571534.4444288792305551.24093857571647.824258069
2305252.77369807  571661.27794542304495.52998448571707.540423079
#Sta/Elev= 30
       0 2824.15    66.9 2816.77    75.2 2812.91    95.7 2814.28   293.2 2797.11
     322 2791.75   374.4 2787.07   514.6 2782.53   538.6 2782.64   562.6 2786.58
   582.6 2785.04   602.7    2778   702.8  2777.3   730.8 2774.79   786.9 2778.48
   820.5 2777.04     839 2774.22   865.8 2775.15     891 2773.15   947.2 2773.19
  954.38 2775.22   967.2 2778.46  1283.8  2775.7  1327.9 2777.96  1339.9 2781.74
    1353 2788.99  1363.5 2797.29  1371.9 2810.12    1388 2817.43  1540.9 2837.66
#Mann= 6 ,-1,0
       0     .06       0     180      .1       0     480     .06       0
  673.48      .1       0   865.8    .045       0  954.38      .1       0
#XS Ineff= 1 ,-1
  669.75  782.42 2787.85
Permanent Ineff=
       F
Bank Sta=865.8,954.38
XS Rating Curve= 0 ,0
Exp/Cntr(USF)=0,0
Exp/Cntr=0.3,0.1

Type RM Length L Ch R = 1 ,11396   ,440.4,406.6,380.4
XS GIS Cut Line= 3
2305635.04785574570782.2908694932305009.28697344571227.871575562
2304505.26945347571678.322016124
#Sta/Elev= 30
       0 2879.24   101.5 2852.42   127.5 2841.35   156.7 2840.54     195 2827.32
   244.1 2815.14   308.4 2801.67   391.2 2789.52   402.8 2783.54   440.6 2782.04
  455.84  2772.8   460.2 2771.03   514.2 2771.16  520.99 2772.82   528.9 2774.62
   560.6 2774.47     583  2776.6   676.3 2775.35     704 2776.61   938.2 2775.59
  1048.6 2773.62  1262.4 2777.36  1280.4 2779.42  1290.1 2782.22  1298.4 2785.85
  1316.4 2797.02  1328.4 2799.48  1347.8 2810.66  1424.4  2835.5  1444.2 2839.45
#Mann= 6 ,-1,0
       0      .1       0     100     .06       0     220      .1       0
     340     .06       0  455.84    .045       0  520.99      .1       0
Bank Sta=455.84,520.99
XS Rating Curve= 0 ,0
Exp/Cntr(USF)=0,0
Exp/Cntr=0.3,0.1

Type RM Length L Ch R = 1 ,10989   ,376.6,356,327.6
XS GIS Cut Line= 3
2304999.85478537570510.4007003352304703.08439654571384.412828764
2304468.74644477571646.668741922
#Sta/Elev= 30
       0    2963     7.2 2960.15    74.7 2918.67   104.3 2903.76   138.1 2882.38
   180.4 2861.62   197.3 2849.31   218.4 2849.42   222.6 2847.32   247.9 2830.69
   257.4 2819.16   273.1 2805.48   307.1 2784.07     362 2780.06  376.59 2771.01
   383.5 2769.16   463.4 2769.12  469.38 2771.01   478.1 2774.27     531 2772.54
   788.7 2774.52   885.8 2772.34   927.4 2774.67  1077.5 2774.33  1133.3 2776.58
  1152.3 2780.98  1177.8 2795.23  1197.6 2808.86  1208.4  2811.7  1274.7 2839.03
#Mann= 4 ,-1,0
       0      .1       0     190     .06       0  376.59    .045       0
  469.38      .1       0
#XS Ineff= 2 , 0
                         1111.63         2795.36
Permanent Ineff=
       F       F
Bank Sta=376.59,469.38
XS Rating Curve= 0 ,0
Exp/Cntr(USF)=0,0
Exp/Cntr=0.3,0.1

Type RM Length L Ch R = 1 ,10633   ,362.4,354.6,345.4
XS GIS Cut Line= 3
2304485.98375043570499.3101946572304542.76391941571167.312182662
2304405.82351187571658.293643846
#Sta/Elev= 30
       0 2957.47    29.7 2942.49   118.5 2889.18   138.4 2875.38   158.4 2857.86
   178.5 2857.54   186.5 2853.57   210.6 2826.65   262.8 2784.79   274.9 2779.93
     315 2776.92   322.2 2770.12     327 2767.89   399.3 2767.87   407.3 2769.84
   419.4  2772.2   531.8 2770.24     580 2773.35   697.3 2770.47   759.6 2772.15
   777.9 2770.06   830.2 2773.16   909.1 2771.77  1021.2 2775.26  1050.7 2784.22
    1082  2808.2  1100.1 2819.42  1112.5 2822.56  1148.1 2841.46  1180.1 2853.89
#Mann= 5 ,-1,0
       0      .1       0      90     .06       0     290      .1       0
   322.2    .045       0   407.3      .1       0
Bank Sta=322.2,407.3
XS Rating Curve= 0 ,0
Exp/Cntr(USF)=0,0
Exp/Cntr=0.3,0.1

Type RM Length L Ch R = 1 ,10279   ,462.6,534.4,583.3
XS GIS Cut Line= 3
2304093.77688884570602.1106932682304242.30379087 571242.48077904
2304188.73671145 571595.53652975
#Sta/Elev= 30
       0 2884.68      36 2871.12    64.7  2852.5    81.2 2852.03    85.3 2849.88
    97.9 2837.42     114 2825.79   167.4 2779.65   191.2 2775.34   212.6 2775.03
   233.1 2768.99   278.3 2769.08   286.5 2767.06   380.9 2766.03   389.1 2767.13
   487.7 2768.29   524.5 2771.72   634.5 2770.14   664.1 2773.14     741 2773.39
   769.3 2769.46   809.8 2772.04   893.5  2771.5     915 2782.61   946.1 2807.31
   971.6 2831.58   987.8 2852.46   991.9 2855.22    1004 2856.84  1014.5  2864.6
#Mann= 4 ,-1,0
       0      .1       0      90     .06       0   286.5    .045       0
   389.1      .1       0
Bank Sta=286.5,389.1
XS Rating Curve= 0 ,0
Exp/Cntr(USF)=0,0
Exp/Cntr=0.3,0.1

Type RM Length L Ch R = 1 ,9744    ,472.1,504.9,537.5
XS GIS Cut Line= 2
2303874.63883668570553.413348343 2303465.5811393571128.042018465
#Sta/Elev= 30
       0 2856.68    29.2 2851.57    47.5 2845.84    73.4 2846.41    87.6 2840.79
   107.7 2836.75   141.9 2826.68     156 2820.96   173.7 2816.33     201 2805.54
   205.2 2800.49   220.7 2776.22   225.3 2772.61   248.3 2773.15   274.1 2771.26
     287 2764.47   294.2 2762.79   397.4 2762.69   408.9 2763.93   446.2 2766.26
   520.2 2765.55   549.6 2768.58   569.3 2777.16   593.8  2791.7   608.6 2797.99
   623.3 2808.05   638.3  2821.7   672.4  2842.1     692 2856.01   705.4 2861.74
#Mann= 5 ,-1,0
       0     .06       0     150      .1       0     280     .06       0
     287    .045       0   408.9      .1       0
Bank Sta=287,408.9
XS Rating Curve= 0 ,0
Exp/Cntr(USF)=0,0
Exp/Cntr=0.3,0.1

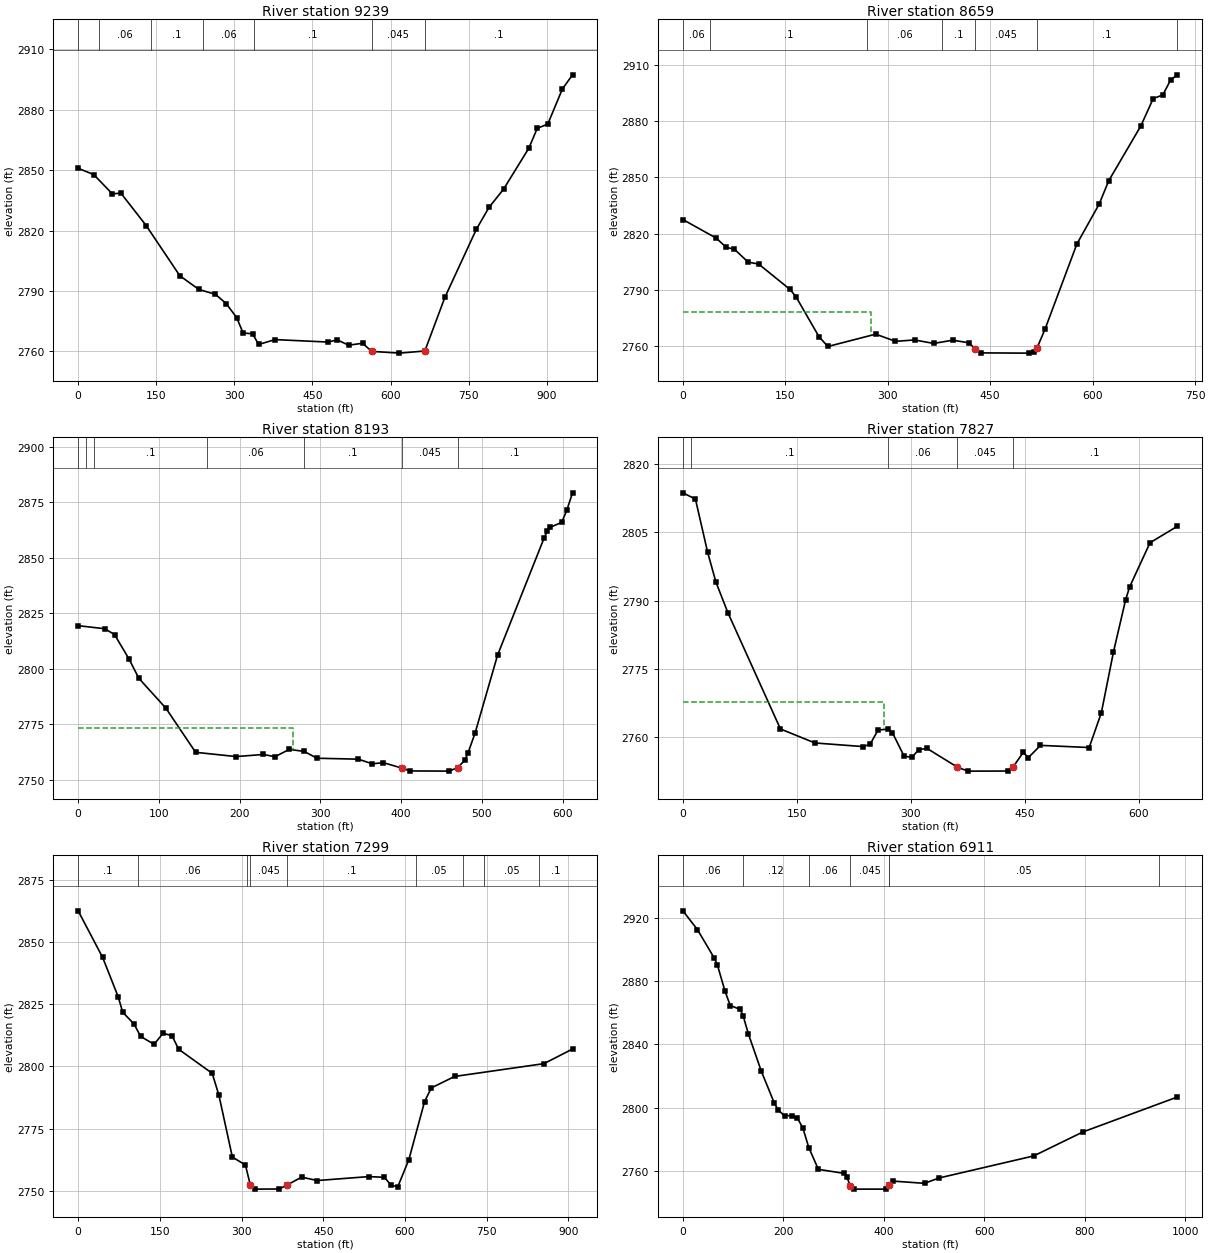
Type RM Length L Ch R = 1 ,9239    ,515.1,580.7,640
XS GIS Cut Line= 4
2303821.15988463570425.1412828962303497.23441351570475.497596462
 2303170.9622025570631.329100224 2302912.8662744570662.982374425
#Sta/Elev= 30
       0 2850.91    29.9 2847.81    65.8 2838.19      82 2838.61   130.6 2822.49
   195.3 2797.53   231.7 2790.75   263.7 2788.29   284.4 2783.69   304.6 2776.67
   316.7 2769.12     335 2768.68   346.7 2763.39   378.1 2765.81   480.2 2764.59
   497.4 2765.68   519.6 2763.03   546.2    2764   563.7 2759.96   617.1 2759.09
   665.8 2760.15   704.2 2786.75   764.7 2820.62   788.9 2831.46   817.1  2840.6
   865.5 2860.92   881.6 2870.78   901.8 2872.87     930 2890.37   949.4 2897.36
#Mann= 7 ,-1,0
       0      .1       0      40     .06       0     140      .1       0
     240     .06       0  337.82      .1       0   563.7    .045       0
   665.8      .1       0
Bank Sta=563.7,665.8
XS Rating Curve= 0 ,0
Exp/Cntr=0.3,0.1

Type RM Length L Ch R = 1 ,8659    ,447.8,465.9,481.5
XS GIS Cut Line= 2
2303719.37532754570277.0768139112303097.91618512569905.738660833
#Sta/Elev= 30
       0 2827.46    48.9 2817.55    63.5 2812.61    75.2 2811.71    95.6 2804.74
   110.9 2803.75   156.9 2790.18   165.6 2786.27   199.4 2764.91   212.3 2759.76
   282.3 2766.34   311.3 2762.51   339.2 2763.25   367.2 2761.39   395.1 2763.12
   418.4 2761.75   427.8 2758.68   436.9 2756.34   506.7 2756.22   514.5  2756.7
   518.5 2758.92   530.3 2769.05   576.9 2814.44   609.5 2835.69   623.5 2848.15
   670.5 2877.37   688.7 2892.05   702.7 2893.92     714 2901.83   723.9 2904.68
#Mann= 7 ,-1,0
       0     .06       0      40      .1       0     270     .06       0
     380      .1       0   427.8    .045       0   518.5      .1       0
  723.95     .06       0
#XS Ineff= 2 , 0
          275.38 2777.99
Permanent Ineff=
       F       F
Bank Sta=427.8,518.5
XS Rating Curve= 0 ,0
Exp/Cntr=0.3,0.1

Type RM Length L Ch R = 1 ,8193    ,371.4,365.4,358.8
XS GIS Cut Line= 2
2303894.11777465570000.6984834382303487.49494452569542.943441137
#Sta/Elev= 30
       0 2819.37      33    2818    45.1 2815.36    63.2 2804.23    75.2 2795.65
   108.7 2782.17   145.5 2762.29   195.7 2760.37   229.4 2761.32   243.8 2760.31
   261.5 2763.61     280 2762.69   295.7 2759.62   347.1  2759.2   364.3  2757.1
   377.9 2757.64   400.5 2755.22   411.3  2753.9   459.5 2753.81   470.2 2755.43
   478.7 2758.66   482.7 2761.86   491.6 2770.97   519.5 2806.15   577.2 2858.98
   581.1 2862.13   584.7 2863.73   598.9 2865.94   605.2 2871.43   612.3 2879.26
#Mann= 7 ,-1,0
       0     .06       0      10     .07       0      20      .1       0
     160     .06       0     280      .1       0   400.5    .045       0
   470.2      .1       0
#XS Ineff= 2 , 0
           265.8 2773.07
Permanent Ineff=
       F       F
Bank Sta=400.5,470.2
XS Rating Curve= 0 ,0
Exp/Cntr(USF)=0,0
Exp/Cntr=0.3,0.1

Type RM Length L Ch R = 1 ,7827    ,574.1,528.6,481.4
XS GIS Cut Line= 2
2304180.50588621569702.1572189912303693.26338412569270.827790914
#Sta/Elev= 30
       0 2813.71    16.5 2812.33    32.5 2800.67    43.4 2794.11    59.2 2787.36
   128.4 2761.79   173.8 2758.72   236.8 2757.93   246.2  2758.4   256.9 2761.56
   270.1 2761.77   275.8 2760.96   291.1 2755.83   301.3 2755.55   310.3 2757.23
     321 2757.55   360.8 2753.45     375 2752.53   427.8 2752.55   434.5 2753.42
     448 2756.68   454.5 2755.47   470.6 2758.19   534.7 2757.72   550.7 2765.34
   566.7 2778.74   582.7 2790.22   588.1 2793.08   614.8 2802.74   650.7 2806.35
#Mann= 5 ,-1,0
       0     .06       0      10      .1       0     270     .06       0
   360.8    .045       0   434.5      .1       0
#XS Ineff= 2 , 0
          264.62 2767.68
Permanent Ineff=
       F       F
Bank Sta=360.8,434.5
XS Rating Curve= 0 ,0
Exp/Cntr(USF)=0,0
Exp/Cntr=0.3,0.1

Type RM Length L Ch R = 1 ,7299    ,418.9,388.1,352.7
XS GIS Cut Line= 3
2304484.03400226568928.9592812542303845.02744215 569075.93079008
2303667.70312172569254.852626912
#Sta/Elev= 30
       0 2862.52      45  2843.8    73.5    2828    81.9 2821.76   102.5 2817.11
   114.8 2812.07   139.4 2808.92   155.8 2813.31   172.2 2812.41   184.6 2806.91
   246.1 2797.26   258.4 2788.49   283.1 2763.64   307.1 2760.42   315.9 2752.59
   324.1 2750.75   369.3  2750.8   383.3 2752.39   410.3 2755.56     439  2754.2
   533.4 2755.78   562.2  2755.5   574.5 2752.33   586.8  2751.7   607.2 2762.63
     636 2785.93   648.4  2791.4   691.1    2796   855.2 2801.15   907.6 2807.02
#Mann= 9 ,-1,0
       0      .1       0     110     .06       0     310      .1       0
   315.9    .045       0   383.3      .1       0     620     .05       0
  705.69      .1       0  745.69     .05       0  845.69      .1       0
Bank Sta=315.9,383.3
XS Rating Curve= 0 ,0
Exp/Cntr(USF)=0,0
Exp/Cntr=0.3,0.1

Type RM Length L Ch R = 1 ,6911    ,361.3,336.8,303.2
XS GIS Cut Line= 3
  2304143.763009568424.1440987642303702.84848252 568965.70215846
2303643.74037571 569245.26752851
#Sta/Elev= 30
       0 2924.43    28.9 2912.57    62.7 2894.43    68.7 2890.16    83.9 2873.57
    94.2  2864.6   114.2 2862.12     120 2857.95   130.3 2846.69   156.1 2823.05
   181.9    2803   189.4 2798.64   202.3 2794.93     218 2795.05   227.9 2793.41
   238.6 2787.35   250.6 2774.82   269.6 2761.05   321.1 2758.51   326.3 2756.22
   333.1 2750.74   341.5 2748.56   403.7 2748.56   409.9 2750.89   418.4 2753.63
   480.9 2752.22   509.6 2755.58   698.3 2769.54   795.9 2784.65   984.1 2806.77
#Mann= 7 ,-1,0
       0     .06       0     120     .12       0     250     .06       0
   333.1    .045       0   409.9      .1       0     410     .05       0
  948.35      .1       0
Bank Sta=333.1,409.9
XS Rating Curve= 0 ,0
Exp/Cntr(USF)=0,0
Exp/Cntr=0.3,0.1

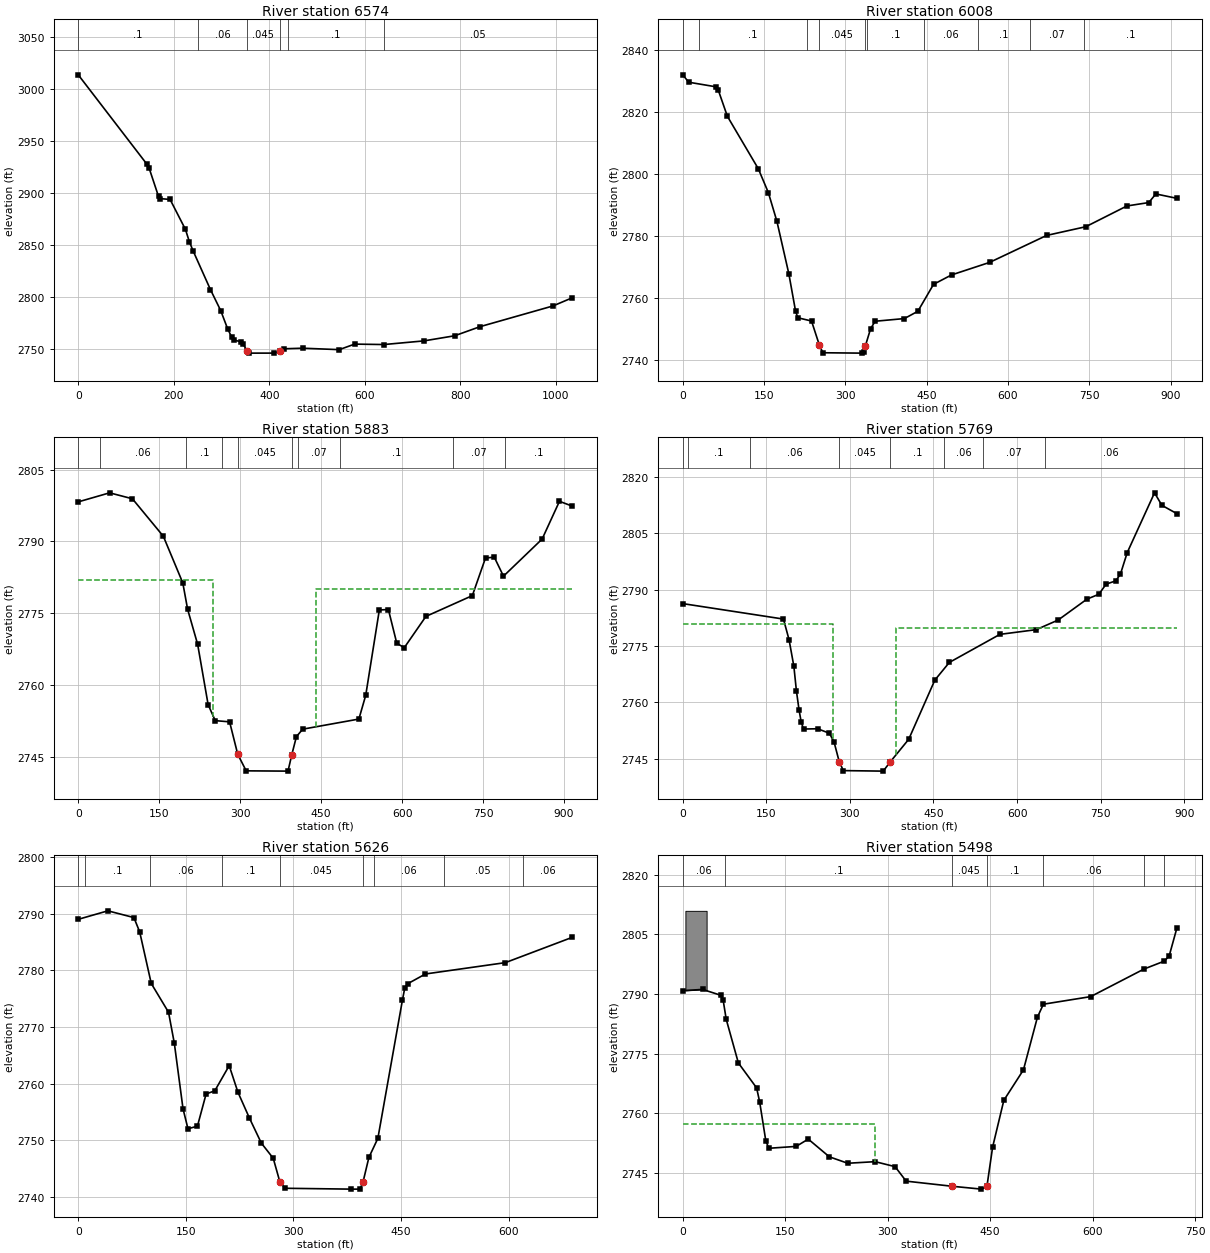
Type RM Length L Ch R = 1 ,6574    ,583.9,565.9,544.3
XS GIS Cut Line= 3
2303662.91057252 568178.12657312 2303571.8521377568986.469871664
2303499.96389969569195.744520101
#Sta/Elev= 30
       0 3013.42     144 2927.46     148 2924.41   168.1 2896.64   172.1 2894.54
   192.3 2893.77   224.5 2864.94   232.5 2853.38   240.4 2844.48   276.8  2807.2
   298.3 2787.04     313 2769.29   321.1 2761.82   325.1 2758.79   341.2 2757.12
   345.3 2755.18   353.3 2748.09   357.3 2746.21   409.6 2746.23   422.2 2748.36
   429.8 2750.37     470 2750.94   546.5 2749.55   578.7 2754.87     640 2754.45
   723.6 2757.95     788 2762.86   841.7 2771.68     994 2791.51  1034.7 2799.42
#Mann= 6 ,-1,0
       0      .1       0     250     .06       0   353.3    .045       0
   422.2     .06       0     440      .1       0     640     .05       0
Bank Sta=353.3,422.2
XS Rating Curve= 0 ,0
Exp/Cntr(USF)=0,0
Exp/Cntr=0.3,0.1

Type RM Length L Ch R = 1 ,6008    ,141.2,125.4,113.5
BEGIN DESCRIPTION:
xs 4
END DESCRIPTION:
XS GIS Cut Line= 4
2303011.97138906568494.6773442032303121.55017217568842.168415335
2303181.38954465569069.7340708162303162.88793923569381.056422534
#Sta/Elev= 30
       0 2831.97      11 2829.59    61.3 2828.11    65.5 2827.05    82.3 2818.61
   139.3 2801.73   157.8 2794.07   173.6 2784.83   195.6 2767.95   208.1 2755.83
   212.3 2753.73   237.5 2752.68  251.97 2744.93   258.5 2742.46   329.8 2742.34
     334 2742.78     337 2744.77   346.5 2750.22   354.9 2752.61   408.8 2753.47
   433.6 2755.81   462.6  2764.5   495.7 2767.52     566 2771.56   671.2 2780.25
   743.4 2783.05   819.3 2789.74   859.6 2790.83   872.6 2793.61   911.5 2792.19
#Mann= 10 ,-1,0
       0     .06       0      30      .1       0     230     .06       0
  251.97    .045       0     337     .06       0     340      .1       0
  444.36     .06       0  544.36      .1       0  639.66     .07       0
  739.66      .1       0
Bank Sta=251.97,337
XS Rating Curve= 0 ,0
Exp/Cntr(USF)=0,0
Exp/Cntr=0.5,0.3

Type RM Length L Ch R = 1 ,5883    ,103,114,128.2
BEGIN DESCRIPTION:
xs 3
END DESCRIPTION:
XS GIS Cut Line= 6
2302818.76194781568482.9789328952303016.73624844568869.144776401
2303049.45847097 568953.640806562303112.27466229 569149.18153114
2303124.66527863 569211.412917772303132.53512762569333.130930525
#Sta/Elev= 30
       0 2798.26    58.1 2800.15   100.3 2798.91   157.6 2791.09   193.7 2781.34
   202.6 2775.85   221.2 2768.52   240.6 2755.94   253.8 2752.59   280.4 2752.34
   295.4 2745.59   311.1 2742.11   388.6 2742.05   395.5 2745.42   404.2 2749.26
   415.9 2750.81   519.9 2752.92   532.6 2757.88   557.8 2775.69   574.6 2775.79
   590.1 2768.75     604 2767.82   644.1 2774.35   730.1 2778.69   754.5 2786.55
   770.8 2786.71   787.8 2782.75   859.4  2790.5   891.5 2798.38   915.5 2797.36
#Mann= 10 ,-1,0
       0      .1       0      40     .06       0     200      .1       0
   267.1     .06       0   295.4    .045       0   395.5     .06       0
   407.1     .07       0  484.07      .1       0  694.68     .07       0
  790.06      .1       0
#XS Ineff= 2 , 0
           250.5 2781.85   440.5         2779.99
Permanent Ineff=
       F       F
Bank Sta=295.4,395.5
XS Rating Curve= 0 ,0
Exp/Cntr(USF)=0,0
Exp/Cntr=0.5,0.3

Type RM Length L Ch R = 1 ,5769    ,141.1,142.9,144.9
BEGIN DESCRIPTION:
xs 2
END DESCRIPTION:
XS GIS Cut Line= 6
2302734.75354395568508.8124679792302822.61694597568694.124370412
 2302898.3979888568926.6175601462302979.28697319569121.750026995
2303024.95498345569232.2562443052303046.58032135 569336.56142934
#Sta/Elev= 30
       0  2786.3   180.7 2782.19   190.8 2776.68   199.4 2769.63     204 2763.06
   208.7 2758.03   212.5 2754.85   216.7 2752.94     242 2753.01     263 2751.83
   271.4 2749.57   280.82744.252   288.2 2741.88   359.8 2741.74   372.4  2744.2
   405.5  2750.2   452.4 2765.95   478.4 2770.65   569.2 2778.12   634.3 2779.37
   673.7 2781.93   725.4 2787.49   746.8 2788.79   759.8 2791.48   777.1 2792.35
   785.5 2794.14   797.7 2799.87   846.7 2815.77   859.9 2812.45   886.9 2810.22
#Mann= 8 ,-1,0
       0     .07       0      10      .1       0     120     .06       0
   280.8    .045       0   372.4      .1       0  469.62     .06       0
  539.62     .07       0  649.62     .06       0
#XS Ineff= 2 , 0
           270.4    2781   382.8          2779.9
Permanent Ineff=
       F       F
Bank Sta=280.8,372.4
XS Rating Curve= 0 ,0
Exp/Cntr(USF)=0,0
Exp/Cntr=0.5,0.3

Type RM Length L Ch R = 1 ,5626    ,119.5,128.1,131.9
BEGIN DESCRIPTION:
xs 1
END DESCRIPTION:
XS GIS Cut Line= 4
2302725.24194288568516.128857708 2302696.4366665568756.911424337
2302762.91038122568984.399248023 2302836.0314674569180.866004843
#Sta/Elev= 30
       0 2789.03    41.3 2790.53    77.6 2789.34    85.7  2786.8   101.8  2777.7
   125.9 2772.62     134 2767.13   146.1 2755.57     153 2752.04   166.2  2752.5
   178.3 2758.19   190.4 2758.74   210.5 2763.19   222.6 2758.52   238.7 2753.93
   255.3 2749.51   271.9 2746.83   281.2 2742.64   288.6 2741.53   380.3 2741.38
   392.8 2741.38     397 2742.58   405.3 2746.98   417.8 2750.34   452.1 2774.79
   455.3 2776.88   459.5 2777.66   484.2 2779.38   595.6 2781.38   689.1 2785.86
#Mann= 9 ,-1,0
       0     .07       0      10      .1       0     100     .06       0
     200      .1       0   281.2    .045       0     397      .1       0
   412.5     .06       0   509.5     .05       0   619.5     .06       0
Bank Sta=281.2,397
XS Rating Curve= 0 ,0
Exp/Cntr(USF)=0,0
Exp/Cntr=0.3,0.1

Type RM Length L Ch R = 1 ,5498    ,242.5,400.2,453.7
XS GIS Cut Line= 5
2302709.83477187568523.9548839792302583.22492506568784.130047978
2302603.10858268568890.4613297942302625.49917748568990.644803221
2302674.81117409569208.370818189
#Sta/Elev= 30
       0 2790.85    29.1 2791.15      56 2789.66      59  2788.6    63.6 2783.64
    81.4 2772.65   108.1 2766.38   112.6 2762.83   121.5 2753.12   125.9 2751.18
     166 2751.65   183.7 2753.49   214.6 2749.03   241.5 2747.41   281.6 2747.81
   310.8 2746.56     327 2742.91   393.9 2741.63   437.2  2740.9   445.32741.623
   453.6 2751.48     470 2763.24   498.7  2770.9   519.2 2784.17   527.9 2787.43
   597.1 2789.34   675.3 2796.29   705.2 2798.29   712.1 2799.61   723.4 2806.63
#Mann= 7 ,-1,0
       0     .06       0    62.3      .1       0   393.9    .045       0
   445.3      .1       0   527.9     .06       0   675.3    .016       0
   705.2      .1       0
#XS Ineff= 2 , 0
          281.24 2757.29
Permanent Ineff=
       F       F
#Block Obstruct= 1 ,-1
    3.87   34.91 2810.93
Bank Sta=393.9,445.3
XS Rating Curve= 0 ,0
Exp/Cntr(USF)=0,0
Exp/Cntr=0.3,0.1

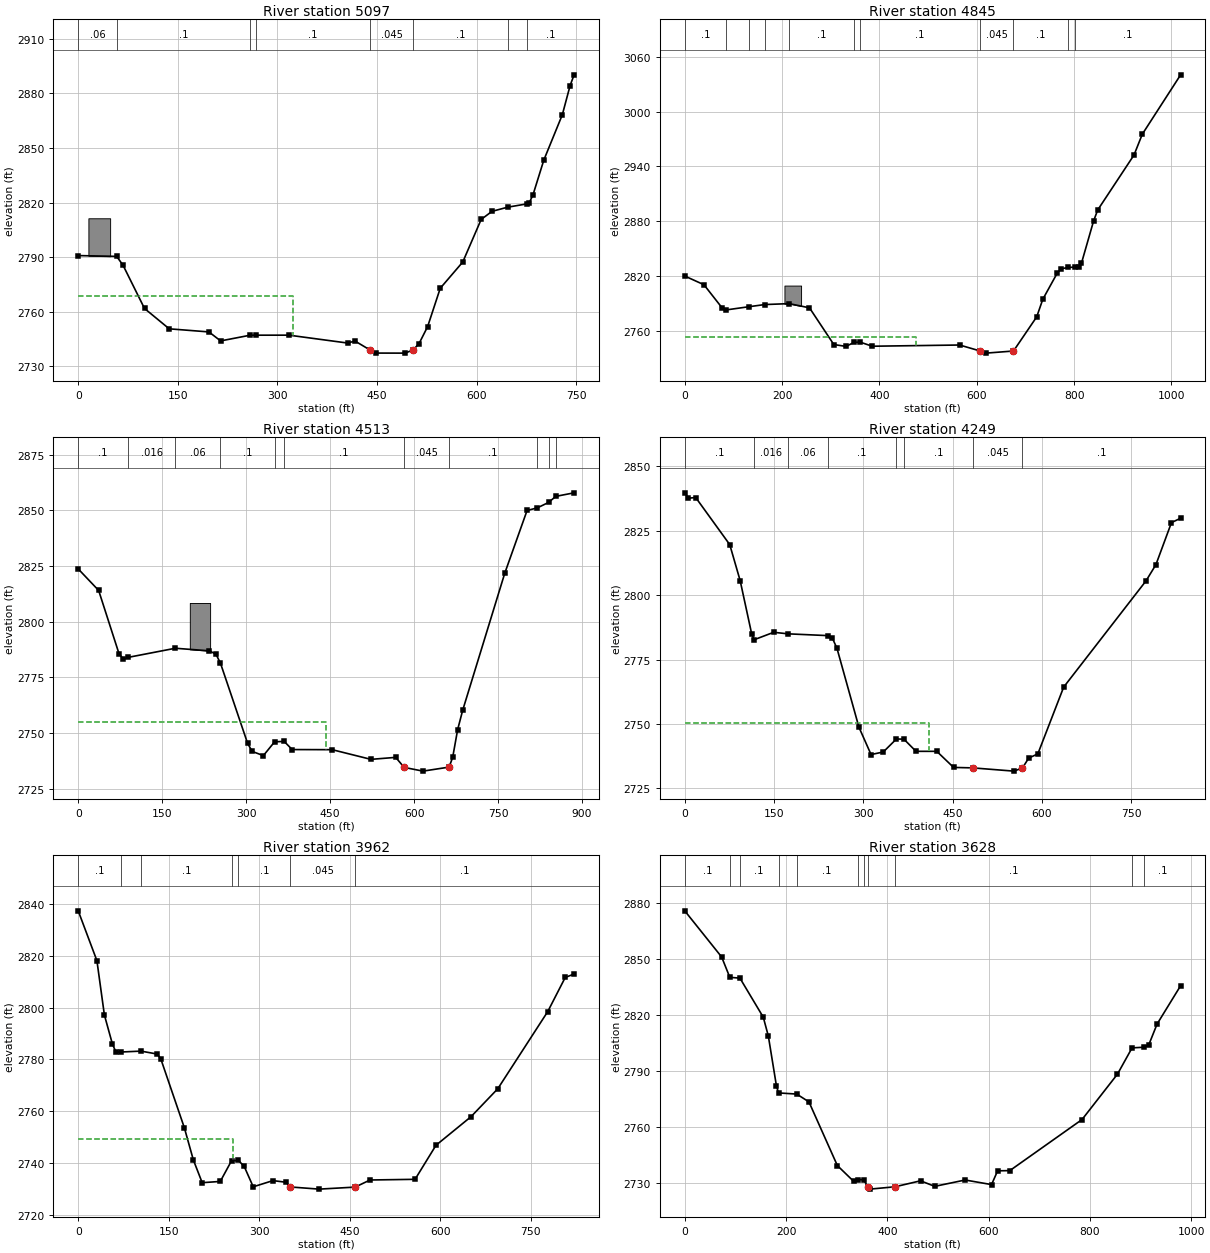
Type RM Length L Ch R = 1 ,5097    ,238.6,252.9,262.9
XS GIS Cut Line= 2
2302703.76832598568504.9248771212302052.33663831 568869.51362003
#Sta/Elev= 30
       0 2790.83    57.9 2790.38    67.5  2785.5    99.8 2761.73     137 2750.54
   196.8 2748.83   214.4 2743.89   258.5    2747   267.3 2747.04   317.3 2747.05
   405.5 2742.72   416.7 2743.81   439.6 2738.84   448.8  2737.2   491.9 2737.17
   503.8 2738.84   512.9 2742.28     526 2751.74     545 2772.85   578.9 2787.28
   606.6  2810.7   622.9 2815.15   646.5 2817.44   674.9 2819.22   678.8 2819.73
   684.7 2824.31   700.9 2843.32   728.8 2868.31   740.5 2884.34   746.5 2890.24
#Mann= 8 ,-1,0
       0     .06       0    57.9      .1       0   258.5    .016       0
   267.3      .1       0   439.6    .045       0   503.8      .1       0
   646.5    .016       0   674.9      .1       0
#XS Ineff= 2 , 0
           322.7 2768.84
Permanent Ineff=
       F       F
#Block Obstruct= 1 ,-1
   15.34   48.06 2811.34
Bank Sta=439.6,503.8
XS Rating Curve= 0 ,0
Exp/Cntr(USF)=0,0
Exp/Cntr=0.3,0.1

Type RM Length L Ch R = 1 ,4845    ,292.3,331.3,365.3
XS GIS Cut Line= 4
 2302814.0689091568320.5318847292302095.34906582568531.742763926
2301989.25928292568563.5516171212301835.98296637568605.801051954
#Sta/Elev= 30
       0 2820.03    39.5 2810.49      77    2785    85.4 2782.95   131.2 2786.38
   164.6 2788.81   214.6 2789.81   256.3 2785.22   306.3 2745.05   331.3    2743
     348 2747.43   360.5 2747.65   385.3 2743.19   564.8 2744.52   606.5 2738.06
     619 2735.64   675.5 2737.96   723.2 2775.34   735.7 2794.56     765 2822.85
   773.3 2827.93   788.2 2829.42     801 2829.77   810.9 2829.68   815.1 2833.94
   840.1 2880.34   848.5 2892.28   923.2 2952.55   940.1 2975.19  1018.9 3040.23
#Mann= 11 ,-1,0
       0      .1       0    85.4    .016       0   131.2     .06       0
   164.6    .016       0   214.6      .1       0     348    .016       0
   360.5      .1       0   606.5    .045       0   675.5      .1       0
   788.2    .016       0     801      .1       0
#XS Ineff= 2 , 0
          475.51 2753.67
Permanent Ineff=
       F       F
#Block Obstruct= 1 ,-1
  204.87  239.04 2809.58
Bank Sta=606.5,675.5
XS Rating Curve= 0 ,0
Exp/Cntr(USF)=0,0
Exp/Cntr=0.3,0.1

Type RM Length L Ch R = 1 ,4513    ,252.6,264.7,273.8
XS GIS Cut Line= 3
2302800.41938171568245.0586060552302446.15126925568288.031956974
2301968.20375659568061.635766765
#Sta/Elev= 30
       0 2823.71    36.5 2814.05    72.8 2785.67    80.8 2783.03    88.9 2783.95
   173.5 2788.06     234  2786.9     246 2785.41   254.1 2781.33   302.4 2745.44
   310.5 2741.72   330.7 2739.81   350.8 2746.02   367.9 2746.19   382.2 2742.53
   453.6 2742.48   522.8 2738.13   567.1 2739.02   582.1 2734.52   615.8 2732.84
   662.5 2734.65   668.9  2739.1   677.7 2751.49   686.6 2760.09   761.8 2821.73
   801.7 2849.97     820 2851.15   840.1 2853.59     853 2856.32   885.7 2857.91
#Mann= 11 ,-1,0
       0      .1       0    88.9    .016       0   173.5     .06       0
   254.1      .1       0   350.8    .016       0   367.9      .1       0
   582.1    .045       0   662.5      .1       0     820    .016       0
   840.1      .1       0     853    .016       0
#XS Ineff= 2 , 0
          443.38    2755
Permanent Ineff=
       F       F
#Block Obstruct= 1 ,-1
  199.34  235.59 2808.41
Bank Sta=582.1,662.5
XS Rating Curve= 0 ,0
Exp/Cntr(USF)=0,0
Exp/Cntr=0.3,0.1

Type RM Length L Ch R = 1 ,4249    ,283.7,286.5,297.1
Node Name=B
XS GIS Cut Line= 3
2302846.12304791568128.7549390682302503.21615259568054.997606867
2302105.96174933567781.966078895
#Sta/Elev= 30
       0 2839.74     6.1 2837.66    18.4 2837.92    75.6 2819.62    93.1 2805.61
   112.4 2784.97   116.6 2782.69   149.4 2785.57   173.8 2784.97   240.4 2784.28
   247.5 2783.53   255.7 2779.32   292.5 2748.74   312.9 2738.09   333.4 2739.08
   355.5 2744.14   368.1 2744.06   388.4 2739.34   423.3 2739.34   451.5 2733.09
   483.7 2732.91   552.7 2731.65   567.1 2732.85   577.7 2736.72     593 2738.35
   636.4 2764.29   774.6 2805.52   791.3 2811.84   817.4 2828.17   832.8 2829.88
#Mann= 8 ,-1,0
       0      .1       0   116.6    .016       0   173.8     .06       0
   240.4      .1       0   355.5    .016       0   368.1      .1       0
   483.7    .045       0   567.1      .1       0
#XS Ineff= 2 , 0
           410.7  2750.3
Permanent Ineff=
       F       F
Bank Sta=483.7,567.1
XS Rating Curve= 0 ,0
Exp/Cntr(USF)=0,0
Exp/Cntr=0.3,0.1

Type RM Length L Ch R = 1 ,3962    ,370,333.7,205.1
XS GIS Cut Line= 3
2302845.76978378567958.9292718692302354.08973614567596.825554472
2302149.96264055567541.799989573
#Sta/Elev= 30
       0 2837.37      31 2818.11    43.4 2797.13    56.7  2785.9    62.5 2782.85
    71.5 2782.83   104.1 2783.17   131.1 2782.03   136.9 2780.17   175.9 2753.59
   190.8 2741.17   205.5 2732.34   235.5 2732.82   254.1 2740.79   265.6 2740.95
   275.2  2738.6   290.1 2730.75   322.8 2733.14   344.8  2732.5   351.4 2730.69
   399.4 2729.85     459 2730.63   483.8 2733.38   558.4 2733.64   593.1  2746.8
   651.1 2757.83   695.5 2768.63   778.3 2798.44   807.3 2811.62     822 2812.97
#Mann= 7 ,-1,0
       0      .1       0    71.5    .016       0   104.1      .1       0
   254.1    .016       0   265.6      .1       0   351.4    .045       0
     459      .1       0
#XS Ineff= 2 , 0
           256.9 2749.25
Permanent Ineff=
       F       F
Bank Sta=351.4,459
XS Rating Curve= 0 ,0
Exp/Cntr(USF)=0,0
Exp/Cntr=0.3,0.1

Type RM Length L Ch R = 1 ,3628    ,243.3,240.6,230.1
XS GIS Cut Line= 3
2303068.99370479567421.8548136342302373.19175367567463.570996303
2302098.93893726567396.653822877
#Sta/Elev= 30
       0 2875.97    72.9 2851.23      89 2840.34     109 2839.91   155.1 2818.97
   165.1 2808.87   181.1 2782.14   185.2  2778.4   221.2 2777.78   245.3 2773.59
   301.4 2739.48   333.4 2731.07   341.4 2731.99   353.5 2731.84   361.5 2728.14
   365.5 2726.85   415.1  2728.1   465.7 2731.31   493.7 2728.34   553.8 2731.74
   605.9 2729.28   617.9 2736.66     642 2736.77   784.6 2764.14   854.6 2788.48
   883.4 2802.54   907.6 2802.89   916.3 2804.08   932.8  2815.3   979.3 2835.84
#Mann= 11 ,-1,0
       0      .1       0      89    .016       0     109      .1       0
   185.2    .016       0   221.2      .1       0   341.4    .016       0
   353.5      .1       0   361.5    .045       0   415.1      .1       0
   883.4    .016       0   907.6      .1       0
Bank Sta=361.5,415.1
XS Rating Curve= 0 ,0
Exp/Cntr=0.3,0.1