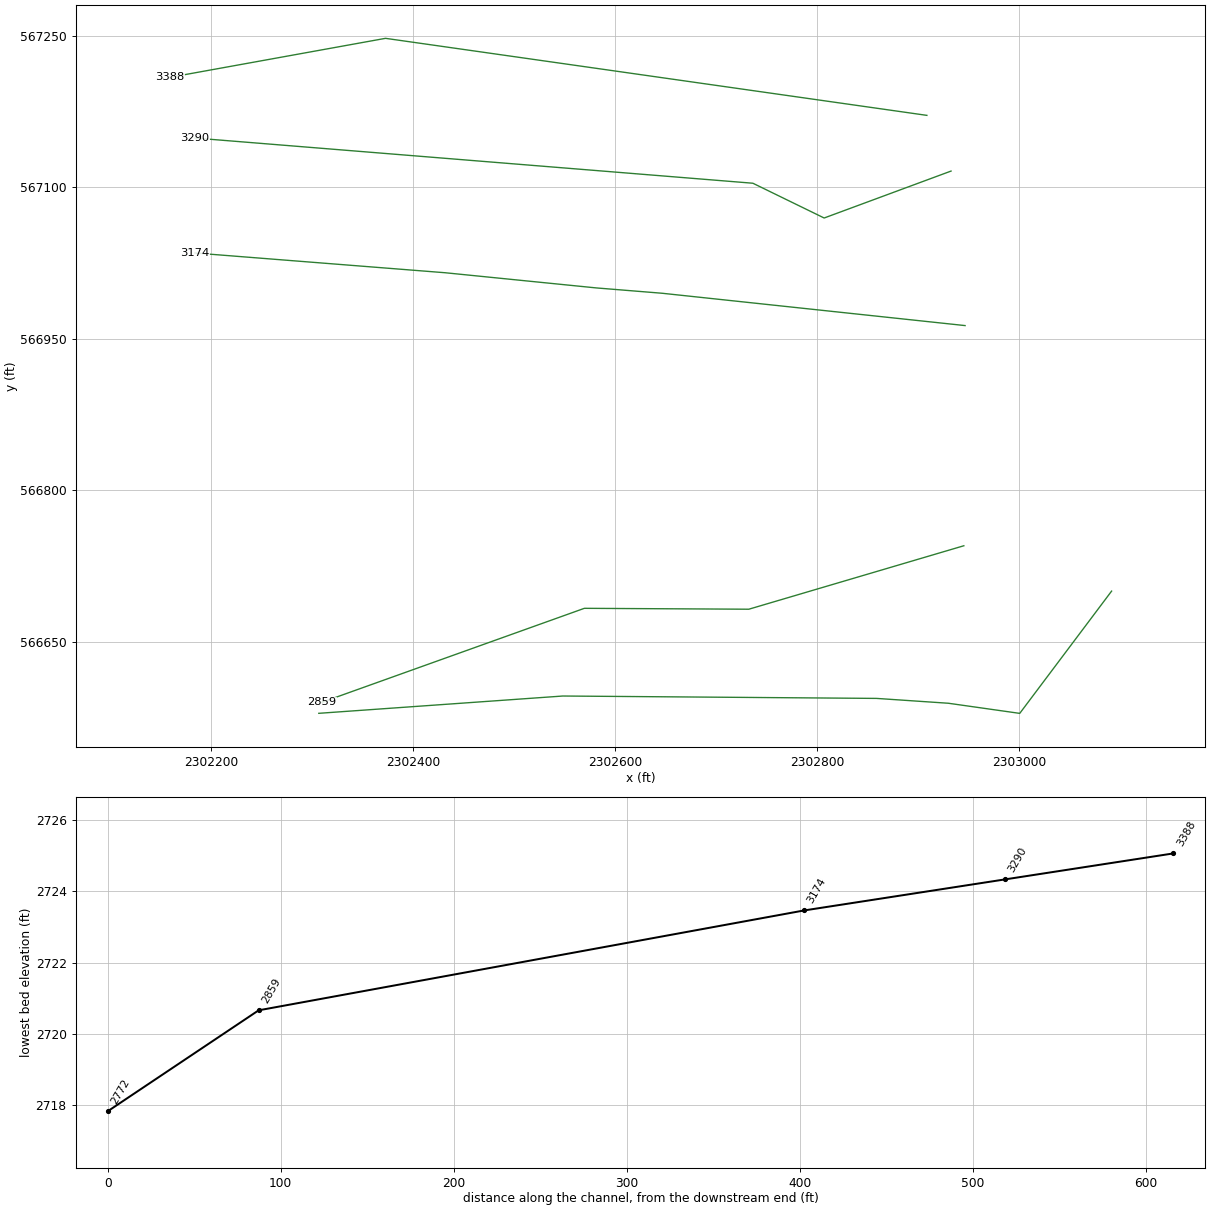
HEC-RAS study WFGRNBRRRV.prj: WFGRNBRRRV

--- WFGRNBRRRV.g01 (geometry) --- (continued)

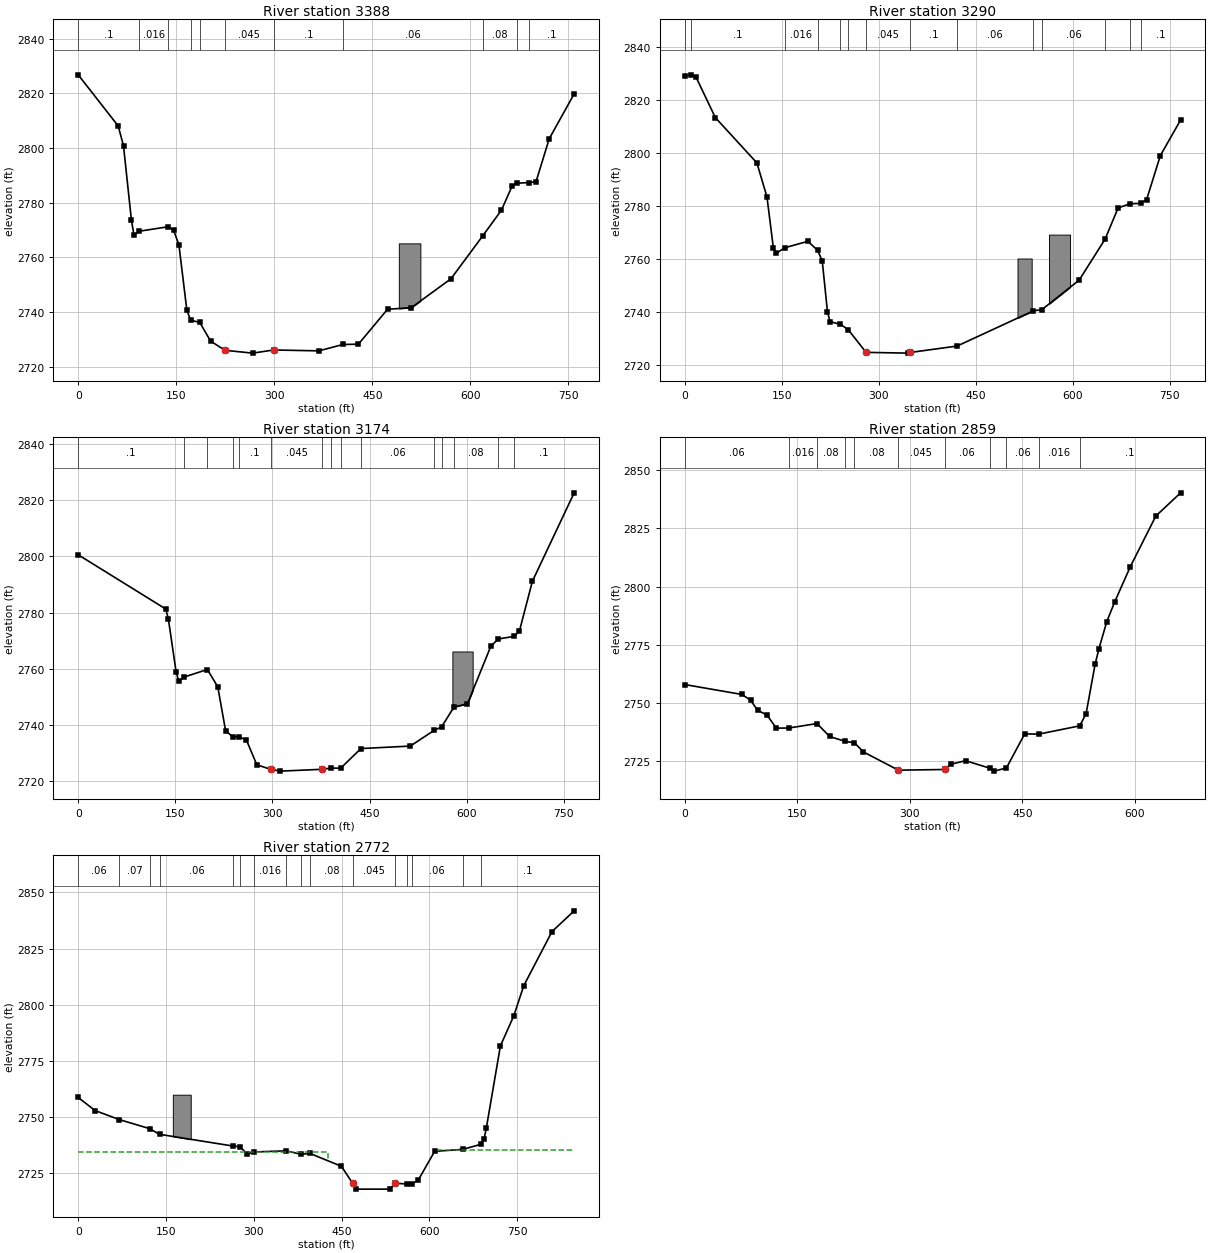
Type RM Length L Ch R = 1 ,3388    ,94.6,97.5,107.6
XS GIS Cut Line= 3
2302908.74511772567171.3616435052302372.54966833567247.653981995
2302158.71621256567208.970542761
#Sta/Elev= 30
       0 2826.74    61.2 2808.05    69.3 2800.81    81.4 2773.65    85.4 2768.14
    93.5 2769.61   137.9 2771.24     146 2769.97   154.1  2764.6   166.2 2740.83
   171.9 2737.11     186 2736.28   202.6 2729.45   224.6 2726.09     267 2725.06
   299.2 2726.21   368.2 2725.89   405.3 2728.22   428.8 2728.33   473.3 2741.08
   509.7 2741.67   570.4 2752.22   619.2 2767.97   647.7 2777.31   663.9 2786.09
   671.4 2787.13   690.3 2787.39   700.5 2787.64   720.8 2803.42   758.9 2819.77
#Mann= 11 ,-1,0
       0      .1       0    93.5    .016       0   137.9      .1       0
   171.9    .016       0     186      .1       0   224.6    .045       0
   299.2      .1       0   405.3     .06       0   619.2     .08       0
   671.4    .016       0   690.3      .1       0
#Block Obstruct= 1 ,-1
  490.61   523.6 2765.16
Bank Sta=224.6,299.2
XS Rating Curve= 0 ,0
Exp/Cntr(USF)=0,0
Exp/Cntr=0.3,0.1

Type RM Length L Ch R = 1 ,3290    ,116.8,116,117.2
XS GIS Cut Line= 4
2302932.67310306567116.1961133682302806.98681204567069.709402989
2302736.39588146 567104.144003272302183.72054696567148.908983635
#Sta/Elev= 30
       0 2829.06     9.1  2829.4    17.6 2828.51    47.4 2813.26   111.7 2796.14
   127.3 2783.25   137.1 2764.15   141.6 2762.05   154.9 2764.12   190.5 2766.54
   205.8 2763.11   212.8 2759.05   220.8 2739.97   224.8 2736.22   240.9 2735.21
   252.9  2733.2   280.5 2724.62   345.2 2724.33   349.2 2724.59   421.3    2727
   539.2  2740.3   552.3 2740.72   610.1  2751.9   650.2 2767.36   670.3 2779.13
   688.9 2780.74   705.1 2780.85   714.4 2782.31   735.7 2798.93     767 2812.36
#Mann= 14 ,-1,0
       0    .016       0     9.1      .1       0   154.9    .016       0
   205.8      .1       0   240.9    .016       0   252.9      .1       0
   280.5    .045       0   349.2      .1       0   421.3     .06       0
   539.2    .016       0   552.3     .06       0   650.2     .08       0
   688.9    .016       0   705.1      .1       0
#Block Obstruct= 2 ,-1
  514.74  536.65 2760.05  563.49  596.01 2769.08
Bank Sta=280.5,349.2
XS Rating Curve= 0 ,0
Exp/Cntr(USF)=0,0
Exp/Cntr=0.3,0.1

Type RM Length L Ch R = 1 ,3174    ,311.4,315.2,327.1
XS GIS Cut Line= 5
2302946.56604779566963.1567999652302646.44469234566995.182485229
2302581.50370272567000.4406390922302431.70232834567015.484911521
2302183.91446986567035.036243333
#Sta/Elev= 30
       0 2800.59   135.2 2781.26   139.2 2777.81   151.2 2758.86   155.3 2755.45
   163.3 2756.98   199.5 2759.69   215.6 2753.52   227.7 2737.82   239.1 2735.65
   248.1 2735.78   259.9 2734.52   275.9 2725.71   297.6  2724.1   312.1 2723.46
   376.6 2724.11   390.8 2724.56   405.4 2724.49   436.7 2731.51     513 2732.39
     550 2738.02   561.2 2739.18   580.5 2746.32   601.3 2747.47   637.4 2767.99
   648.8 2770.56   673.5 2771.51   681.6 2773.46   701.6 2791.16   766.1 2822.68
#Mann= 15 ,-1,0
       0      .1       0   163.3    .016       0   199.5      .1       0
   239.1    .016       0   248.1      .1       0   297.6    .045       0
   376.6      .1       0   390.8     .04       0   405.4      .1       0
   436.7     .06       0     550    .016       0   561.2     .06       0
   580.5     .08       0   648.8    .016       0   673.5      .1       0
#Block Obstruct= 1 ,-1
     578   609.3 2766.12
Bank Sta=297.6,376.6
XS Rating Curve= 0 ,0
Exp/Cntr(USF)=0,0
Exp/Cntr=0.3,0.1

Type RM Length L Ch R = 1 ,2859    ,87.8,87.2,83.8
BEGIN DESCRIPTION:
xs 4
END DESCRIPTION:
XS GIS Cut Line= 4
2302945.34167601566745.0986419422302732.38965092566682.243796453
2302569.50031545 566683.131067822302309.57596289566590.059277344
#Sta/Elev= 30
       0 2757.89    76.3 2753.63    87.8 2751.17    97.1 2746.86   109.7 2744.76
   122.2 2739.14   138.8  2739.2   176.4 2741.12   193.1 2735.56   213.9 2733.46
   226.2 2732.86   238.2 2728.92   284.8 2721.07   346.3 2721.36   354.3 2723.58
   374.3 2725.15   406.3 2721.96   412.5 2720.66   428.8 2722.02   453.2 2736.66
     472 2736.58   526.5 2740.13     535 2745.34     547 2766.55     552 2773.17
   562.6 2784.96   573.3 2793.55     594  2808.6     628 2830.37     661 2840.33
#Mann= 11 ,-1,0
       0     .06       0   138.8    .016       0   176.4     .08       0
   213.9    .016       0   226.2     .08       0   284.8    .045       0
   346.3     .06       0   406.3     .04       0   428.8     .06       0
     472    .016       0   526.5      .1       0
Bank Sta=284.8,346.3
XS Rating Curve= 0 ,0
Exp/Cntr(USF)=0,0
Exp/Cntr=0.5,0.3

Type RM Length L Ch R = 1 ,2772    ,37.8,40.2,43.7
BEGIN DESCRIPTION:
xs 3
END DESCRIPTION:
XS GIS Cut Line= 6
2303091.67481166566700.1644816462303000.69895697 566579.07964259
2302930.05714286 566589.102386242302858.94883993566593.905275075
2302548.18010986566596.2700376852302306.47271183566579.136724665
#Sta/Elev= 30
       0 2758.65    28.8 2752.83    70.3  2748.8   121.8 2744.79   138.9 2742.25
   264.8 2737.01   276.3 2736.71   288.8 2733.45   300.8 2734.39   354.8 2734.88
   380.9 2733.37   396.1 2733.71   449.6 2728.01   468.9 2720.39   474.7 2717.83
   532.9 2717.83   540.9 2720.47   560.9 2720.12     570 2720.17   580.9 2721.87
   608.9 2734.67   656.5 2735.52   687.9 2737.79   693.1    2740   697.1 2744.92
   721.2 2781.62     744 2794.96   761.2 2808.52   809.4 2832.57   847.2 2841.81
#Mann= 16 ,-1,0
       0     .06       0    70.3     .07       0   121.8    .016       0
   138.9     .06       0   264.8    .016       0   276.3     .06       0
   300.8    .016       0   354.8     .06       0   380.9    .016       0
   396.1     .08       0   468.9    .045       0   540.9     .06       0
   560.9     .04       0     570     .06       0   656.5    .016       0
   687.9      .1       0
#XS Ineff= 2 , 0
             426 2734.47   614.2         2735.26
Permanent Ineff=
       F       F
#Block Obstruct= 1 ,-1
   161.6  192.21  2759.9
Bank Sta=468.9,540.9
XS Rating Curve= 0 ,0
Exp/Cntr(USF)=0,0
Exp/Cntr=0.5,0.3