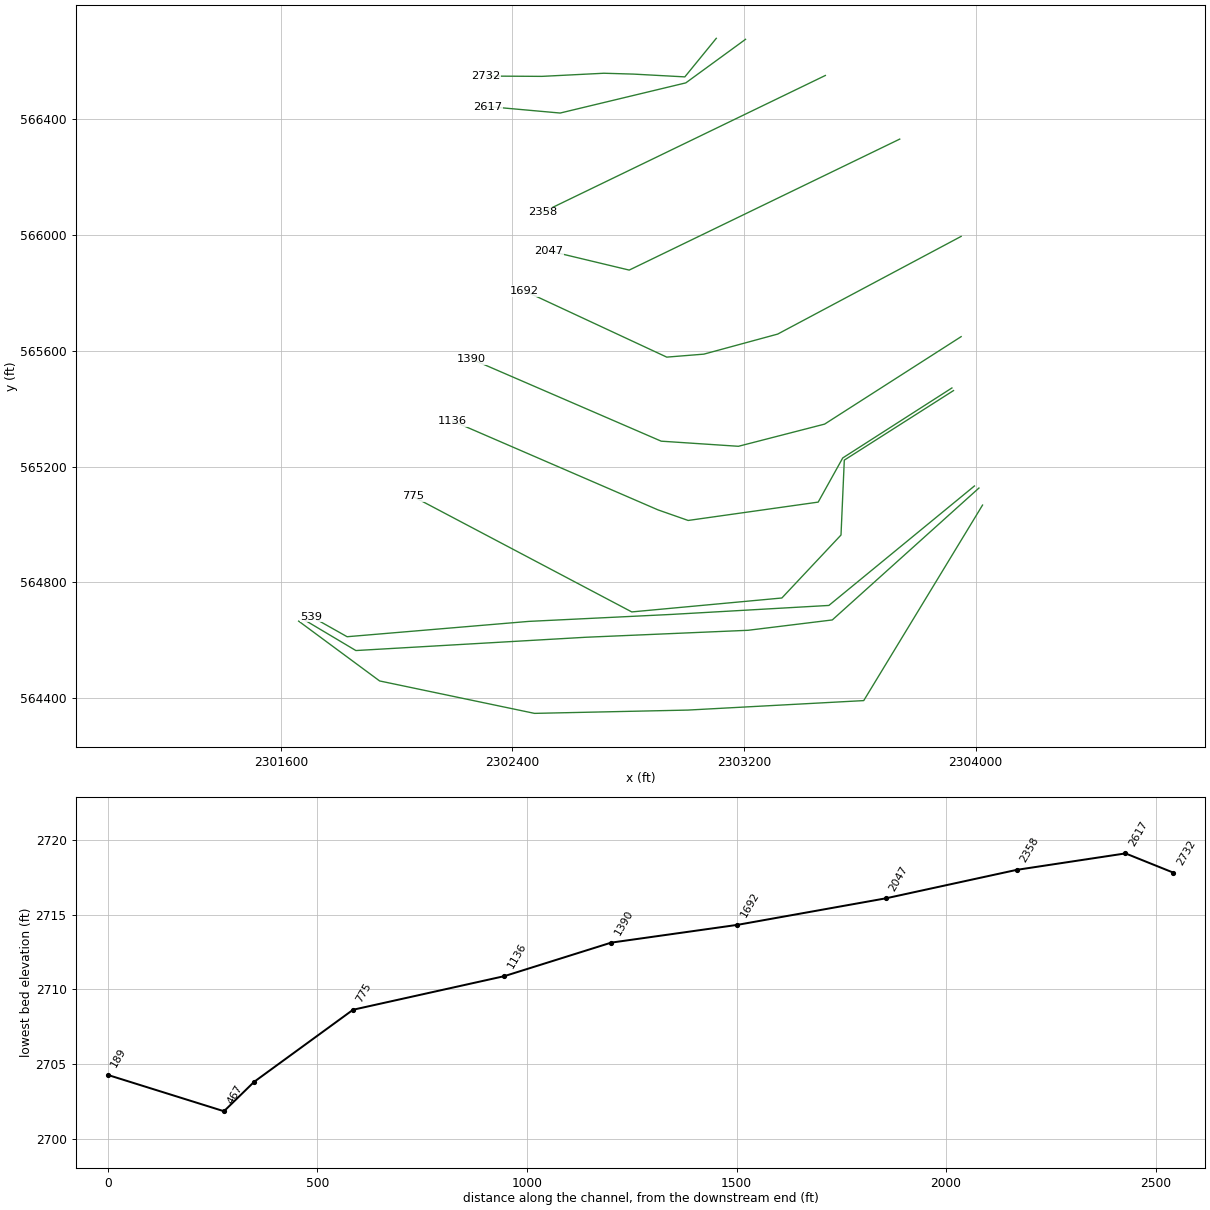
HEC-RAS study WFGRNBRRRV.prj: WFGRNBRRRV

--- WFGRNBRRRV.g01 (geometry) --- (continued)

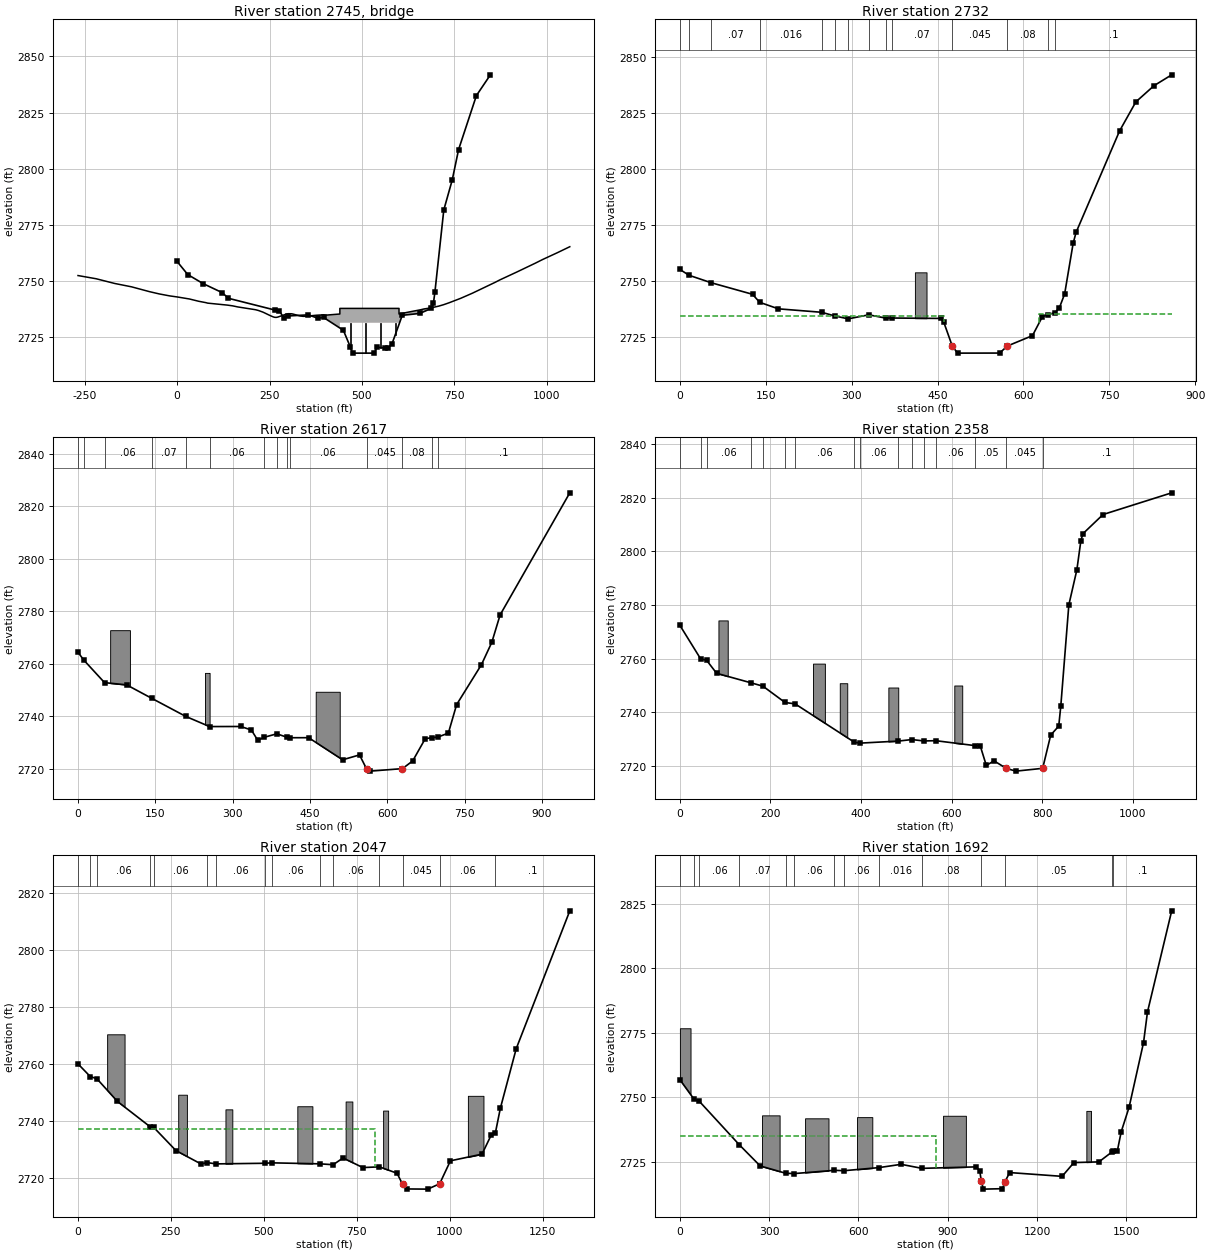
Type RM Length L Ch R = 3 ,2745    ,,,
BEGIN DESCRIPTION:
Bridge No.: Bridge 54075WFG020
Abandoned Bridge
JV notes: road deck updated per available survey data provided. survey provided was only partial, noted that structure is to be removed at some point
channel from Effective profile - no survery points collected
per imagery, structure is approx. 160' wide, guardrail assumed 2.5' per standard specs
4 circular piers shown in the photos provided by survey, pier coefficients updated per surveyed photos: 2 piers located within channel
END DESCRIPTION:
Bridge Culvert--1,0,-1,-1, 0
Deck Dist Width WeirC Skew NumUp NumDn MinLoCord MaxHiCord MaxSubmerge Is_Ogee
17.83638,18,2.6,0, 53, 53, , , 0.98, 0, 0,0,,
    -268 -218.84-169.195-123.085 -74.524  -48.45 -20.062    .438  33.238  58.348
  78.192  82.438 135.738 150.192 164.136 212.295 220.321 232.361 252.369 260.453
 264.466 268.479 272.493  293.57 300.562 308.569 312.573 332.591 340.598 348.605
 376.148 396.647   400.5   440.1   440.1   600.1   600.1   629.3  658.56 667.569
 688.063 708.121 720.703 735.155 766.695 798.236 860.445 872.313  919.07 968.107
 988.0321029.1131061.935
2752.388 2750.962748.8792747.359 2745.21 2744.212743.3262742.8532741.953 2740.93
2740.3082740.1062739.226 2738.892738.4062737.1632736.8032736.0782734.5022733.939
2733.7692733.758  2733.92735.1222735.3972735.3732735.2732734.3752734.219 2734.25
2734.7062734.9062734.7342735.2592737.7592737.7592735.259 2736.23 2737.152737.509
 2738.03  2738.82739.4092740.2412742.2342744.5052749.4012750.4132753.9932757.855
  2759.5 2762.632765.235
                                                                                
                                                                                
                                                                                
                         2731.35 2731.35 2731.35 2731.35
                                                                                
                        
    -244 -194.84-145.195 -99.085 -50.524  -24.45   3.938  24.438  57.238  82.348
 102.192 106.438 159.738 174.192 188.136 236.295 244.321 256.361 276.369 284.453
 288.466 292.479 296.493  317.57 324.562 332.569 336.573 356.591 364.598 372.605
 400.148 420.647   424.5   464.1   464.1   624.1   624.1   653.3  682.56 691.569
 712.063 732.121 744.703 759.155 790.695 822.236 884.445 896.313  943.07 992.107
1012.0321053.1131085.935
2752.388 2750.962748.8792747.359 2745.21 2744.212743.3262742.8532741.953 2740.93
2740.3082740.1062739.226 2738.892738.4062737.1632736.8032736.0782734.5022733.939
2733.7692733.758  2733.92735.1222735.3972735.3732735.2732734.3752734.219 2734.25
2734.7062734.9062734.7342735.2592737.7592737.7592735.259 2736.23 2737.152737.509
 2738.03  2738.82739.4092740.2412742.2342744.5052749.4012750.4132753.9932757.855
  2759.5 2762.632765.235
                                                                                
                                                                                
                                                                                
                         2731.35 2731.35 2731.35 2731.35
                                                                                
                        
Pier Skew, UpSta & Num, DnSta & Num=  ,470.1, 2 ,494.1, 2 , 0 , 0 , 0 ,,
       3       3
       0  2731.5
       3       3
       0  2731.5
Pier Skew, UpSta & Num, DnSta & Num=  ,510.1, 2 ,534.1, 2 , 0 , 0 , 0 ,,
       3       3
       0  2731.5
       3       3
       0  2731.5
Pier Skew, UpSta & Num, DnSta & Num=  ,550.1, 2 ,574.1, 2 , 0 , 0 , 0 ,,
       3       3
       0  2731.5
       3       3
       0  2731.5
Pier Skew, UpSta & Num, DnSta & Num=  ,590.1, 2 ,614.1, 2 , 0 , 0 , 0 ,,
       3       3
       0  2731.5
       3       3
       0  2731.5
BR Coef=-1 ,-1 , 0 ,, 0 ,,,0.8,0,1.2,0,
WSPro=,,,, 1 ,,,, 0 ,,,, 0 ,,,,-1 ,-1 ,-1 , 0 , 0 , 0 , 0 , 0
BR U #Sta/Elev= 30
       0 2758.65    28.8 2752.83    70.3  2748.8   121.8 2744.79   138.9 2742.25
   264.8 2737.01   276.3 2736.71   288.8 2733.45   300.8 2734.39   354.8 2734.88
   380.9 2733.37   396.1 2733.71   449.6 2728.01   468.9 2720.39   474.7 2717.83
   532.9 2717.83   540.9 2720.47   560.9 2720.12     570 2720.17   580.9 2721.87
   608.9 2734.67   656.5 2735.52   687.9 2737.79   693.1    2740   697.1 2744.92
   721.2 2781.62     744 2794.96   761.2 2808.52   809.4 2832.57   847.2 2841.81
BR U #Mann= 16
       0     .06    70.3     .07   121.8    .016   138.9     .06   264.8    .016
   276.3     .06   300.8    .016   354.8     .06   380.9    .016   396.1     .08
   468.9     .04   540.9     .06   560.9     .04     570     .06   656.5    .016
   687.9      .1
BR D #Sta/Elev= 30
       0 2755.11    15.9 2752.51    54.5 2749.19   126.8 2744.03   139.4 2740.45
   171.9 2737.55   247.5 2736.01   270.4 2734.38   293.9 2733.08   329.9 2734.87
   359.6 2733.41     371 2733.45   455.7 2733.27     461 2731.53   475.7 2720.98
  484.97  2717.8   558.5 2717.83   571.8 2720.95   615.8  2725.6     633 2733.98
   643.5 2735.02   655.5  2735.9     663 2738.14     672 2744.17   686.9  2766.8
     692 2771.64     768 2816.88   796.4  2829.8     828 2837.01     859 2841.87
BR D #Mann= 14
       0     .05    15.9     .06    54.5     .07   139.4    .016   247.5     .06
   270.4     .08   293.9    .016   329.9     .06   359.6    .016     371     .07
   475.7     .04   571.8     .08   643.5    .016   655.5      .1
BC Design=,, 0 ,, 0 ,,,,,,
BC Use User HTab Curves=0
BC User HTab FreeFlow(D)= 0

Type RM Length L Ch R = 1 ,2732    ,104.4,114.4,127.3
BEGIN DESCRIPTION:
xs 2
END DESCRIPTION:
XS GIS Cut Line= 6
 2303104.3357979566679.4344516682302995.65816141566546.267108812
2302817.89977182566555.889410305  2302715.841407 566558.83031003
2302501.83460276566548.0364415082302309.11335534566549.057011612
#Sta/Elev= 30
       0 2755.11    15.9 2752.51    54.5 2749.19   126.8 2744.03   139.4 2740.45
   171.9 2737.55   247.5 2736.01   270.4 2734.38   293.9 2733.08   329.9 2734.87
   359.6 2733.41     371 2733.45   455.7 2733.27     461 2731.53   475.7 2720.98
  484.97  2717.8   558.5 2717.83   571.8 2720.95   615.8  2725.6     633 2733.98
   643.5 2735.02   655.5  2735.9     663 2738.14     672 2744.17   686.9  2766.8
     692 2771.64     768 2816.88   796.4  2829.8     828 2837.01     859 2841.87
#Mann= 14 ,-1,0
       0     .05       0    15.9     .06       0    54.5     .07       0
   139.4    .016       0   247.5     .06       0   270.4     .08       0
   293.9    .016       0   329.9     .06       0   359.6    .016       0
     371     .07       0   475.7    .045       0   571.8     .08       0
   643.5    .016       0   655.5      .1       0
#XS Ineff= 2 , 0
           460.8 2734.47   627.4         2735.26
Permanent Ineff=
       F       F
#Block Obstruct= 1 ,-1
  410.48  430.77 2753.82
Bank Sta=475.7,571.8
XS Rating Curve= 0 ,0
Exp/Cntr(USF)=0,0
Exp/Cntr=0.5,0.3

Type RM Length L Ch R = 1 ,2617    ,242.3,259.4,272.2
XS GIS Cut Line= 4
2303205.31815185566675.9987133082302999.00647594566525.563116284
2302564.89232453566421.332738347 2302313.4499695566443.898077901
#Sta/Elev= 30
       0 2764.37    11.4 2761.37    51.5 2752.81    94.4 2751.96   143.1 2746.83
     209 2739.95   255.3 2736.07   315.8  2736.1   336.4 2734.76   348.7 2730.85
   361.5    2732   385.8 2733.31   404.8 2732.04   411.2 2731.82   447.5 2731.83
   513.4 2723.41   546.2 2725.27   559.9 2719.93   566.8 2719.09   629.5 2720.04
   649.4 2722.98   673.7 2731.44   686.1 2731.84   698.4 2732.08   718.6 2733.58
   734.6 2744.43   782.8 2759.67   802.9 2768.17     819 2778.62   954.2 2825.14
#Mann= 14 ,-1,0
       0     .06       0    11.4     .05       0    51.5     .06       0
   143.1     .07       0     209    .016       0   255.3     .06       0
   361.5    .016       0   385.8     .06       0   404.8    .016       0
   411.2     .06       0   559.9    .045       0   629.5     .08       0
   686.1    .016       0   698.4      .1       0
#Block Obstruct= 3 ,-1
   62.38  100.73  2772.8  246.31  255.33 2756.52  461.21  507.81 2749.33
Bank Sta=559.9,629.5
XS Rating Curve= 0 ,0
Exp/Cntr(USF)=0,0
Exp/Cntr=0.3,0.1

Type RM Length L Ch R = 1 ,2358    ,311.6,311.3,314.9
XS GIS Cut Line= 2
2303481.15340752566551.1478410852302503.73848915566078.355314976
#Sta/Elev= 30
       0 2772.39    45.5 2759.96    59.1 2759.32    81.1  2754.5   156.6 2750.97
   183.3  2749.7   232.1 2743.61   254.4 2743.09   385.2 2728.77   397.5 2728.44
   482.2  2729.2   512.1 2729.77   538.7 2729.25   564.9 2729.35   652.1  2727.5
   663.2 2727.36   676.5 2720.11   693.5 2721.83   720.8 2718.99   741.9 2717.99
   800.9 2719.03   818.7 2731.44   836.4  2734.8   840.9 2742.17   858.7 2780.04
   876.4 2793.09   885.3    2804   889.8  2806.6   934.2 2813.76  1085.8 2821.86
#Mann= 16 ,-1,0
       0     .06       0    45.5    .016       0    59.1     .06       0
   156.6    .016       0   183.3     .06       0   232.1    .016       0
   254.4     .06       0   385.2    .016       0   397.5     .06       0
   482.2    .016       0   512.1     .06       0   538.7    .016       0
   564.9     .06       0   652.1     .05       0   720.8    .045       0
   800.9      .1       0
#Block Obstruct= 5 ,-1
   85.08  105.59 2774.24  293.91  320.11 2758.12  352.97  369.47  2750.8
  460.25  482.07  2749.2  605.83  623.33 2749.95
Bank Sta=720.8,800.9
XS Rating Curve= 0 ,0
Exp/Cntr(USF)=0,0
Exp/Cntr=0.3,0.1

Type RM Length L Ch R = 1 ,2047    ,380.9,354.9,274.6
XS GIS Cut Line= 3
2303738.01989507566331.2954632722302803.50913167565878.779998976
2302526.39868447565945.109627293
#Sta/Elev= 30
       0 2760.06    32.9 2755.63    50.9 2754.84   105.8 2746.91   193.2 2738.07
   203.6 2737.79   263.5 2729.63   330.9 2724.93   347.3 2725.41   371.3 2724.95
     503 2725.17     521 2725.32   650.9 2724.97   686.5 2724.66   713.1 2727.03
   766.3 2723.66   810.9 2723.91   858.4 2721.67   873.1 2717.84   886.5 2716.15
     941 2716.09   973.1 2717.97   973.1 2717.98    1002 2726.03    1087 2728.37
  1111.7 2735.06  1122.7 2735.65  1136.3 2744.45  1179.1 2765.42  1323.2  2813.8
#Mann= 15 ,-1,0
       0     .06       0    32.9    .016       0    50.9     .06       0
   193.2    .016       0   203.6     .06       0   347.3    .016       0
   371.3     .06       0     503    .016       0     521     .06       0
   650.9    .016       0   686.5     .06       0   810.9     .05       0
   873.1    .045       0   973.1     .06       0  1122.7      .1       0
#XS Ineff= 2 , 0
             800 2737.36
Permanent Ineff=
       F       F
#Block Obstruct= 7 ,-1
   78.37  125.27 2770.45  269.59  292.99 2749.24  396.74  415.19  2744.1
   590.1  630.64 2745.19  720.06  738.16 2746.86  820.89   834.4 2743.67
 1049.02 1090.91 2748.85
Bank Sta=873.1,973.1
XS Rating Curve= 0 ,0
Exp/Cntr(USF)=0,0
Exp/Cntr=0.3,0.1

Type RM Length L Ch R = 1 ,1692    ,307.4,301.4,278.1
Node Name=A
XS GIS Cut Line= 5
2303950.27470568565995.2253464662303316.45825732565657.681237919
2303061.45768623565588.4036261222302933.22040482565578.085683939
2302442.38115527565806.554403698
#Sta/Elev= 30
       0 2756.78    47.7 2749.19    65.8 2748.34   200.1 2731.47   269.8 2723.31
   355.9 2720.46   384.5 2720.35     519 2721.62   550.7 2721.46   669.1 2722.67
   743.3 2723.94   813.3 2722.38   995.7 2722.95  1007.7 2721.36  1012.62717.409
  1019.7 2714.31  1083.9 2714.48    1092 2717.13    1108 2720.74  1284.2 2719.27
  1323.9 2724.62  1407.8 2724.89  1453.4 2728.88  1456.3 2728.98  1469.5 2728.99
  1482.8  2736.6  1509.2 2746.09  1557.8 2771.22    1571 2783.08  1652.4 2822.38
#Mann= 14 ,-1,0
       0     .07       0    47.7    .016       0    65.8     .06       0
   200.1     .07       0   355.9    .016       0   384.5     .06       0
     519    .016       0   550.7     .06       0   669.1    .016       0
   813.3     .08       0  1012.6    .045       0    1092     .05       0
  1453.4    .016       0  1456.3      .1       0
#XS Ineff= 2 , 0
             861    2735
Permanent Ineff=
       F       F
#Block Obstruct= 6 ,-1
       0   35.69 2776.78     276  335.01 2742.96  420.55  499.28 2741.81
  595.04  646.47 2742.27  884.18  960.85  2742.8 1365.66 1381.27 2744.69
Bank Sta=1012.6,1092
XS Rating Curve= 0 ,0
Exp/Cntr(USF)=0,0
Exp/Cntr=0.3,0.1

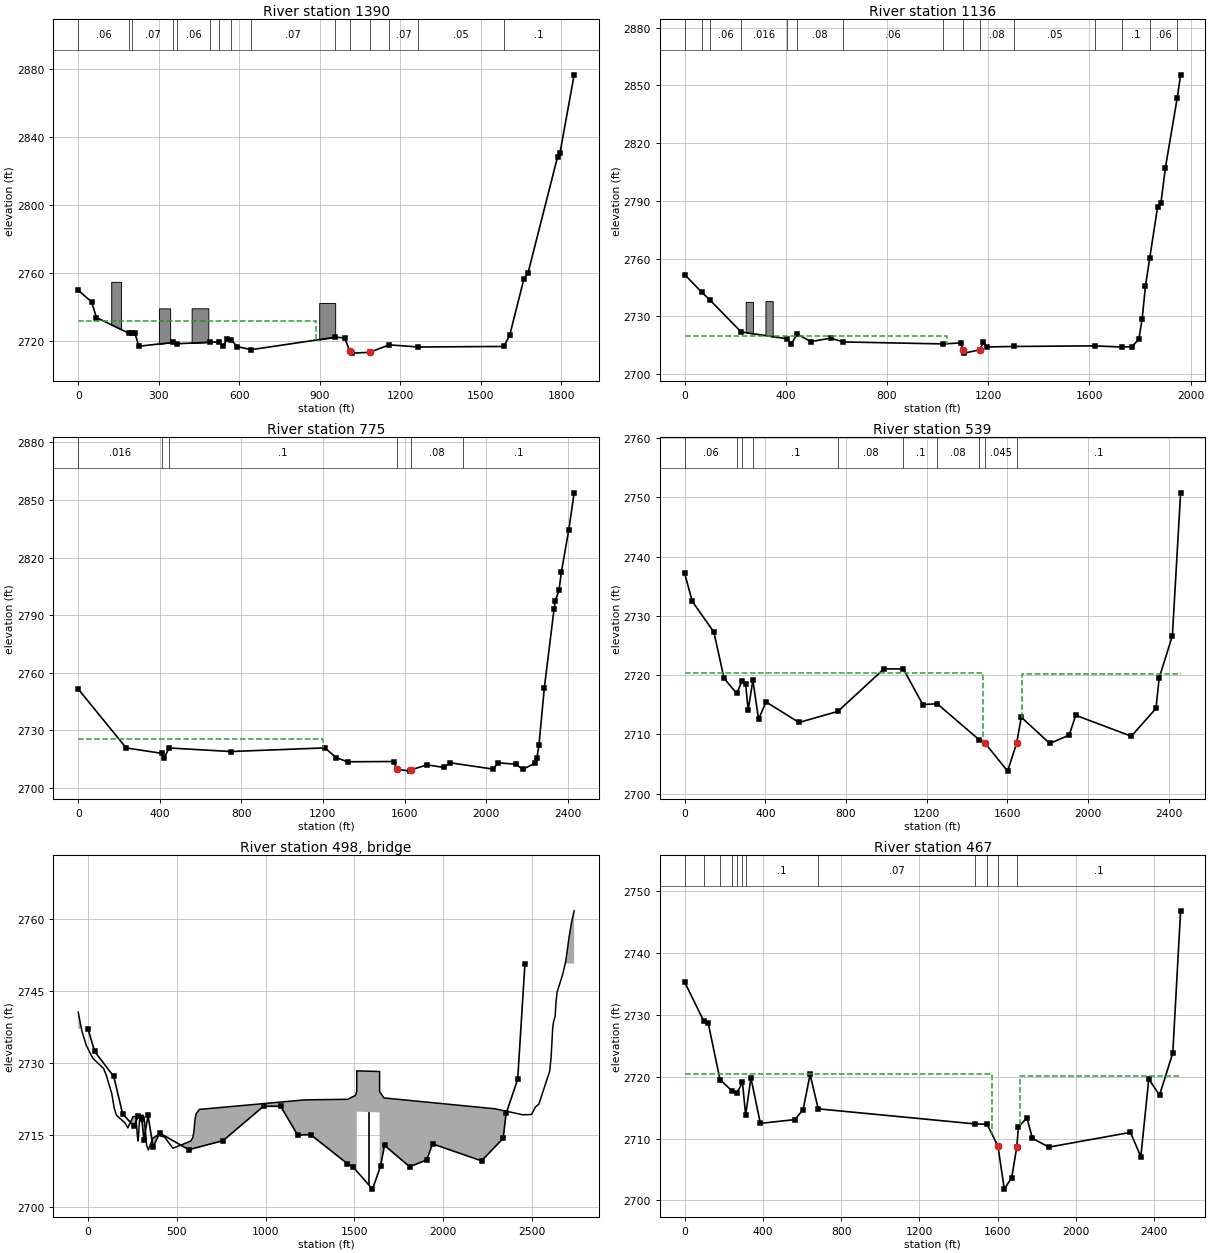
Type RM Length L Ch R = 1 ,1390    ,266.7,254.6,222.7
XS GIS Cut Line= 5
2303950.27470568565648.8372874772303478.59734876  565346.6689807
 2303180.8510172  565270.02141022302914.05851219565287.709311085
2302259.60617947565570.715725237
#Sta/Elev= 30
       0 2750.04      50 2743.17    67.9 2734.01   187.8 2724.88     202 2725.04
   211.5 2724.76   225.8 2717.15     354 2719.44   368.3 2718.64   491.8 2719.54
   525.4 2719.58   539.3 2717.13   555.5  2721.4   570.9 2720.82   591.6 2716.97
   645.3 2715.16   957.7 2722.46   992.6 2722.08  1012.6 2714.16  1020.6 2713.12
  1085.5 2713.59  1158.9 2717.97  1267.8 2716.72  1585.9 2717.04  1607.7 2723.55
  1660.8 2756.73    1676 2760.09  1786.4 2828.52  1795.1 2830.56    1848 2876.53
#Mann= 15 ,-1,0
       0     .06       0   187.8    .016       0     202     .07       0
     354    .016       0   368.3     .06       0   491.8    .016       0
   525.4     .06       0   570.9     .08       0   645.3     .07       0
   957.7     .08       0  1012.6    .045       0  1085.5     .08       0
  1158.9     .07       0  1267.8     .05       0  1585.9      .1       0
#XS Ineff= 2 , 0
          886.76 2731.88
Permanent Ineff=
       F       F
#Block Obstruct= 4 ,-1
     123   159.4 2754.98  300.63   342.5  2739.4  422.67  484.78 2739.45
  898.03  957.56 2742.55
Bank Sta=1012.6,1085.5
XS Rating Curve= 0 ,0
Exp/Cntr(USF)=0,0
Exp/Cntr=0.3,0.1

Type RM Length L Ch R = 1 ,1136    ,374.9,361.1,352.8
XS GIS Cut Line= 6
2303918.39155183565471.549972054 2303541.2280193565229.778476838
2303456.33936098565077.1937998572303007.18164986565013.795941112
2302902.95127193565050.3303003892302192.68034598565357.648734307
#Sta/Elev= 30
       0  2751.7      67 2742.55    98.6 2738.65   223.2 2721.88   405.8 2718.31
   420.7 2715.51   444.5  2720.8   499.5 2716.85   576.9 2718.67   626.8  2716.7
  1022.7 2715.66  1092.1  2716.2 1099.71 2712.59  1104.8 2710.88    1167 2712.61
  1181.1 2716.68  1194.1 2714.09  1301.8 2714.34  1621.2 2714.66  1727.7 2714.05
    1768 2714.23  1795.5 2718.12  1808.6 2728.73  1821.7 2745.76  1838.5 2760.28
  1869.3 2786.61  1882.7 2788.82  1900.1  2806.9  1947.1 2843.43  1960.6 2855.46
#Mann= 15 ,-1,0
       0     .07       0      67    .016       0    98.6     .06       0
   223.2    .016       0   405.8     .07       0   444.5     .08       0
   626.8     .06       0  1022.7     .08       0 1099.71    .045       0
    1167     .08       0  1301.8     .05       0  1621.2     .07       0
  1727.7      .1       0  1838.5     .06       0  1947.1      .1       0
#XS Ineff= 2 , 0
            1036    2720
Permanent Ineff=
       F       F
#Block Obstruct= 2 ,-1
   241.3   269.8  2737.5   319.3   347.9  2737.9
Bank Sta=1099.71,1167
XS Rating Curve= 0 ,0
Exp/Cntr(USF)=0,0
Exp/Cntr=0.3,0.1

Type RM Length L Ch R = 1 ,775     ,72.2,235.9,168
BEGIN DESCRIPTION:
xs 4
END DESCRIPTION:
XS GIS Cut Line= 6
2303923.93915002565462.5155053972303546.60071919565222.256696987
 2303535.2077303564963.4911797172303330.91247509564745.929998837
2302812.30146812564697.8184075652302056.36161267565096.734308739
#Sta/Elev= 30
       0 2751.43   235.1 2720.73   409.5  2717.9     421 2715.44   445.5  2720.7
   748.6 2718.85  1209.5 2720.74  1265.4 2715.64  1320.6 2713.51  1548.4 2713.64
 1560.63 2709.69  1625.6 2708.63  1631.4 2709.33  1711.4 2711.88  1792.4 2710.55
    1824 2712.99  2036.2 2709.65  2057.3 2712.99  2146.3 2712.22  2179.6  2709.5
  2238.6 2712.73  2248.7 2715.34    2259 2722.08  2285.5 2752.05  2333.3 2793.25
  2339.3 2797.42  2357.3 2802.84  2369.2 2812.55  2405.5 2834.56  2431.7 2853.73
#Mann= 6 ,-1,0
       0    .016       0   409.5     .06       0   445.5      .1       0
 1560.63    .045       0  1631.4     .08       0  1886.1      .1       0
#XS Ineff= 2 , 0
         1201.69 2725.48
Permanent Ineff=
       F       F
Bank Sta=1560.63,1631.4
XS Rating Curve= 0 ,0
Exp/Cntr(USF)=0,0
Exp/Cntr=0.5,0.3

Type RM Length L Ch R = 1 ,539     ,158.6,72.1,66.3
BEGIN DESCRIPTION:
xs 3
END DESCRIPTION:
XS GIS Cut Line= 6
2303996.22786791 565132.966543452303493.33726616564720.222491039
2302949.05477184 564689.147399762302455.99415446564665.042214022
2301828.93939994564612.1147778292301706.14133504564681.257023933
#Sta/Elev= 30
       0 2737.17    37.5 2732.47     145 2727.26   195.1 2719.49   258.2 2716.91
   283.4 2718.95   302.3 2718.49   314.9  2714.1   338.1 2719.14   366.5 2712.57
   403.5 2715.49   567.1 2712.02   759.9 2713.89   988.1 2721.06  1084.4 2721.06
  1180.6 2715.05  1252.7 2715.17    1460 2709.11  1490.6  2708.5 1601.49 2703.81
 1646.65 2708.56  1669.2 2712.92  1810.5 2708.48  1906.8 2709.88  1939.4 2713.23
  2215.1  2709.7  2337.2 2714.39  2353.5 2719.57  2418.7 2726.66  2459.6 2750.77
#Mann= 10 ,-1,0
       0     .06       0   258.2    .016       0   283.4     .06       0
   338.1      .1       0   759.9     .08       0  1084.4      .1       0
  1252.7     .08       0    1460      .1       0  1490.6    .045       0
 1646.65      .1       0
#XS Ineff= 2 , 0
          1480.9 2720.39  1673.5         2720.16
Permanent Ineff=
       F       F
Bank Sta=1490.6,1646.65
XS Rating Curve= 0 ,0
Exp/Cntr(USF)=0,0
Exp/Cntr=0.5,0.3

Type RM Length L Ch R = 3 ,498     ,,,
BEGIN DESCRIPTION:
Bridge No.: Bridge 54075WFG010
Railroad crossing
JV notes: road deck updated per survey data provided
channel burned per survey points
rail height provided in survey viewer
pier shape and size provided in survey viewer, checked against survey photos provided
invert from survey:
   US invert: 2703.81
   DS invert:2703.71
END DESCRIPTION:
Bridge Culvert--1,0,-1,-1, 0
Deck Dist Width WeirC Skew NumUp NumDn MinLoCord MaxHiCord MaxSubmerge Is_Ogee
34,18,2.6,0, 60, 60, , , 0.98, 0, 0,0,,
     -55 -33.257  -9.306   27.04  87.616 102.657 133.834 148.193 160.308 207.524
  224.53 252.872 267.044 270.346 278.381 281.461 284.049 289.718 293.576 309.557
 318.283 329.922 339.589  366.22 392.852 431.431 478.074 578.285 590.401 596.458
 602.516 608.574 626.9941220.6871461.385 1505.65 1512.93 1512.93 1597.34 1641.46
 1641.46    16662291.1092446.9992496.1592518.8822537.567 2597.382599.8312607.069
2615.7842620.3852629.5862634.1882640.3052672.6852689.3992707.8032721.6062736.576
2740.6582736.5872733.7192731.0632728.9332727.5522723.6952720.5812719.1982717.631
2716.5622718.8622718.9822718.5182714.7612713.8162714.7222717.8612718.9992719.225
2717.9392712.9692711.9682714.4692715.0452714.6452712.3132713.816 2714.562715.952
2718.3042719.4842720.4072722.3942722.508 2723.32 2724.23 2728.432728.345  2728.3
  2724.1  2722.82720.5362719.2882719.3492720.9322721.4792728.1892728.6562731.381
 2737.332738.5642739.8492742.5972744.7812748.6122751.2822756.2142759.2912761.749
                                                                                
                                                                                
                                                                                
                                                 2719.95 2719.95 2719.84 2719.78
 2719.78
                                                                                
      10  31.743  55.694   92.04 152.616 167.657 198.834 213.193 225.308 272.524
  289.53 317.872 332.044 335.346 343.381 346.461 349.049 354.718 358.576 374.557
 383.283 394.922 404.589  431.22 457.852 496.431 543.074 643.285 655.401 661.458
 667.516 673.574 691.9941285.6871526.385 1570.65 1577.93 1577.93 1662.34 1706.46
 1706.46    17312356.1092511.9992561.1592583.8822602.567 2662.382664.8312672.069
2680.7842685.3852694.5862699.1882705.3052737.6852754.3992772.8032786.6062801.576
2740.6582736.5872733.7192731.0632728.9332727.5522723.6952720.5812719.1982717.631
2716.5622718.8622718.9822718.5182714.7612713.8162714.7222717.8612718.9992719.225
2717.9392712.9692711.9682714.4692715.0452714.6452712.3132713.816 2714.562715.952
2718.3042719.4842720.4072722.3942722.508 2723.32 2724.23 2728.432728.345  2728.3
  2724.1  2722.82720.5362719.2882719.3492720.9322721.4792728.1892728.6562731.381
 2737.332738.5642739.8492742.5972744.7812748.6122751.2822756.2142759.2912761.749
                                                                                
                                                                                
                                                                                
                                                 2719.95 2719.95 2719.84 2719.78
 2719.78
                                                                                
Pier Skew, UpSta & Num, DnSta & Num=  ,1576.68, 2 ,1641.68, 2 , 0 , 0 , 0 ,,
       6       6
       0    2720
       6       6
       0    2720
BR Coef=-1 ,-1 , 0 ,, 0 ,,,0.8,0,1.33,0,
WSPro=,,,, 1 ,,,, 0 ,,,, 0 ,,,,-1 ,-1 ,-1 , 0 , 0 , 0 , 0 , 0
BR U #Sta/Elev= 30
       0 2737.17    37.5 2732.47     145 2727.26   195.1 2719.49   258.2 2716.91
   283.4 2718.95   302.3 2718.49   314.9  2714.1   338.1 2719.14   366.5 2712.57
   403.5 2715.49   567.1 2712.02   759.9 2713.89   988.1 2721.06  1084.4 2721.06
  1180.6 2715.05  1252.7 2715.17    1460 2709.11  1490.6  2708.5 1601.49 2703.81
 1646.65 2708.56  1669.2 2712.92  1810.5 2708.48  1906.8 2709.88  1939.4 2713.23
  2215.1  2709.7  2337.2 2714.39  2353.5 2719.57  2418.7 2726.66  2459.6 2750.77
BR U #Mann= 10
       0     .06   258.2    .016   283.4     .06   338.1      .1   759.9     .08
  1084.4      .1  1252.7     .08    1460      .1  1490.6     .04 1646.65      .1
BR D #Sta/Elev= 30
       0 2735.33    96.3 2729.11   120.6 2728.65   180.4 2719.57   240.2 2717.77
   266.4 2717.36   295.4 2719.11   311.7 2713.78   338.4 2719.85   386.8 2712.48
   563.2 2713.09   605.1 2714.69     641 2720.39   682.4 2714.83  1485.1 2712.39
  1545.7 2712.34  1601.2 2708.79 1633.58 2701.84 1671.44 2703.71  1697.4 2708.63
  1705.7 2711.92  1749.4 2713.35  1777.5 2710.05  1861.6 2708.64  2278.3 2711.02
  2331.4 2707.09  2372.1 2719.66  2426.9 2717.04  2494.7 2723.86  2534.8 2746.87
BR D #Mann= 12
       0     .06    96.3     .07   180.4    .016   240.2     .06   266.4    .016
   295.4     .06   311.7      .1   682.4     .07  1485.1      .8  1545.7      .1
  1601.2     .04  1697.4      .1
BC Design=,, 0 ,, 0 ,,,,,,
BC Use User HTab Curves=0
BC User HTab FreeFlow(D)= 0

Type RM Length L Ch R = 1 ,467     ,260.5,277.2,253.2
BEGIN DESCRIPTION:
xs 2
END DESCRIPTION:
XS GIS Cut Line= 6
2304011.77513602565125.8318698152303505.12920009564670.106771867
2303214.21181495564634.3628867192302653.21840141564610.257700981
2301859.20295616564564.3574454412301684.39915391564668.407482484
#Sta/Elev= 30
       0 2735.33    96.3 2729.11   120.6 2728.65   180.4 2719.57   240.2 2717.77
   266.4 2717.36   295.4 2719.11   311.7 2713.78   338.4 2719.85   386.8 2712.48
   563.2 2713.09   605.1 2714.69     641 2720.39   682.4 2714.83  1485.1 2712.39
  1545.7 2712.34  1601.2 2708.79 1633.58 2701.84 1671.44 2703.71  1697.4 2708.63
  1705.7 2711.92  1749.4 2713.35  1777.5 2710.05  1861.6 2708.64  2278.3 2711.02
  2331.4 2707.09  2372.1 2719.66  2426.9 2717.04  2494.7 2723.86  2534.8 2746.87
#Mann= 12 ,-1,0
       0     .06       0    96.3     .07       0   180.4    .016       0
   240.2     .06       0   266.4    .016       0   295.4     .06       0
   311.7      .1       0   682.4     .07       0  1485.1     .08       0
  1545.7      .1       0  1601.2    .045       0  1697.4      .1       0
#XS Ineff= 2 , 0
          1570.6 2720.39  1713.8         2720.16
Permanent Ineff=
       F       F
Bank Sta=1601.2,1697.4
XS Rating Curve= 0 ,0
Exp/Cntr(USF)=0,0
Exp/Cntr=0.5,0.3

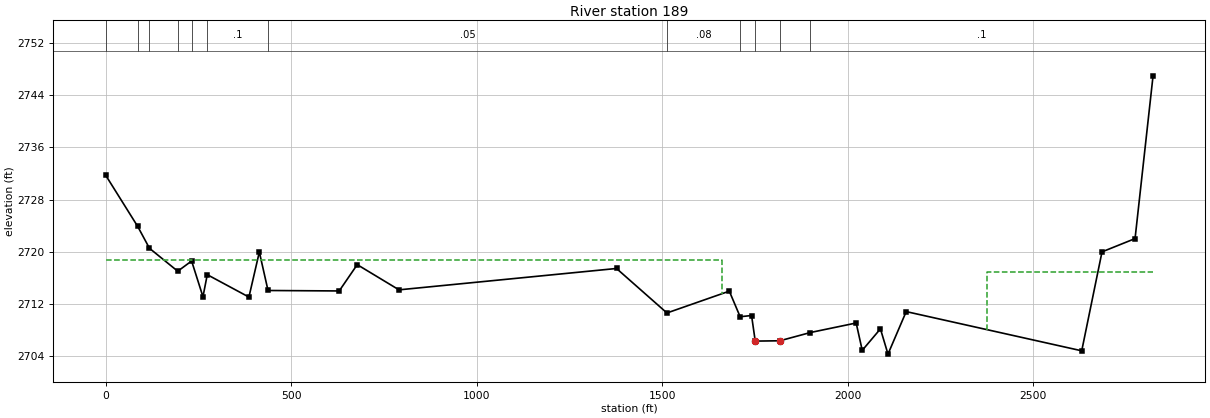
Type RM Length L Ch R = 1 ,189     ,,,
XS GIS Cut Line= 6
2304024.23154664565066.9567228452303613.71325829 564391.43134579
2303005.91913325564358.675973782 2302476.2829653564347.302580724
2301941.22396355564459.3259529922301661.48481417564666.028784045
#Sta/Elev= 30
       0 2731.71    85.8  2723.9   117.8 2720.52     194    2717   231.4 2718.57
     262 2713.08   273.6 2716.47   385.9 2713.03     414 2719.95   437.4 2714.04
   629.3 2713.97   677.9 2718.01   790.5 2714.14  1376.9 2717.42  1512.9 2710.59
    1681 2713.94  1710.2 2710.01    1741  2710.2  1750.9 2706.27  1817.3 2706.32
  1899.8 2707.59    2023 2709.05  2039.4 2704.85  2088.4 2708.15  2108.8 2704.27
  2157.9  2710.8  2631.1 2704.78  2685.8 2719.97  2774.9 2722.01  2823.4    2747
#Mann= 12 ,-1,0
       0     .08       0    85.8     .07       0   117.8     .08       0
     194    .016       0   231.4     .07       0   273.6      .1       0
   437.4     .05       0  1512.9     .08       0  1710.2     .08       0
  1750.9    .045       0  1817.3     .08       0  1899.8      .1       0
#XS Ineff= 2 , 0
         1661.41 2718.78 2375.22         2716.95
Permanent Ineff=
       F       F
Bank Sta=1750.9,1817.3
XS Rating Curve= 0 ,0
Exp/Cntr(USF)=0,0
Exp/Cntr=0.3,0.1
LCMann Table=0

Chan Stop Cuts=-1
Use User Specified Reach Order=0
Composite Channel Slope=5